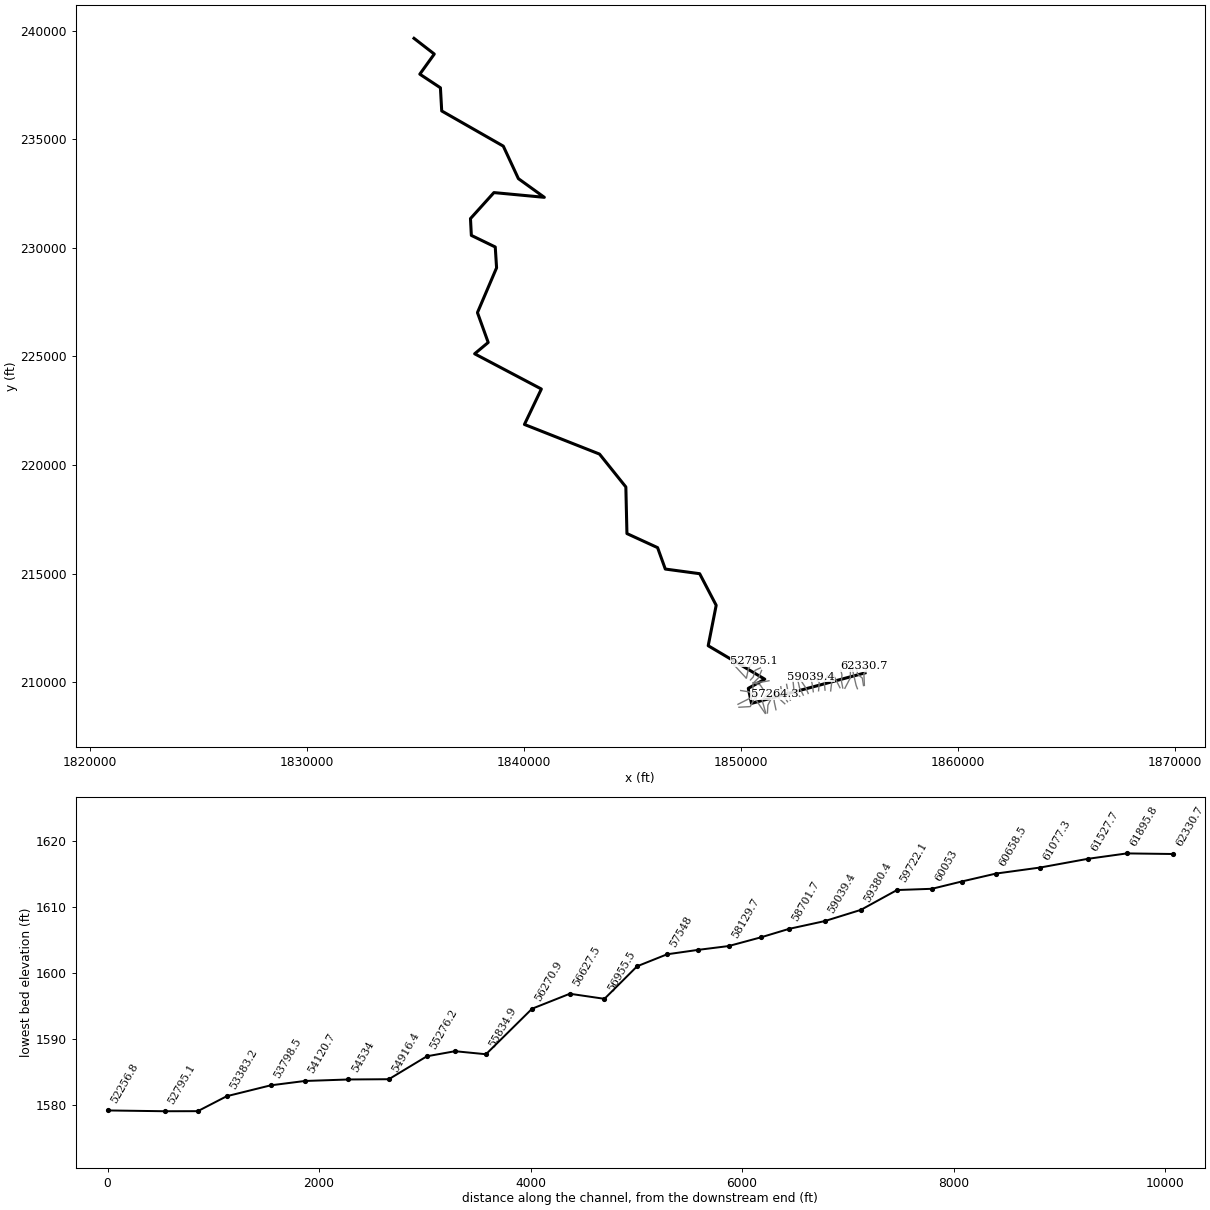
--- SUGARCK.prj (project) ---

Proj Title=SUGARCK
Current Plan=p01
Default Exp/Contr=0,0
English Units
Geom File=g01
Flow File=f01
Plan File=p01
BEGIN DESCRIPTION:
END DESCRIPTION:
DSS Export Rating Curves= 0
DSS Export Rating Curve Sorted= 0
DSS Export Volume Flow Curves= 0
DXF OffsetX= 0
DXF OffsetY= 0
DXF ScaleX= 0
DXF ScaleY= 0

--- SUGARCK.p01 (plan) ---

Plan Title=Floodplain
Program Version=4.00
Geom File=g01
Flow File=f01
K Sum by GR=0
Std Step Tol=0.01
Critical Tol=0.01
Num of Std Step Trials=20
Max Error Tol=0.3
Flow Tol Ratio=0.001
Split Flow NTrial=30
Split Flow Tol=0.02
Split Flow Ratio=0.02
Log Output Level=0
Friction Slope Method=1
Unsteady Friction Slope Method=2
Unsteady Bridges Friction Slope Method=1
Global Log Level=0
CheckData=False
Run HTab=0
Run UNet=0
Run PostProcess=0
UNET Theta=0
UNET Theta Warmup=0
UNET ZTol=0
UNET ZSATol=0
UNET MxIter=0
UNET MaxInSteps=0
UNET DtIC=0
UNET DtMin=0
UNET MaxCRTS=0
UNET WFStab=0
UNET SFStab=0
UNET WFX=0
UNET SFX=0
UNET DSS MLevel=0
UNET DZMax Abort=0
UNET Convert EG Bridges=0
UNET Use Existing IB Tables=0
UNET Froude Limit=0
UNET Froude Power=0
Write IC File=0
Echo Input=False
Echo Output=False
Write Detailed=0

--- SUGARCK.f01 (steady flow) ---

Flow Title=NFF Regression Equation
Program Version=4.10
Number of Profiles= 1
Profile Names=P100yr
River Rch & RM=SUGARCK,Main            ,62330.7
1194.186
River Rch & RM=SUGARCK,Main            ,58701.7
1288.988
River Rch & RM=SUGARCK,Main            ,55542.4
1371.746
River Rch & RM=SUGARCK,Main            ,55276.2
2107.256
River Rch & RM=SUGARCK,Main            ,46638.3
2295.261
River Rch & RM=SUGARCK,Main            ,46132.1
2615.841
River Rch & RM=SUGARCK,Main            ,41214.3
2774.969
River Rch & RM=SUGARCK,Main            ,30888.8
3074.948
River Rch & RM=SUGARCK,Main            ,30536.9
3772.255
River Rch & RM=SUGARCK,Main            ,25184.2
3873.173
River Rch & RM=SUGARCK,Main            ,23773.1
4268.832
River Rch & RM=SUGARCK,Main            ,9011.8
4581.127
River Rch & RM=SUGARCK,Main            ,8721.1
5715.587
River Rch & RM=SUGARCK,Main            ,294.5
5950.048
Boundary for River Rch & Prof#=SUGARCK,Main            , 1
Up Type= 0
Dn Type= 1
Dn Known WS=1521.55
DSS Import GetInterval= 0
DSS Import GetPeak= 0
DSS Import FillOption= 0

--- SUGARCK.g01 (geometry) ---

Geom Title=USGS 10m DEM
Program Version=4.10

River Reach=SUGARCK         ,Main
Reach XY= 30
     1855726.107      210424.787     1850495.882      209022.193
     1850348.598      209714.335     1851107.774      210135.629
     1848500.021       211677.32     1848868.076      213539.126
     1848106.271      214994.681     1846522.846      215208.309
     1846166.687      216194.681     1844754.188      216842.598
     1844703.834      218989.349     1843489.604      220503.709
     1840029.373       221867.96     1840809.743      223500.237
     1837733.395      225122.786     1838359.049      225643.987
     1837863.318      227019.196      1838745.16      229082.181
     1838684.049      230041.209     1837581.965      230575.237
      1837541.79      231348.838     1838623.632      232546.765
     1840946.541       232328.61     1839750.728      233189.068
     1839055.439        234686.3     1836215.993      236307.008
     1836156.493      237373.446     1835206.488      238001.408
     1835873.984      238927.795     1834939.316      239651.174

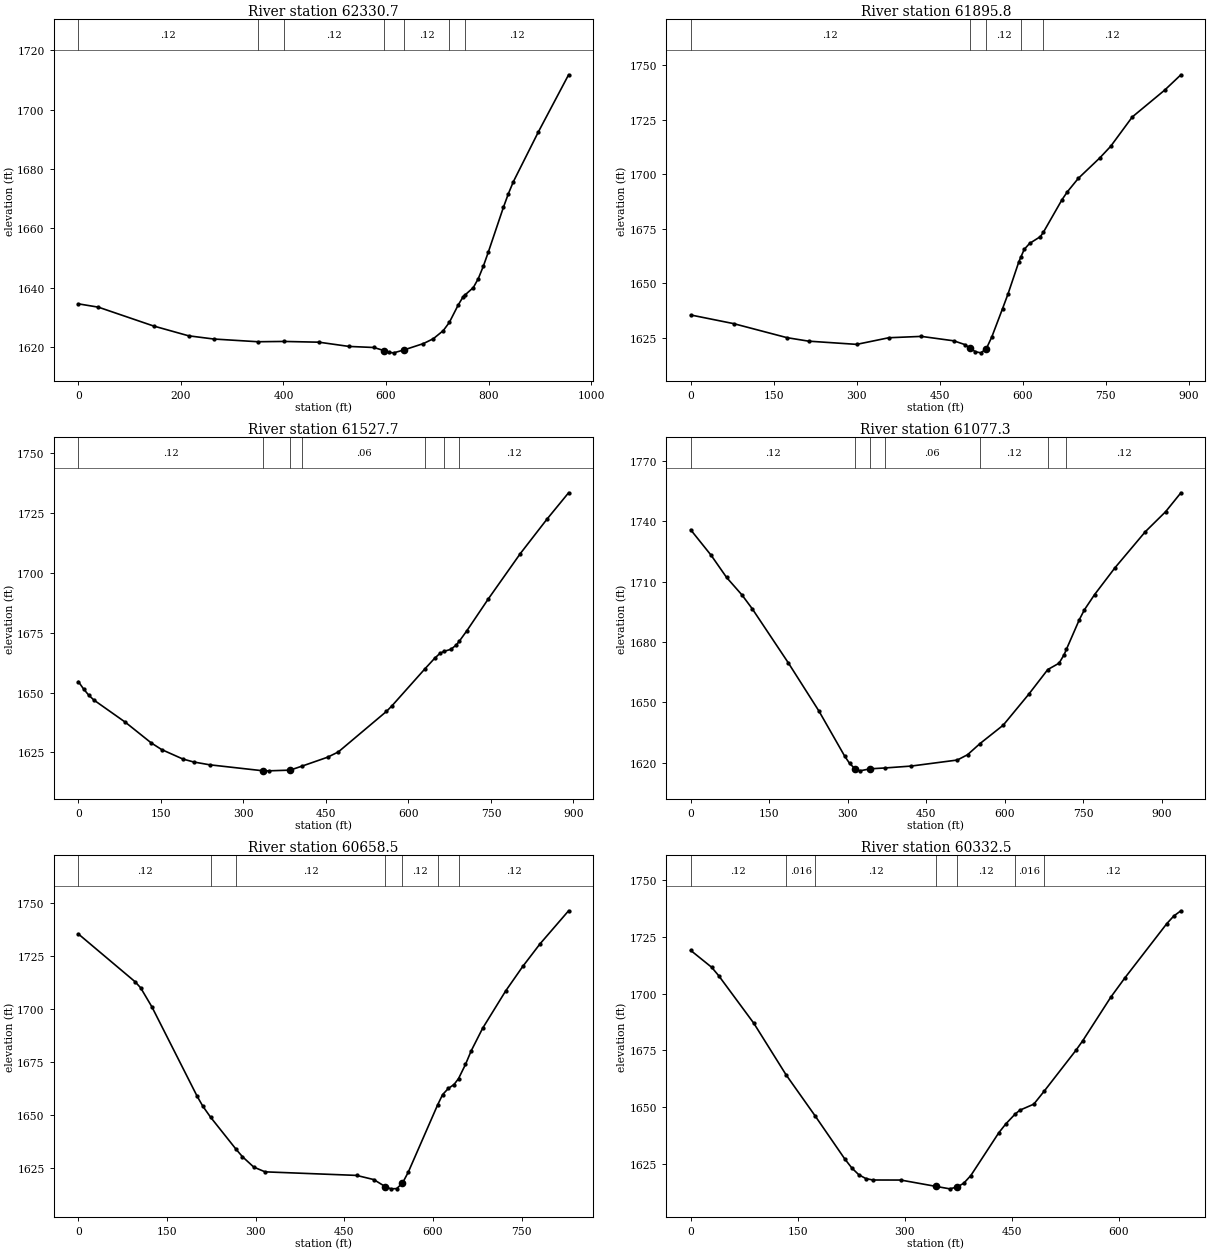
Type RM Length L Ch R = 1 ,62330.7 ,344.2,434.9,492.5
XS GIS Cut Line= 4
     1855699.847      209850.364      1855676.41      210397.239
     1855794.021      210511.948     1855684.646      210730.698
#Sta/Elev= 30
       0 1634.57    39.1 1633.45   146.6 1627.11     215  1623.8   263.9 1622.72
  350.18  1621.8  400.85  1621.9   469.2 1621.65   527.8 1620.22   576.4 1619.86
   595.7 1618.84   605.4  1618.2     615 1618.06   634.4    1619     673 1621.18
   692.3 1622.81   711.7 1625.54  723.56 1628.31     741 1634.22   750.8 1637.04
  754.731637.646   770.4 1640.06   780.1 1643.08   789.9 1647.25   799.7 1652.05
   829.1 1667.12   838.8 1671.71   848.6 1675.79   897.5  1692.6   956.2 1711.77
#Mann= 7 ,-1 , 0
       0     .12       0  350.18     .06       0  400.85     .12       0
   595.7    .045       0   634.4     .12       0  723.56    .016       0
  754.73     .12       0
Bank Sta=595.7,634.4
XS Rating Curve= 0 ,0
Exp/Cntr=0.3,0.1

Type RM Length L Ch R = 1 ,61895.8 ,395.1,368.1,340.9
XS GIS Cut Line= 4
      1855658.18      209842.552     1855603.917      210186.427
     1855392.979      210360.907     1855338.292      210618.719
#Sta/Elev= 30
       0 1635.51    77.4 1631.55   174.1  1625.1   212.8 1623.51   299.8 1622.03
   357.9 1625.07   416.6 1625.69   475.2 1623.66   494.8 1621.97   504.6 1620.25
   514.3 1618.66   524.1 1618.15   533.9 1620.03   543.7 1625.33   563.2 1638.36
     573 1645.04   592.6 1659.82  596.681662.226   602.3 1665.54   612.1  1668.3
   631.6 1671.42  636.821673.343   670.7 1688.37   680.4 1691.99     700  1698.1
     739 1707.53   758.5  1712.8   797.6 1726.28   856.1 1738.58   885.4 1745.61
#Mann= 5 ,-1 , 0
       0     .12       0   504.6    .045       0   533.9     .12       0
  596.68    .016       0  636.82     .12       0
Bank Sta=504.6,533.9
XS Rating Curve= 0 ,0
Exp/Cntr=0.3,0.1

Type RM Length L Ch R = 1 ,61527.7 ,470.4,450.4,424
XS GIS Cut Line= 3
     1855377.907      209697.802     1855320.063      209847.886
     1855153.396      210558.823
#Sta/Elev= 30
       0 1654.58     9.5 1651.51    18.9 1648.91    28.4 1646.86    85.2 1637.66
   132.5 1628.98   151.4 1626.21     190 1622.26   209.5 1621.03   238.7 1619.85
   336.1 1617.34   345.8 1617.33   384.8 1617.62  406.941619.331   452.9 1623.01
   472.4  1625.2     560 1642.14   569.8 1644.42  630.421660.038   647.6 1664.32
   657.4  1666.4  664.481667.203   676.9 1668.06   686.6 1669.78  692.681671.535
   706.1  1675.8     745 1689.06   803.4 1708.06   852.1  1722.5   891.1 1733.43
#Mann= 7 ,-1 , 0
       0     .12       0   336.1    .045       0   384.8     .12       0
  406.94     .06       0  630.42     .12       0  664.48    .016       0
  692.68     .12       0
Bank Sta=336.1,384.8
XS Rating Curve= 0 ,0
Exp/Cntr=0.3,0.1

Type RM Length L Ch R = 1 ,61077.3 ,405.4,418.8,432
XS GIS Cut Line= 3
     1854801.834      209717.677     1855054.438      210204.657
     1855054.438      210592.677
#Sta/Elev= 30
       0  1735.8    39.2 1723.08    68.6 1712.11      98 1703.41   117.6 1696.56
   186.1 1669.84   244.9 1645.78   293.9 1623.46   303.7 1619.67   313.5 1617.17
   323.3 1616.01   342.9 1617.02  370.781617.429   421.2 1618.38   509.4 1621.38
     529 1624.02  552.631629.527   597.1  1638.7   645.6 1653.98  682.281666.345
   703.8 1669.49   713.5 1673.74  717.731676.313   742.6 1691.17   752.3 1696.06
   771.7  1703.6   810.5 1716.88   868.7 1734.86   907.5 1744.81   936.6 1754.18
#Mann= 7 ,-1 , 0
       0     .12       0   313.5    .045       0   342.9     .12       0
  370.78     .06       0  552.63     .12       0  682.28    .016       0
  717.73     .12       0
Bank Sta=313.5,342.9
XS Rating Curve= 0 ,0
Exp/Cntr=0.3,0.1

Type RM Length L Ch R = 1 ,60658.5 ,302.9,325.9,348.1
XS GIS Cut Line= 4
     1854702.875      209730.698     1854637.771       210069.24
     1854666.417      210329.657     1854611.729      210545.802
#Sta/Elev= 30
       0 1735.19    95.8 1712.73   105.3 1709.87   124.5 1700.82   201.1 1658.68
   210.7    1654   223.91648.803  267.031633.694   277.7 1630.24   296.9 1625.33
     316  1623.1   470.9 1621.42     500 1619.45   519.4 1616.13   529.1 1615.09
   538.8 1615.21   548.5 1617.79   558.2 1622.85  607.831654.505   616.4 1659.47
   626.1 1662.39   635.8 1664.25  643.431667.042   655.2 1673.72   664.9 1680.15
   684.3  1690.8   723.1  1708.3   752.1 1719.88   781.2 1730.48   829.7 1746.12
#Mann= 7 ,-1 , 0
       0     .12       0   223.9    .016       0  267.03     .12       0
   519.4    .045       0   548.5     .12       0  607.83    .016       0
  643.43     .12       0
Bank Sta=519.4,548.5
XS Rating Curve= 0 ,0
Exp/Cntr=0.3,0.1

Type RM Length L Ch R = 1 ,60332.5 ,302.3,279.5,257.3
XS GIS Cut Line= 2
     1854572.667      209743.719     1854260.167      210355.698
#Sta/Elev= 30
       0 1719.07    29.4 1711.62    39.3  1707.9    88.4 1686.97  133.761664.162
  174.451646.065     216 1627.07   225.8 1623.12   235.6 1620.12   245.4 1618.43
   255.2 1617.78   294.5 1617.76   343.6 1614.97   363.2 1613.88   373.9 1614.73
   382.8 1616.36   392.7 1619.74   431.9 1638.61   441.7  1642.5  454.491646.765
   461.4 1648.57     481 1651.24  495.441656.921   539.9 1674.93   549.7 1679.26
     589 1698.47   608.6 1706.91   667.5  1730.9   677.3 1734.26   687.2 1736.54
#Mann= 7 ,-1 , 0
       0     .12       0  133.76    .016       0  174.45     .12       0
   343.6    .045       0   373.9     .12       0  454.49    .016       0
  495.44     .12       0
Bank Sta=343.6,373.9
XS Rating Curve= 0 ,0
Exp/Cntr=0.3,0.1

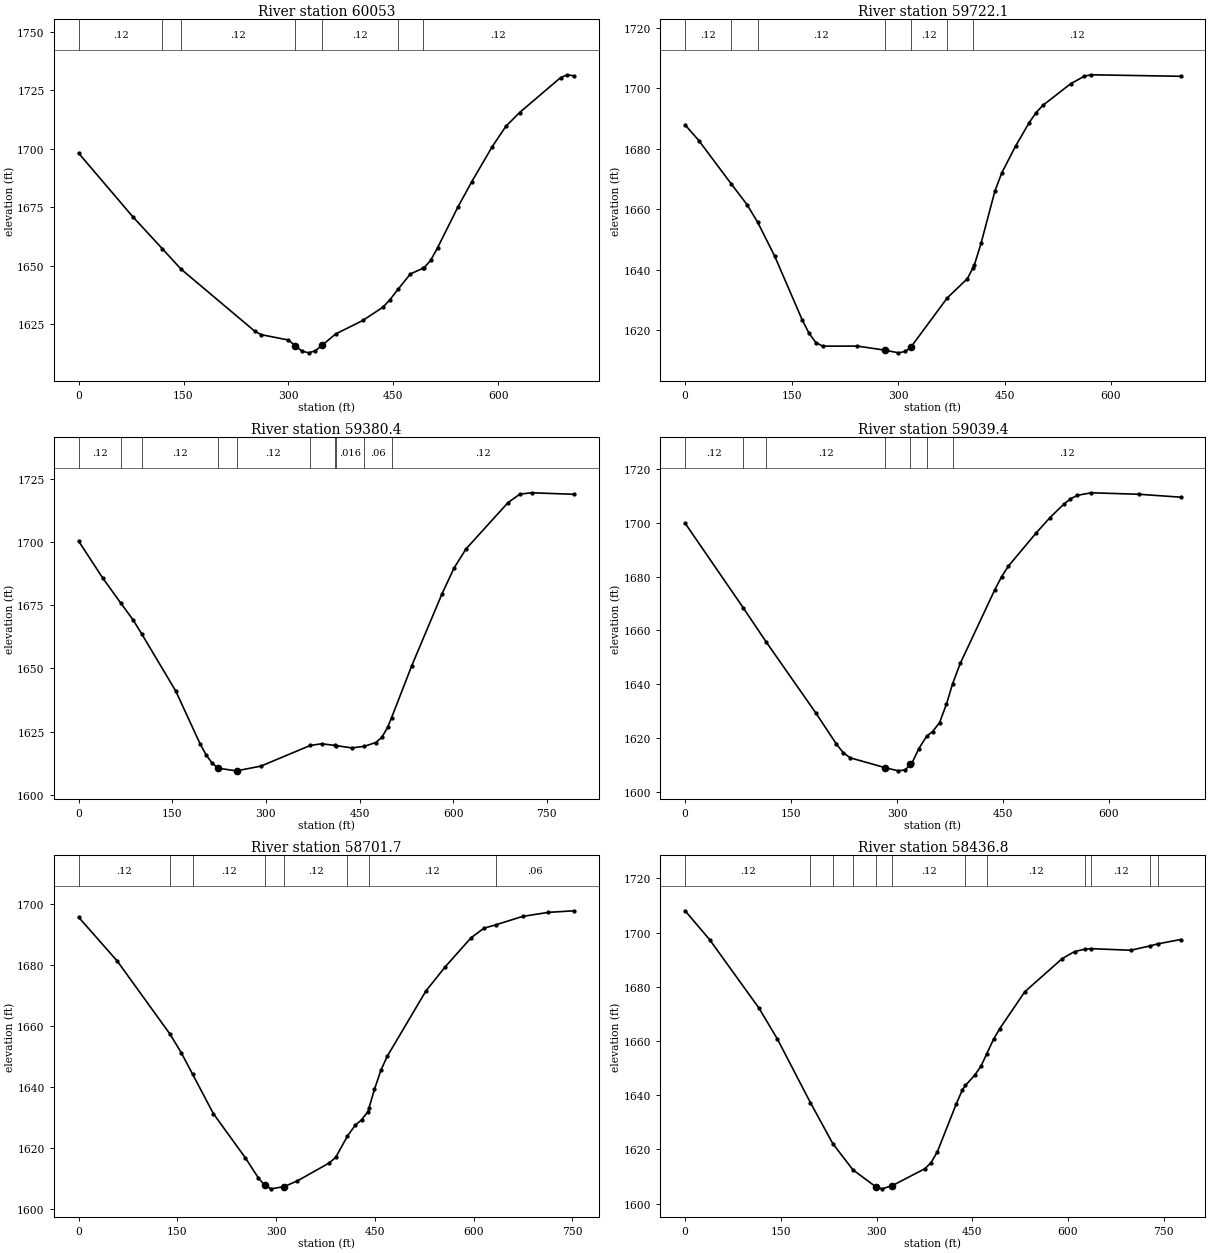
Type RM Length L Ch R = 1 ,60053   ,323.4,331,338.5
XS GIS Cut Line= 3
     1854145.584      209595.282     1854197.667      210027.573
      1854113.91      210287.864
#Sta/Elev= 30
       0 1698.05    77.4 1670.94  119.861657.198  146.571648.512   251.6  1622.1
   261.2 1620.54     300 1618.26   309.6 1615.86   319.3 1613.55     329 1612.78
   338.7 1613.66   348.3 1616.04   367.7 1620.84   406.4  1626.6   435.4  1632.3
   445.2 1635.41  457.04    1640   474.5 1646.47  492.131648.842     494 1649.04
   503.8 1652.43   513.5 1657.72   542.8 1675.23   562.4 1685.92   591.7  1700.9
   611.2 1709.57   630.7 1715.39   689.3 1730.31   699.1 1731.54   708.8 1731.05
#Mann= 7 ,-1 , 0
       0     .12       0  119.86    .016       0  146.57     .12       0
   309.6    .045       0   348.3     .12       0  457.04    .016       0
  492.13     .12       0
Bank Sta=309.6,348.3
XS Rating Curve= 0 ,0
Exp/Cntr=0.3,0.1

Type RM Length L Ch R = 1 ,59722.1 ,347.2,341.7,324.8
XS GIS Cut Line= 3
     1853885.167       209631.74     1853853.917      209998.927
     1853997.146      210295.802
#Sta/Elev= 30
       0 1687.88    19.4 1682.68   65.051668.379    87.3 1661.52  102.431655.642
   126.1 1644.57   164.9 1623.52   174.6 1619.03   184.3 1615.96     194  1614.8
   242.4 1614.82   281.2 1613.49   300.6 1612.59   310.3 1613.07   318.2 1614.51
  369.371630.748   397.6 1637.06  405.561640.662   407.3 1641.45     417 1648.81
   436.4 1665.97   446.1 1672.02   465.5 1680.83   484.8 1688.64   494.6 1691.96
   504.2 1694.36     543 1701.42   562.4 1703.95   572.1 1704.42   698.1 1703.92
#Mann= 7 ,-1 , 0
       0     .12       0   65.05    .016       0  102.43     .12       0
   281.2    .045       0   318.2     .12       0  369.37    .016       0
  405.56     .12       0
Bank Sta=281.2,318.2
XS Rating Curve= 0 ,0
Exp/Cntr=0.3,0.1

Type RM Length L Ch R = 1 ,59380.4 ,333.2,340.9,349.5
XS GIS Cut Line= 3
      1853587.76      209601.435      1853619.01      209989.456
     1853355.989      210296.748
#Sta/Elev= 30
       0 1700.29    38.9 1685.59    67.11675.975    87.6 1669.05  100.82 1663.74
   155.7 1641.04   194.6 1620.22   204.4 1615.82   214.1 1612.53   223.8  1610.6
     253 1609.58     292 1611.45  371.091619.604   389.3 1620.27  410.941619.594
  412.641619.528   437.4 1618.65   457.21619.238     476 1620.76   485.6 1622.76
   495.2 1626.86  501.291630.565   533.7 1651.13   581.9 1679.36   601.2 1689.57
   620.4 1697.16   687.8 1715.48   707.1 1718.87   726.4 1719.37   793.8 1718.76
#Mann= 10 ,-1 , 0
       0     .12       0    67.1    .016       0  100.82     .12       0
   223.8    .045       0     253     .12       0  371.09    .016       0
  410.94     .06       0  412.64    .016       0   457.2     .06       0
  501.29     .12       0
Bank Sta=223.8,253
XS Rating Curve= 0 ,0
Exp/Cntr=0.3,0.1

Type RM Length L Ch R = 1 ,59039.4 ,320.2,337.7,353.1
XS GIS Cut Line= 3
     1853343.495      209557.385     1853302.678      209866.098
     1853220.874       210247.28
#Sta/Elev= 30
       0 1699.83   82.051668.501  115.161655.584   184.9 1629.41   214.1 1617.84
   223.8 1614.63   233.6 1612.73   282.2 1609.11   301.7 1607.88   311.4 1608.25
   318.9 1610.24   321.2 1610.85   330.9 1616.17  341.951620.764   350.4 1622.48
   360.1 1625.78   369.9 1632.68  378.471640.128   389.4 1647.76   438.1    1675
   447.8  1679.9   457.6 1683.91   496.6 1696.13   516.1 1701.82   535.6 1706.81
   545.3 1708.86   555.1 1710.16   574.6 1711.12   642.8 1710.56   701.3 1709.49
#Mann= 7 ,-1 , 0
       0     .12       0   82.05    .016       0  115.16     .12       0
   282.2    .045       0   318.9     .12       0  341.95    .016       0
  378.47     .12       0
Bank Sta=282.2,318.9
XS Rating Curve= 0 ,0
Exp/Cntr=0.3,0.1

Type RM Length L Ch R = 1 ,58701.7 ,269.6,264.9,258.6
XS GIS Cut Line= 3
     1853108.869      209478.519     1853017.979      209704.657
     1852736.729      210129.136
#Sta/Elev= 30
       0 1695.59    58.5  1681.3  138.89 1657.32     156 1651.22  173.251644.185
   204.7 1631.32   253.5 1616.79   273.1 1610.27   282.9  1607.8   292.7  1606.7
   312.3 1607.44   331.8 1609.24   380.8 1615.17   390.6 1617.01  408.371623.946
     420 1627.47   429.8 1629.26   439.6 1632.01  441.361633.307   449.4 1639.23
   459.2 1645.47   468.9 1650.08   527.7 1671.47   557.1 1679.39   596.2 1688.86
   615.8    1692  633.461693.081   674.6 1695.86   713.8 1697.18   752.9  1697.7
#Mann= 8 ,-1 , 0
       0     .12       0  138.89    .016       0  173.25     .12       0
   282.9    .045       0   312.3     .12       0  408.37    .016       0
  441.36     .12       0  633.46     .06       0
Bank Sta=282.9,312.3
XS Rating Curve= 0 ,0
Exp/Cntr=0.3,0.1

Type RM Length L Ch R = 1 ,58436.8 ,320.9,307.1,293.5
XS GIS Cut Line= 3
       1852882.1      209402.294     1852708.084      209746.323
      1852622.71      210127.781
#Sta/Elev= 30
       0 1708.06    38.6 1697.36   115.7 1672.14   144.6 1660.72  196.271637.276
  231.62 1622.03  263.021612.429   298.8 1606.18   308.4 1605.42   324.6  1606.6
   375.9 1612.88   385.5 1615.14   395.3 1619.15   424.6 1636.62   434.4 1641.96
  439.21 1643.58   453.9 1647.41   463.7 1650.76  472.341655.133   483.3 1660.65
     493 1664.56   532.1 1678.13   590.8 1690.41   610.3 1693.01  627.121693.933
  636.011694.081   698.2 1693.49  728.581695.102  741.061695.869   776.4 1697.45
#Mann= 12 ,-1 , 0
       0     .12       0  196.27    .016       0  231.62     .12       0
  263.02    .016       0   298.8    .045       0   324.6     .12       0
  439.21    .016       0  472.34     .12       0  627.12     .06       0
  636.01     .12       0  728.58     .06       0  741.06     .12       0
Bank Sta=298.8,324.6
XS Rating Curve= 0 ,0
Exp/Cntr=0.3,0.1

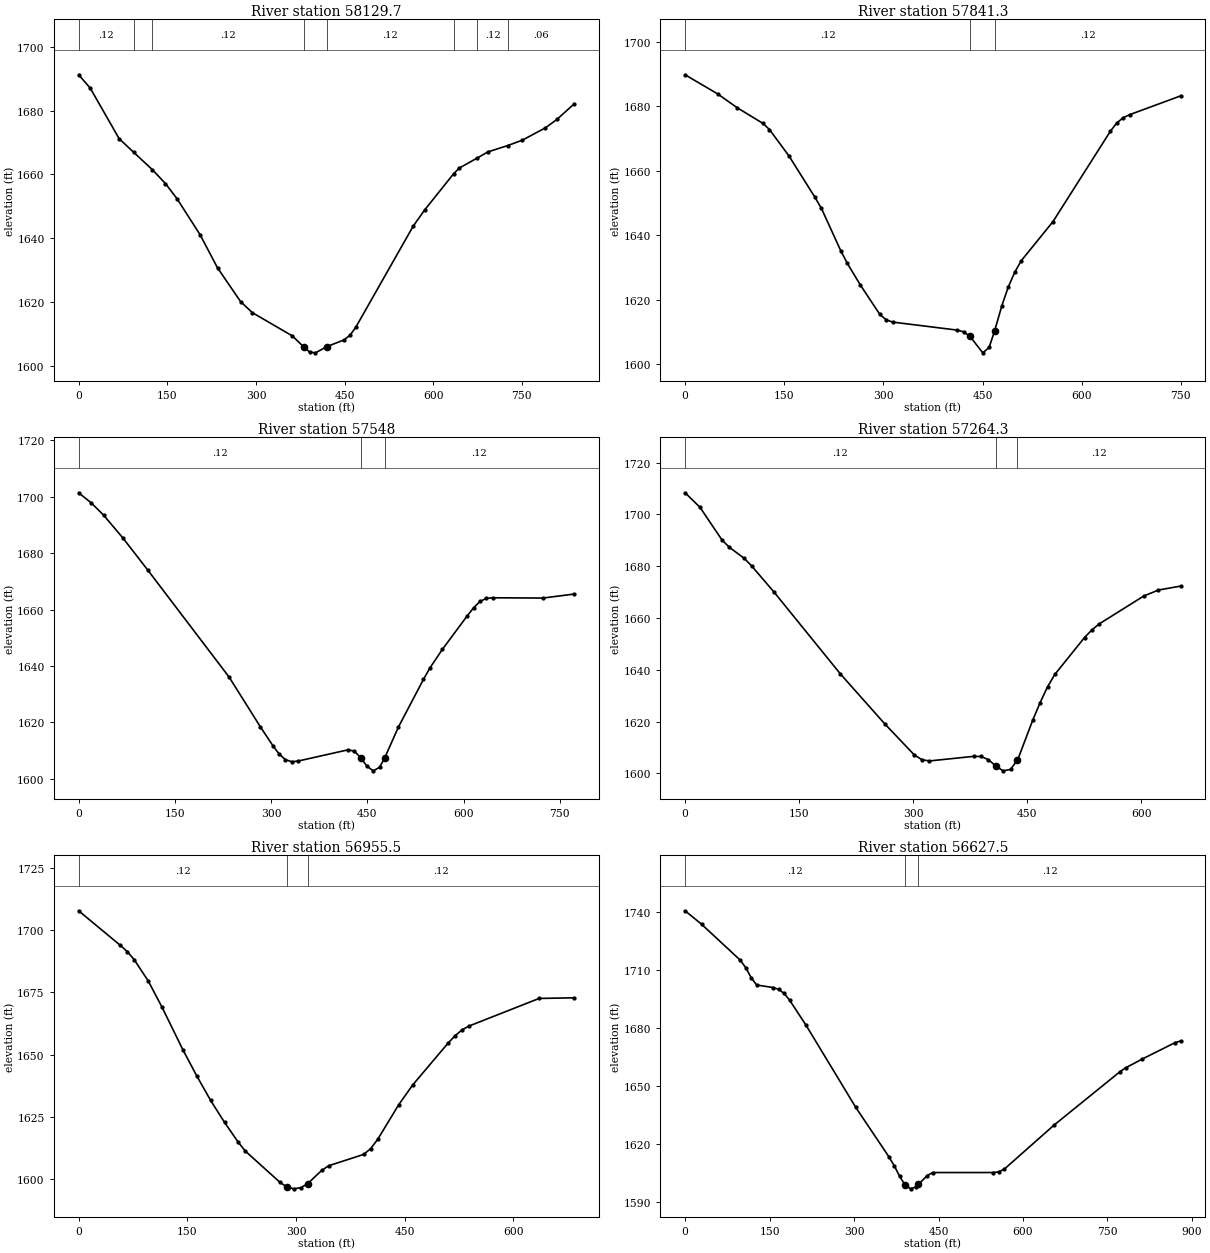
Type RM Length L Ch R = 1 ,58129.7 ,284.2,288.4,291.8
XS GIS Cut Line= 3
     1852716.166      209346.517     1852465.896      209480.698
     1852412.784      210032.557
#Sta/Elev= 30
       0 1691.24    19.6 1687.07    68.5 1671.22    92.91666.986  124.631661.516
   146.9 1657.15   166.5 1652.39   205.6 1641.07     235 1630.72   274.2 1620.11
   293.7 1616.71   361.8 1609.37   381.2 1605.88     391 1604.33   400.7 1604.09
   420.1 1606.05   449.3 1608.16     459 1609.58   468.8 1612.07     566 1643.78
   585.5 1648.89  634.391660.205   643.8 1661.98  674.38 1665.15   692.5 1667.07
   726.31669.072   750.8 1670.76   789.8 1674.62   809.2 1677.24   838.4 1682.13
#Mann= 8 ,-1 , 0
       0     .12       0    92.9    .016       0  124.63     .12       0
   381.2    .045       0   420.1     .12       0  634.39    .016       0
  674.38     .12       0   726.3     .06       0
Bank Sta=381.2,420.1
XS Rating Curve= 0 ,0
Exp/Cntr=0.3,0.1

Type RM Length L Ch R = 1 ,57841.3 ,279.3,293.3,303.9
XS GIS Cut Line= 3
     1852284.919      209167.541      1852187.25      209527.573
      1852113.68       209896.88
#Sta/Elev= 30
       0 1689.77    49.1 1683.86    78.5 1679.59   117.8 1674.68   127.6 1672.79
   157.1  1664.6   196.3  1651.8   206.2 1648.32   235.6 1635.13   245.4 1631.27
   265.1 1624.56   294.5 1615.46   304.3 1613.74   314.1 1613.05   411.7 1610.56
   421.3 1610.03     431  1608.6   450.3 1603.51   459.9 1605.18   468.2 1610.32
   479.2 1618.16   488.9 1623.95   498.6 1628.48   508.2 1632.01   556.5 1644.22
   643.4 1672.28     653 1674.82   662.7 1676.45   672.4 1677.39   749.6 1683.22
#Mann= 3 ,-1 , 0
       0     .12       0     431    .045       0   468.2     .12       0
Bank Sta=431,468.2
XS Rating Curve= 0 ,0
Exp/Cntr=0.3,0.1

Type RM Length L Ch R = 1 ,57548   ,274,283.7,296.4
XS GIS Cut Line= 3
     1852155.125      209096.665     1851887.771      209517.157
     1851846.104       209787.99
#Sta/Elev= 30
       0 1701.41    19.5 1697.86    39.1 1693.43    68.4 1685.55   107.5 1674.09
   234.5 1636.08   283.3 1618.42   302.9  1611.7   312.6 1608.77   322.4 1606.79
   332.2 1606.07     342 1606.31   420.1  1610.3   429.9  1609.8   439.7 1607.46
   449.4 1604.46   459.2 1602.84     469  1604.1     477 1607.41   498.3 1618.32
   537.4 1635.25   547.2 1639.21   566.8 1645.87   605.9 1657.86   615.7 1660.68
   625.5 1662.88   635.3 1663.98   645.1 1664.19   723.4 1664.09   772.3 1665.51
#Mann= 3 ,-1 , 0
       0     .12       0   439.7    .045       0     477     .12       0
Bank Sta=439.7,477
XS Rating Curve= 0 ,0
Exp/Cntr=0.3,0.1

Type RM Length L Ch R = 1 ,57264.3 ,336.4,308.8,280.2
XS GIS Cut Line= 2
     1852030.396      209004.273     1851551.834      209446.844
#Sta/Elev= 30
       0 1708.38    19.5  1702.8    48.6 1690.13    58.4 1687.28    77.8 1683.07
    87.6 1680.11   116.8  1670.1   204.3 1638.43   262.7 1619.13   301.6 1607.14
   311.3 1605.35     321 1604.83   379.4 1606.61   389.2 1606.57   398.9 1605.34
   408.6  1602.9   418.3 1601.02   428.1 1601.56   436.9 1605.18   437.8 1605.55
   457.3 1620.61     467 1627.38   476.7 1633.43   486.4 1638.28   525.4  1652.5
   535.1 1655.44   544.8 1657.77   603.2  1668.5   622.6 1670.83   651.8 1672.35
#Mann= 3 ,-1 , 0
       0     .12       0   408.6    .045       0   436.9     .12       0
Bank Sta=408.6,436.9
XS Rating Curve= 0 ,0
Exp/Cntr=0.3,0.1

Type RM Length L Ch R = 1 ,56955.5 ,349.5,327.9,307.7
XS GIS Cut Line= 3
      1851623.63       208728.72     1851546.625      209084.865
     1851512.771      209402.573
#Sta/Elev= 30
       0 1707.79    57.5 1693.91    67.1 1691.39    76.7 1688.15    95.9 1679.68
   115.1 1669.05   143.8    1652     163 1641.47   182.2 1631.58   201.4 1622.77
   220.5 1614.72   230.1 1611.23   278.1 1598.64   287.7 1596.78   297.2 1596.08
   306.8 1596.58   315.9  1598.1   335.6 1603.52   345.2 1605.36   393.4 1609.92
   403.1 1612.25   412.8    1616   441.8  1629.9   461.2 1637.87   509.6 1654.53
   519.3 1657.53     529  1659.9   538.6 1661.46   635.5 1672.57   683.9 1672.83
#Mann= 3 ,-1 , 0
       0     .12       0   287.7    .045       0   315.9     .12       0
Bank Sta=287.7,315.9
XS Rating Curve= 0 ,0
Exp/Cntr=0.3,0.1

Type RM Length L Ch R = 1 ,56627.5 ,365,356.6,348.2
XS GIS Cut Line= 3
     1851229.642      208580.768     1851252.354      208941.636
     1851489.334      209402.573
#Sta/Elev= 30
       0 1740.58    29.3  1733.6    97.7 1715.12   107.5 1711.26   117.3 1706.04
     127 1702.21   156.4  1700.9   166.1 1699.99   175.9 1697.84   185.7 1694.34
     215  1681.3     303 1638.97   361.6 1613.54   371.4 1608.78   381.1 1603.25
   390.9 1598.66   400.7 1596.85   410.5 1598.01   414.4 1599.14     430 1603.74
   439.8 1605.27   547.4 1605.28   557.2 1605.66   566.9 1607.06     655 1629.76
   772.3 1657.43   782.1 1659.36   811.4  1663.9   870.1 1672.43   879.9 1673.27
#Mann= 3 ,-1 , 0
       0     .12       0   390.9    .045       0   414.4     .12       0
Bank Sta=390.9,414.4
XS Rating Curve= 0 ,0
Exp/Cntr=0.3,0.1

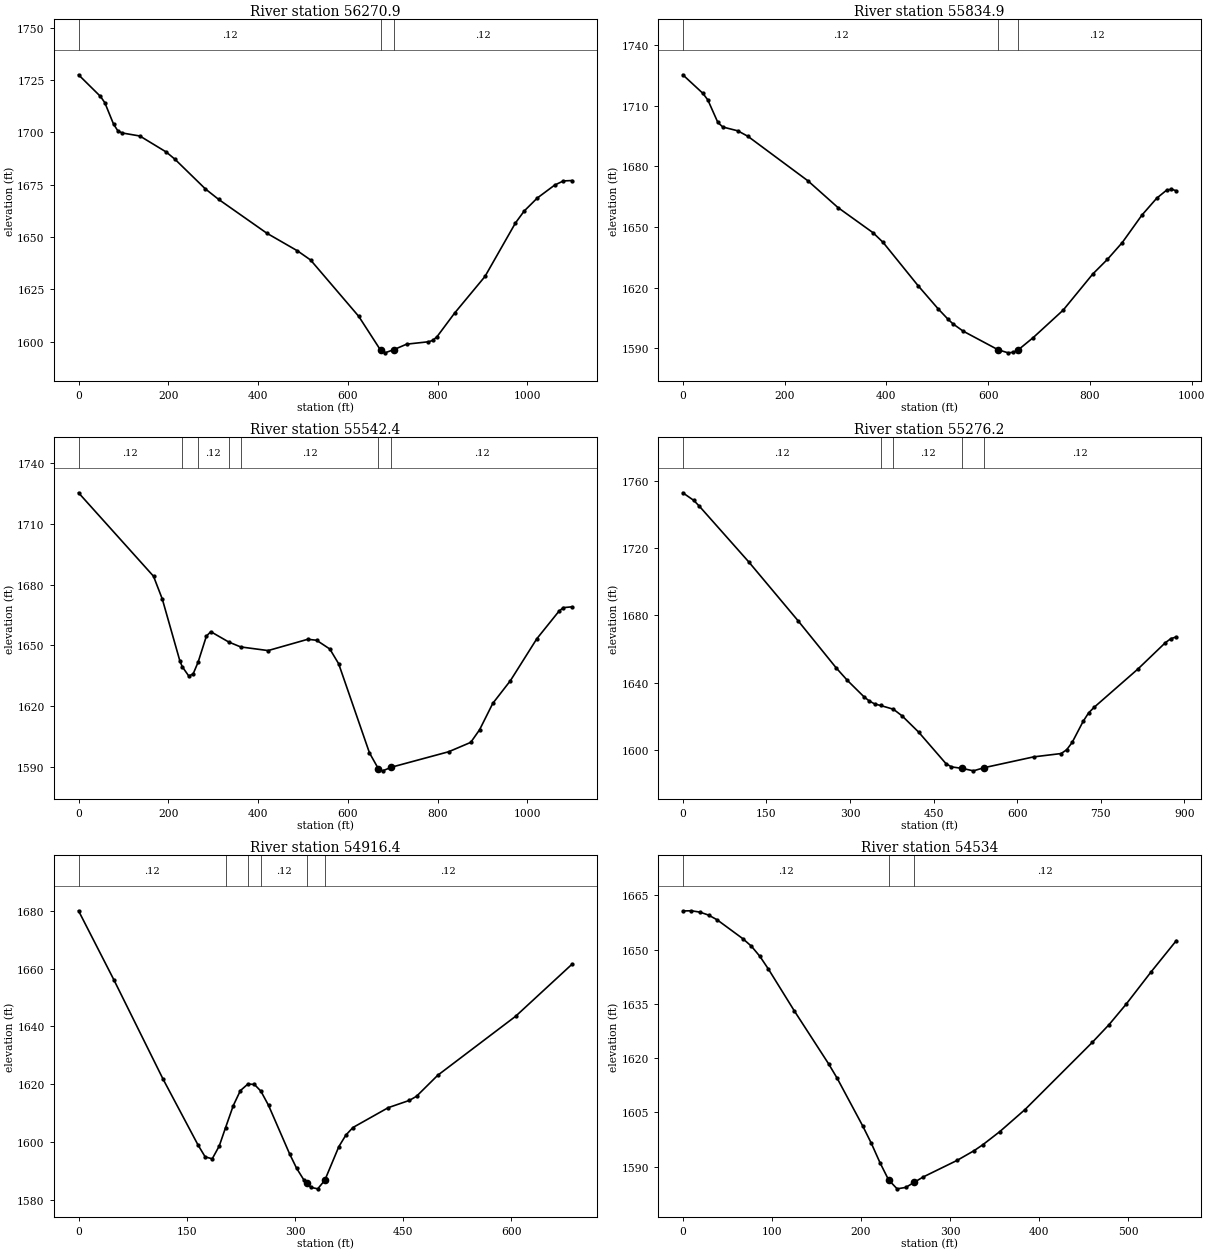
Type RM Length L Ch R = 1 ,56270.9 ,384.3,436,484.7
XS GIS Cut Line= 3
     1851150.792      208577.052     1850984.125      209178.615
     1851288.813      209543.198
#Sta/Elev= 30
       0 1727.51    48.8 1717.17    58.5 1714.19      78 1703.92    87.8 1700.64
    97.5 1699.68   136.6 1698.24   195.1 1690.62   214.6 1687.17   282.8  1672.9
   312.1 1667.94   419.4 1651.78   487.7 1643.34   516.9 1638.97   624.2 1612.02
   672.7  1595.9   682.4 1594.58   701.8 1596.05   730.9 1598.73   779.4 1599.87
   789.1 1600.51   798.8 1602.36   837.6 1613.54   905.4 1631.09   973.3 1656.67
   992.7 1662.36  1021.8 1668.57  1060.6 1674.77    1080 1676.76  1099.4 1676.95
#Mann= 3 ,-1 , 0
       0     .12       0   672.7    .045       0   701.8     .12       0
Bank Sta=672.7,701.8
XS Rating Curve= 0 ,0
Exp/Cntr=0.3,0.1

Type RM Length L Ch R = 1 ,55834.9 ,332.8,292.6,250.7
XS GIS Cut Line= 3
     1851127.354      208561.427     1850705.479      209178.615
     1850726.313      209399.969
#Sta/Elev= 30
       0  1725.4    39.4 1716.22    49.2 1712.94    68.9 1701.79    78.7 1699.52
   108.2 1697.63   127.9 1694.93   245.9 1672.88   304.9 1659.64   373.8 1647.18
   393.5 1642.42   462.3 1620.96   501.7  1609.5   521.4 1604.27   531.2 1601.98
   550.9 1598.43   619.7 1589.18   639.4 1587.67   649.1 1587.93   659.1 1589.12
   688.6 1595.21   747.6 1608.85   805.6 1626.69   834.6    1634   863.6 1642.28
   902.3  1655.9   931.3 1664.25   950.6 1668.21   960.3 1668.73   969.9 1667.94
#Mann= 3 ,-1 , 0
       0     .12       0   619.7    .045       0   659.1     .12       0
Bank Sta=619.7,659.1
XS Rating Curve= 0 ,0
Exp/Cntr=0.3,0.1

Type RM Length L Ch R = 1 ,55542.4 ,289.5,266.2,242.6
XS GIS Cut Line= 3
     1849917.649      208843.363      1850437.25      208873.927
     1850705.479      209386.948
#Sta/Elev= 30
       0  1725.3     167 1684.14   186.6 1672.88   225.9 1642.24  231.031639.513
   245.5 1634.93   255.3 1635.93  266.421641.779   284.8 1654.57   294.6 1656.78
  334.541651.689  361.181649.254   422.3 1647.46   510.7 1653.03   530.3 1652.54
   559.8 1648.22   579.4 1640.98   648.1 1596.99   667.7 1589.24   677.5 1588.13
   697.1 1589.93   824.7 1597.56   873.7 1602.18   893.4  1608.4   922.8 1621.42
     962  1632.6  1020.9  1653.3    1070 1666.82  1079.8 1668.64  1099.4 1669.04
#Mann= 7 ,-1 , 0
       0     .12       0  231.03    .016       0  266.42     .12       0
  334.54     .06       0  361.18     .12       0   667.7    .045       0
   697.1     .12       0
Bank Sta=667.7,697.1
XS Rating Curve= 0 ,0
Exp/Cntr=0.3,0.1

Type RM Length L Ch R = 1 ,55276.2 ,383.3,359.8,336.6
XS GIS Cut Line= 2
     1849873.276       208980.03     1850663.813      209379.136
#Sta/Elev= 30
       0  1753.1    19.7 1748.56    29.5 1745.18   118.1    1712   206.6 1676.92
   275.5 1648.63   295.2 1641.32   324.7 1631.64   334.6    1629   344.4 1627.23
  354.811626.317  377.931624.077   393.6 1620.09   423.1 1610.48   472.3 1591.63
   482.1 1589.72   501.8 1588.79   521.5 1587.36   541.2 1589.28   629.7 1595.69
   678.9 1597.67   688.8 1599.92   698.6 1604.26   718.3  1616.8   728.1 1621.86
     738  1625.2   816.7 1648.06   865.9 1663.74   875.7 1666.14   885.6  1667.2
#Mann= 5 ,-1 , 0
       0     .12       0  354.81    .016       0  377.93     .12       0
   501.8    .045       0   541.2     .12       0
Bank Sta=501.8,541.2
XS Rating Curve= 0 ,0
Exp/Cntr=0.3,0.1

Type RM Length L Ch R = 1 ,54916.4 ,436.9,382.4,327.8
XS GIS Cut Line= 3
     1849997.146      209613.511     1850382.563      209553.615
     1850629.959      209394.761
#Sta/Elev= 30
       0 1679.97    48.8  1656.2     117 1621.87   165.8 1598.95   175.5 1594.93
   185.3 1594.26     195 1598.68   203.71604.983   214.5 1612.66   224.3 1617.82
  234.811620.114   243.8 1619.94   252.71617.646   263.3 1612.74   292.5 1595.98
   302.3 1590.96     312 1587.07   316.7  1585.8   321.8 1584.42   331.5 1583.88
   341.3 1586.84   360.8 1598.48   370.5 1602.45   380.3 1605.07   429.2 1611.93
   458.6 1614.45   468.4 1615.86   497.8 1623.12   605.6 1643.48     684 1661.52
#Mann= 6 ,-1 , 0
       0     .12       0   203.7     .08       0  234.81    .016       0
   252.7     .12       0   316.7    .045       0   341.3     .12       0
Bank Sta=316.7,341.3
XS Rating Curve= 0 ,0
Exp/Cntr=0.3,0.1

Type RM Length L Ch R = 1 ,54534   ,390.1,413.2,436.1
XS GIS Cut Line= 3
     1850567.459      209967.677     1850559.646      209621.323
     1850642.979      209431.219
#Sta/Elev= 30
       0 1660.69     9.6 1660.74    19.2 1660.37    28.9 1659.55    38.5 1658.25
    67.4 1653.02      77 1650.95    86.6 1648.12    96.2 1644.58   125.1 1633.09
   163.6 1618.44   173.2 1614.46   202.1 1601.17   211.7  1596.4   221.3  1591.1
     231 1586.32   240.6 1583.84   250.2 1584.23   259.8 1585.64   269.5 1587.08
     308 1591.72   327.2 1594.43   336.8 1596.04   355.9 1599.68   384.2 1605.78
   459.7 1624.36   478.5 1629.26   497.4 1634.83   525.7 1643.85     554 1652.49
#Mann= 3 ,-1 , 0
       0     .12       0     231    .045       0   259.8     .12       0
Bank Sta=231,259.8
XS Rating Curve= 0 ,0
Exp/Cntr=0.3,0.1

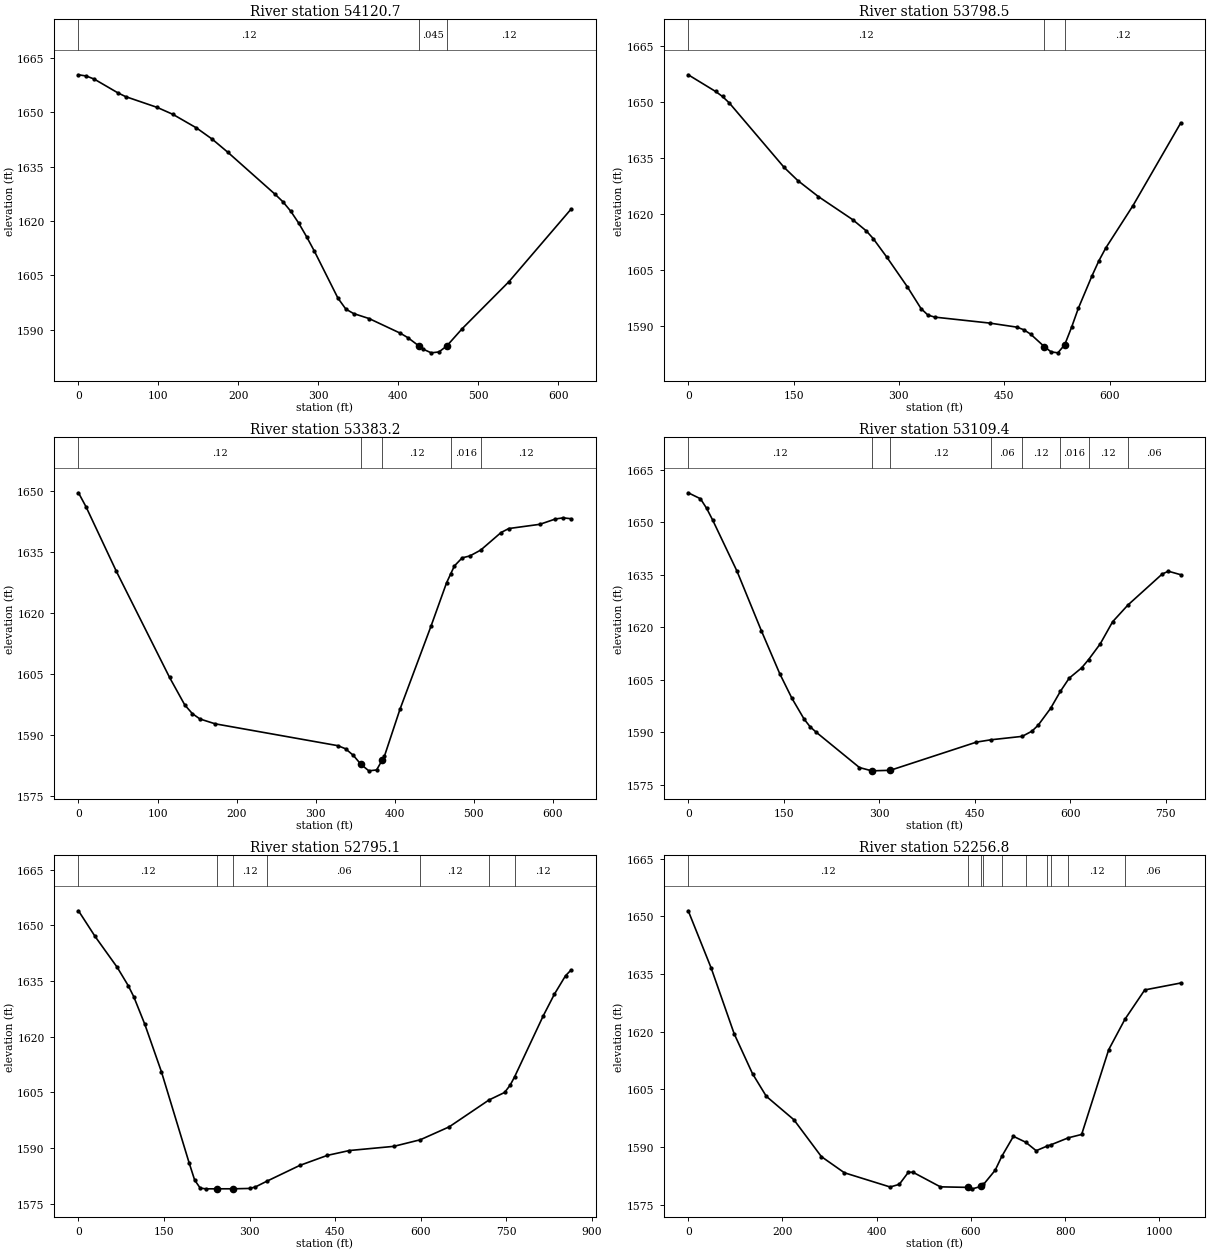
Type RM Length L Ch R = 1 ,54120.7 ,277.9,322.2,366.3
XS GIS Cut Line= 3
     1850575.271      209970.282     1850895.584      209873.927
     1851051.834      209639.552
#Sta/Elev= 30
       0 1660.36     9.8 1660.02    19.7 1659.17    49.2 1655.38      59 1654.33
    98.4 1651.36   118.1 1649.44   147.6 1645.69   167.2 1642.61   186.9 1638.96
     246 1627.37   255.8  1625.3   265.6 1622.69   275.5 1619.42   285.3 1615.69
   295.1 1611.68   324.6  1598.7   334.5 1595.68   344.2 1594.45   363.6 1593.07
   402.5 1589.04   412.2 1587.78   426.6  1585.4   431.6 1584.58   441.3 1583.61
     451 1583.86   460.8 1585.52   480.2 1590.32   538.5 1603.25   616.2 1623.27
#Mann= 3 ,-1 , 0
       0     .12       0   426.6    .045       0   460.8     .12       0
Bank Sta=426.6,460.8
XS Rating Curve= 0 ,0
Exp/Cntr=0.3,0.1

Type RM Length L Ch R = 1 ,53798.5 ,377.7,415.3,452.8
XS GIS Cut Line= 3
     1850606.521      209980.698     1851044.021      210014.552
     1851301.834      210064.032
#Sta/Elev= 30
       0 1657.21      39 1652.75    48.8 1651.41    58.5 1649.68   136.5 1632.48
     156 1628.96   185.3 1624.68     234 1618.54   253.5 1615.52   263.3 1613.48
   282.8 1608.49     312 1600.58   331.5 1594.76   341.3 1593.03     351 1592.49
   429.1  1590.9     468 1589.81   477.7 1589.12   487.4 1587.96   506.9 1584.62
   516.6 1583.21   526.3 1582.95     536  1585.1   545.8 1589.77   555.5 1594.88
   574.9 1603.52   584.6  1607.5   594.4 1610.93   633.3 1622.29   701.3 1644.37
#Mann= 3 ,-1 , 0
       0     .12       0   506.9    .045       0     536     .12       0
Bank Sta=506.9,536
XS Rating Curve= 0 ,0
Exp/Cntr=0.3,0.1

Type RM Length L Ch R = 1 ,53383.2 ,270.7,273.8,276.6
XS GIS Cut Line= 3
     1850640.375      210017.157     1850827.875      210209.865
     1850960.688       210537.99
#Sta/Elev= 30
       0 1649.65     9.6 1646.18      48  1630.3   115.2 1604.26   134.4  1597.5
     144 1595.36   153.6 1594.05   172.8 1592.86   327.9 1587.49   337.7 1586.73
   347.5 1585.12   357.4 1582.86   367.2  1581.3     377 1581.52   384.1 1583.94
   386.9  1584.9   406.5  1596.4   445.9 1616.91   465.5 1627.53  470.88 1629.78
   475.4 1631.67   485.2 1633.65     495 1634.13  508.671635.563   534.4 1639.88
   544.2 1640.86   583.5  1641.9   603.2 1643.21     613 1643.49   622.9 1643.27
#Mann= 5 ,-1 , 0
       0     .12       0   357.4    .045       0   384.1     .12       0
  470.88    .016       0  508.67     .12       0
Bank Sta=357.4,384.1
XS Rating Curve= 0 ,0
Exp/Cntr=0.3,0.1

Type RM Length L Ch R = 1 ,53109.4 ,310.1,314.3,317.6
XS GIS Cut Line= 4
     1850447.667       210100.49     1850577.875      210241.115
        1850656.      210540.594     1850903.396      210655.177
#Sta/Elev= 30
       0 1658.49    19.2 1656.78    28.8 1654.08    38.3 1650.73    76.7 1636.05
     115 1619.02   143.7 1606.82   162.9 1599.76   182.1  1593.8   191.6  1591.6
   201.3 1590.03     269 1579.97   288.4 1579.03   317.4 1579.18   452.8 1587.24
  475.521587.903  524.64 1588.88   540.1 1590.38   549.8 1592.09   569.3 1596.89
  584.71 1601.76   598.5 1605.52     618 1608.45  628.881610.807   647.2  1615.3
   666.7 1621.63  690.721626.412   744.6 1635.27   754.3 1636.07   773.8 1635.07
#Mann= 8 ,-1 , 0
       0     .12       0   288.4    .045       0   317.4     .12       0
  475.52     .06       0  524.64     .12       0  584.71    .016       0
  628.88     .12       0  690.72     .06       0
Bank Sta=288.4,317.4
XS Rating Curve= 0 ,0
Exp/Cntr=0.3,0.1

Type RM Length L Ch R = 1 ,52795.1 ,374.5,538.3,581.8
XS GIS Cut Line= 3
     1850264.507       210198.58     1850360.861      210643.893
     1850612.152      210965.108
#Sta/Elev= 30
       0  1653.9    29.1 1646.99    67.9 1638.67    87.2 1633.74    96.9 1630.76
   116.3 1623.32   145.4 1610.55   193.9 1586.04   203.6  1581.4   213.3 1579.23
     223 1579.02   242.4 1579.03   271.4 1579.03   300.5 1579.13   310.2 1579.54
  329.651581.034   387.8 1585.32   436.2 1588.03     475 1589.34   552.7 1590.46
  599.211592.238   649.8 1595.71  719.57 1602.95   746.9 1604.97   756.6 1606.92
  764.481609.188   814.9 1625.68   834.3 1631.46   853.7  1636.4   863.4 1637.94
#Mann= 7 ,-1 , 0
       0     .12       0   242.4    .045       0   271.4     .12       0
  329.65     .06       0  599.21     .12       0  719.57    .016       0
  764.48     .12       0
Bank Sta=242.4,271.4
XS Rating Curve= 0 ,0
Exp/Cntr=0.3,0.1

Type RM Length L Ch R = 1 ,52256.8 ,230.9,104.3,96.6
XS GIS Cut Line= 5
     1850244.542       210194.24     1849991.938      210465.073
     1849762.771      210715.073     1849669.021      210798.407
     1849723.709      211001.532
#Sta/Elev= 30
       0 1651.48    48.7 1636.58    97.5 1619.48   136.4  1609.1   165.7 1603.21
   224.2 1597.12   282.6 1587.52   331.4 1583.32   428.5 1579.62   447.9 1580.31
   467.2 1583.46   476.9 1583.46   535.1 1579.66   593.2 1579.52   602.9 1579.14
     621 1579.76   626.61580.279   651.4 1583.98  665.541587.614   690.1  1592.8
  716.141591.273   738.4 1589.06  761.441590.262  770.771590.647  806.751592.421
   834.9 1593.29   892.3 1615.34  926.791623.261   968.8 1630.89  1045.3 1632.69
#Mann= 10 ,-1 , 0
       0     .12       0   593.2    .045       0     621     .12       0
   626.6     .06       0  665.54    .016       0  716.14     .06       0
  761.44     .12       0  770.77     .06       0  806.75     .12       0
  926.79     .06       0
Bank Sta=593.2,621
XS Rating Curve= 0 ,0
Exp/Cntr=0.3,0.1