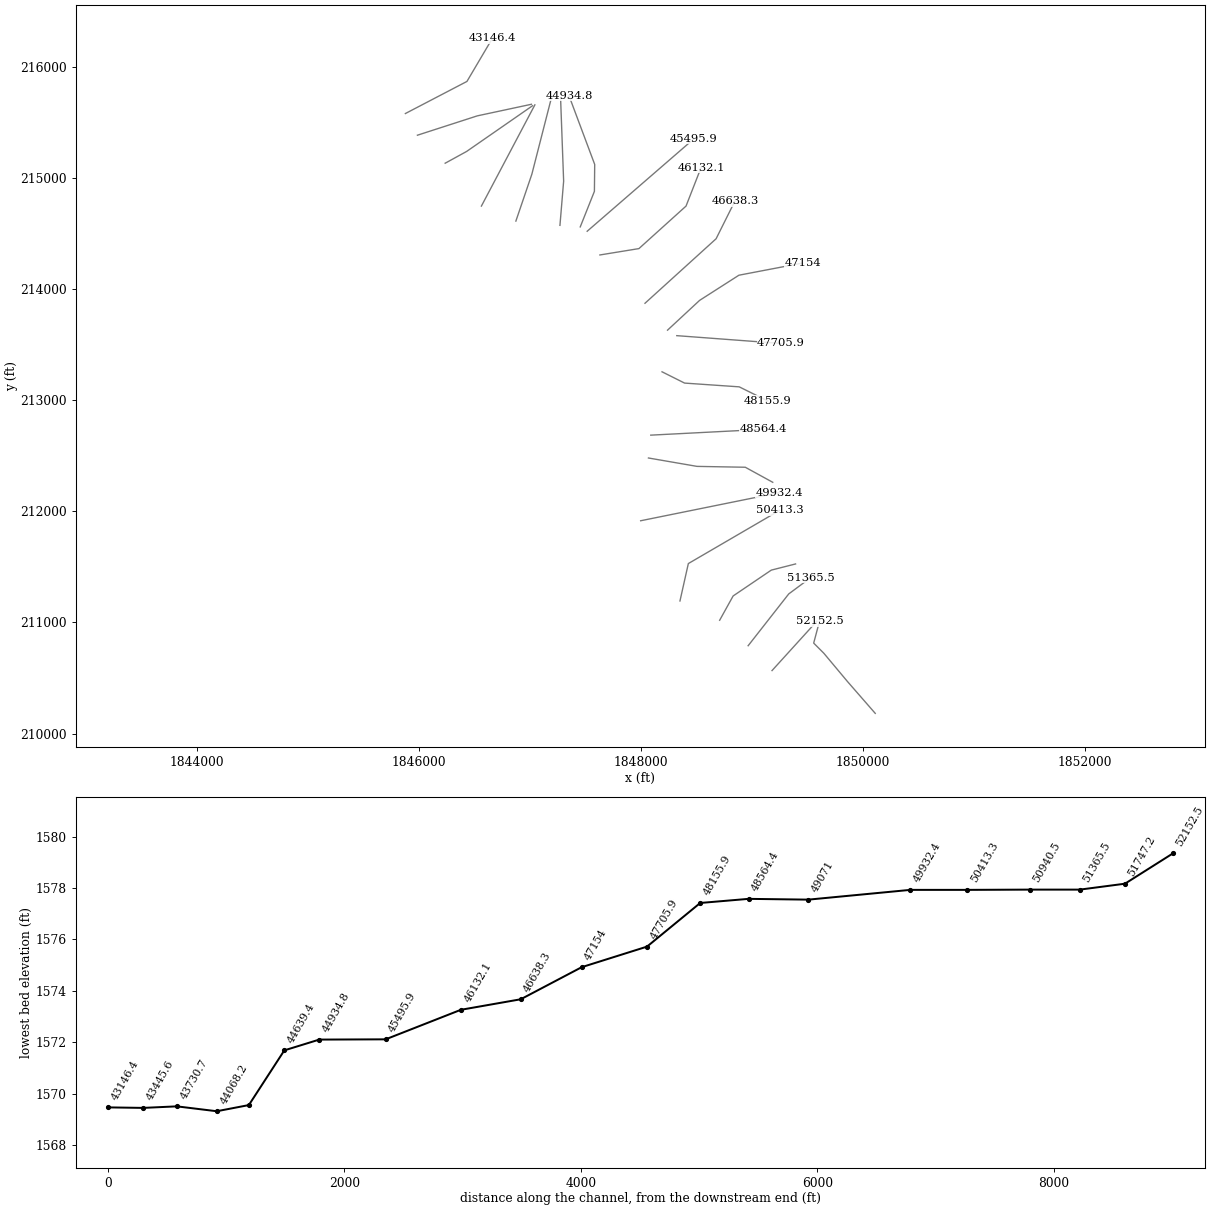
HEC-RAS study SUGARCK.prj: SUGARCK

--- SUGARCK.g01 (geometry) --- (continued)

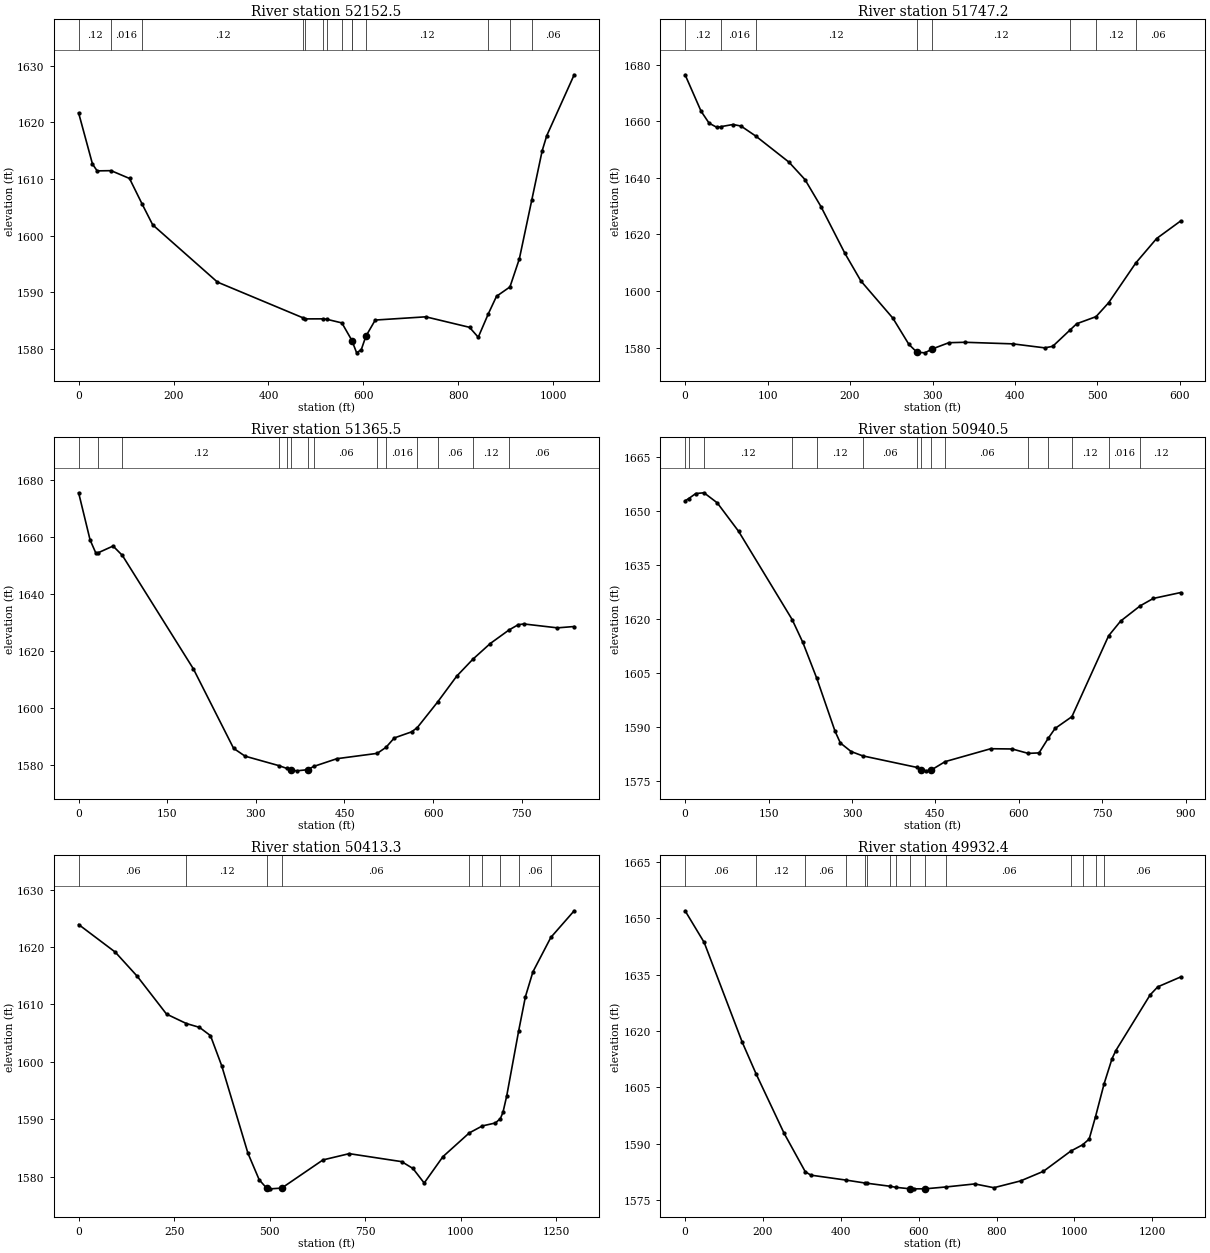
Type RM Length L Ch R = 1 ,52152.5 ,461.9,405.3,349.5
XS GIS Cut Line= 5
     1850114.334      210181.219     1849864.334      210467.677
     1849650.792      210722.886     1849559.646      210814.032
     1849611.729      211009.344
#Sta/Elev= 30
       0 1621.64    29.2 1612.63      39 1611.43   68.411611.466   107.2 1610.09
  133.521605.623     156 1601.92   292.5 1591.82  472.591585.525  477.261585.334
  515.531585.343   522.41585.275  554.591584.625  575.011581.639     576 1581.46
   585.7 1579.35   595.5 1579.92   605.2 1582.28   624.9 1585.13   731.4  1585.7
   823.5 1583.85   841.9  1582.1   863.41586.282   880.4 1589.32  908.681590.969
   928.5 1595.92  954.731606.304   976.6 1614.98   986.3 1617.65    1044 1628.37
#Mann= 14 ,-1 , 0
       0     .12       0   68.41    .016       0  133.52     .12       0
  472.59    .016       0  477.26     .12       0  515.53    .016       0
   522.4     .12       0  554.59    .016       0  575.01     .12       0
     576    .045       0   605.2     .12       0   863.4    .016       0
  908.68     .12       0  954.73     .06       0
#XS Ineff= 2 , 0
       0     530                       0
Permanent Ineff=
       F       F
Bank Sta=576,605.2
XS Rating Curve= 0 ,0
Exp/Cntr=0.3,0.1

Type RM Length L Ch R = 1 ,51747.2 ,377.9,381.7,384
XS GIS Cut Line= 2
     1849184.222       210566.51     1849588.292       211011.08
#Sta/Elev= 30
       0 1676.37    19.4 1663.49    29.1 1659.28    38.8 1657.76   44.041658.082
    58.1 1658.81    67.8 1658.26   85.811654.698     126  1645.5   145.4 1639.34
   164.7 1629.83   193.8 1613.28   213.2 1603.53   251.9 1590.42   271.3 1581.17
     281  1578.4   290.7 1578.17   299.8 1579.56   319.8 1581.75   339.1  1581.9
   397.3 1581.34     436 1579.93   445.7 1580.47  466.241586.111   474.8 1588.45
  498.23 1590.95   513.6  1595.9  546.421609.907   571.7 1618.55   600.8 1624.74
#Mann= 8 ,-1 , 0
       0     .12       0   44.04    .016       0   85.81     .12       0
     281    .045       0   299.8     .12       0  466.24    .016       0
  498.23     .12       0  546.42     .06       0
Bank Sta=281,299.8
XS Rating Curve= 0 ,0
Exp/Cntr=0.3,0.1

Type RM Length L Ch R = 1 ,51365.5 ,436.2,425,410.1
XS GIS Cut Line= 3
     1848969.175      210790.366      1849334.82       211256.74
     1849532.556      211403.371
#Sta/Elev= 30
       0 1675.66    19.4 1659.08    29.2 1654.44   32.071654.484    58.3 1656.94
   74.031653.648   194.3 1613.75   262.3 1585.85   281.7  1583.1  339.221579.754
  352.331578.792   359.5 1578.25   369.2 1577.94   387.6 1578.34  397.781579.478
   437.2 1582.21  505.451584.085  520.351586.212   534.3  1589.5   563.5 1591.63
  573.161593.114  607.751602.151     640 1611.22  667.24 1617.15   696.8 1622.69
  728.421627.432   744.1  1629.3   753.6 1629.56   810.4 1628.19   838.8 1628.66
#Mann= 14 ,-1 , 0
       0     .12       0   32.07    .016       0   74.03     .12       0
  339.22     .06       0  352.33     .12       0   359.5    .045       0
   387.6     .12       0  397.78     .06       0  505.45     .12       0
  520.35    .016       0  573.16     .12       0  607.75     .06       0
  667.24     .12       0  728.42     .06       0
Bank Sta=359.5,387.6
XS Rating Curve= 0 ,0
Exp/Cntr=0.3,0.1

Type RM Length L Ch R = 1 ,50940.5 ,530.1,527.2,522.4
XS GIS Cut Line= 4
     1848712.424      211019.761     1848833.952      211238.511
     1849177.702       211471.15     1849396.452      211526.705
#Sta/Elev= 30
       0 1652.91    6.211653.505    19.2 1654.93      341655.141    57.8 1652.35
    96.2 1644.44  192.521619.934   211.7 1613.59   236.81603.613   269.6 1588.94
   279.2 1585.67   298.5  1583.3   319.21582.104   416.21578.913     424 1578.23
   433.6 1577.94   442.8 1578.19  467.621580.501   549.5 1584.08   588.1 1584.01
  616.861582.788   636.4 1582.92  652.931586.982   665.3 1589.72  695.49 1592.98
  761.451615.423   783.1 1619.52  818.371623.761   841.9 1625.81     891 1627.44
#Mann= 15 ,-1 , 0
       0     .12       0    6.21    .016       0      34     .12       0
  192.52     .06       0   236.8     .12       0   319.2     .06       0
   416.2     .12       0     424    .045       0   442.8     .12       0
  467.62     .06       0  616.86     .12       0  652.93    .016       0
  695.49     .12       0  761.45    .016       0  818.37     .12       0
Bank Sta=424,442.8
XS Rating Curve= 0 ,0
Exp/Cntr=0.3,0.1

Type RM Length L Ch R = 1 ,50413.3 ,488.8,481,470.9
XS GIS Cut Line= 3
     1848354.785      211193.372     1848430.306      211530.177
     1849253.222      212009.344
#Sta/Elev= 30
       0 1623.91    95.9 1619.11   153.4 1614.91   230.1 1608.33  281.911606.689
   316.4 1606.02   345.2 1604.58   374.6 1599.34   443.3 1584.12   472.8  1579.5
   492.4 1578.04   502.2 1577.93   531.7 1578.06   639.7 1582.96   708.4 1584.05
   845.8 1582.66   875.3 1581.47   904.7 1578.94   953.8 1583.53 1022.781587.658
 1056.971588.873  1091.3 1589.39  1104.2 1590.16  1110.9 1591.22  1120.7 1594.06
 1152.071605.409  1169.8 1611.37  1189.4 1615.68 1236.341621.668  1297.4  1626.3
#Mann= 9 ,-1 , 0
       0     .06       0  281.91     .12       0   492.4    .045       0
   531.7     .06       0 1022.78     .12       0 1056.97    .016       0
  1104.2     .12       0 1152.07     .06       0 1236.34     .12       0
Bank Sta=492.4,531.7
XS Rating Curve= 0 ,0
Exp/Cntr=0.3,0.1

Type RM Length L Ch R = 1 ,49932.4 ,667.9,861.4,808.8
XS GIS Cut Line= 2
     1848000.618      211915.594     1849248.014      212168.198
#Sta/Elev= 30
       0 1652.04      49  1643.6   146.8    1617  182.711608.485   254.5 1592.69
  308.741582.472   323.1 1581.58  413.831580.255  463.241579.461  467.061579.426
  525.831578.624  541.951578.327   577.6 1577.94   587.1 1577.93   616.8 1577.94
  671.241578.443     744 1579.24     793 1578.23   861.5 1580.04   920.3  1582.6
  990.491587.988 1020.731589.652  1037.8  1591.2 1054.111597.176 1076.29 1605.99
  1096.5 1612.62  1106.3 1614.79  1194.4 1629.63    1214 1631.77  1272.7  1634.4
#Mann= 15 ,-1 , 0
       0     .06       0  182.71     .12       0  308.74     .06       0
  413.83     .12       0  463.24     .06       0  467.06     .12       0
  525.83     .06       0  541.95     .12       0   577.6    .045       0
   616.8     .12       0  671.24     .06       0  990.49     .12       0
 1020.73    .016       0 1054.11     .12       0 1076.29     .06       0
Bank Sta=577.6,616.8
XS Rating Curve= 0 ,0
Exp/Cntr=0.3,0.1

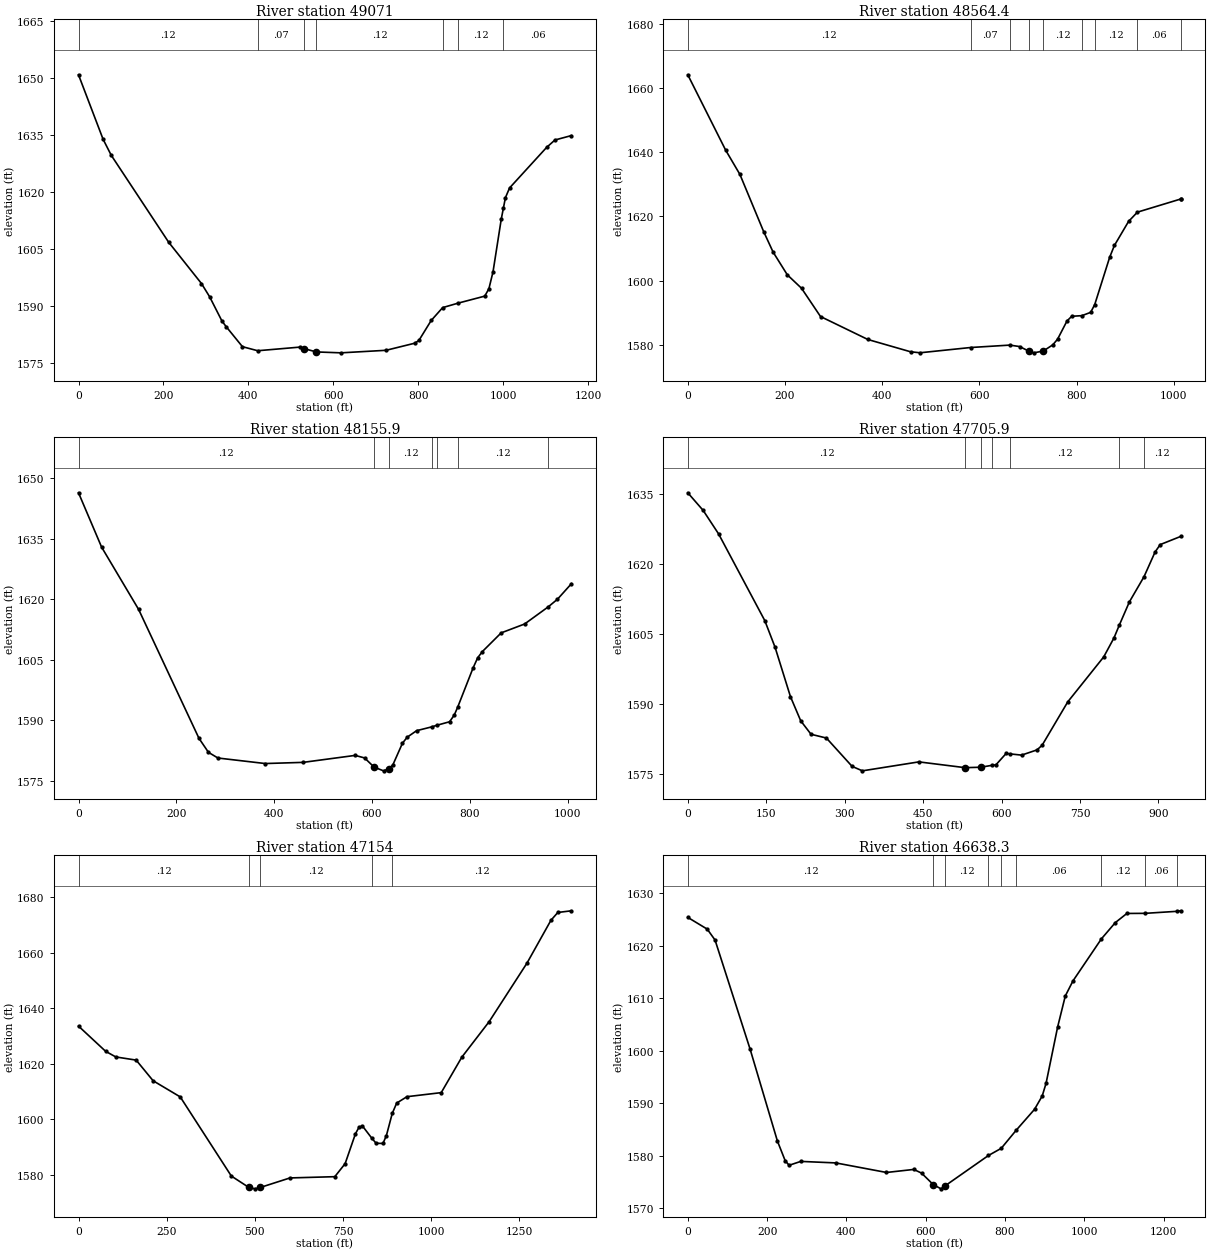
Type RM Length L Ch R = 1 ,49071   ,490.8,506.6,508.5
XS GIS Cut Line= 4
     1848070.931      212480.698     1848508.431      212405.177
     1848943.327      212397.365     1849190.722      212261.948
#Sta/Elev= 30
       0 1650.85    57.9 1633.85    77.2 1629.61   212.3 1606.71   289.6 1595.82
   308.8 1592.33   337.8 1585.94   347.5 1584.49   386.1 1579.17  422.041578.105
   521.3 1579.06     531 1578.67     560 1577.79     618 1577.55   724.3 1578.22
   791.9 1580.09   801.6 1580.81   830.6 1586.08  857.621589.476  894.181590.658
   956.7  1592.5   966.5 1594.45   976.2 1598.91   995.6  1612.8 1000.651615.712
  1005.4 1618.45  1015.1 1621.01  1102.6 1631.73  1122.1 1633.66    1161 1634.83
#Mann= 7 ,-1 , 0
       0     .12       0  422.04     .07       0     531    .045       0
     560     .12       0  857.62    .016       0  894.18     .12       0
 1000.65     .06       0
Bank Sta=531,560
XS Rating Curve= 0 ,0
Exp/Cntr=0.3,0.1

Type RM Length L Ch R = 1 ,48564.4 ,412.6,408.5,403.6
XS GIS Cut Line= 2
     1848091.764      212686.427     1849104.785      212738.511
#Sta/Elev= 30
       0 1664.07      78 1640.61   107.3 1633.07   156.1  1615.3   175.6 1608.91
   204.8 1601.85   234.1 1597.66   273.1 1588.88   370.6 1581.73   458.4 1577.91
   477.9  1577.6  581.841579.236  662.631579.986   682.7 1579.54   703.1 1578.01
     712 1577.58   731.5 1578.14     751 1580.06   760.8  1581.8   780.3 1587.49
     790 1588.95  810.881589.144     829 1590.17  837.35 1592.59   868.1  1607.3
   877.8 1610.97   907.1 1618.48  925.211621.341 1013.981625.412  1014.4 1625.43
#Mann= 9 ,-1 , 0
       0     .12       0  581.84     .07       0  662.63     .12       0
   703.1    .045       0   731.5     .12       0  810.88    .016       0
  837.35     .12       0  925.21     .06       0 1013.98     .12       0
Bank Sta=703.1,731.5
XS Rating Curve= 0 ,0
Exp/Cntr=0.3,0.1

Type RM Length L Ch R = 1 ,48155.9 ,449.2,450,449.5
XS GIS Cut Line= 4
     1848193.327       213256.74     1848396.452      213155.177
     1848888.639      213121.323     1849146.452      212993.719
#Sta/Elev= 30
       0 1646.37    47.3 1632.88     123 1617.43   246.4 1585.47   265.8    1582
   285.1  1580.6   381.9 1579.23   459.3 1579.52   565.7 1581.25     585 1580.62
   604.4 1578.35   623.7 1577.42   635.8 1577.97   643.1 1578.97   662.4 1584.26
   672.1 1585.76   691.4 1587.38  722.771588.336  732.461588.709   758.8 1589.59
   768.4 1591.26  775.331593.195   806.8 1602.92   816.3 1605.46   825.9    1607
   864.3 1611.63   912.2 1613.83   960.31618.059   979.4 1619.97  1008.1 1623.84
#Mann= 7 ,-1 , 0
       0     .12       0   604.4    .045       0   635.8     .12       0
  722.77     .08       0  732.46    .016       0  775.33     .12       0
   960.3     .06       0
Bank Sta=604.4,635.8
XS Rating Curve= 0 ,0
Exp/Cntr=0.3,0.1

Type RM Length L Ch R = 1 ,47705.9 ,537.1,551.9,568.2
XS GIS Cut Line= 2
     1848326.139      213582.261     1849266.243      213511.948
#Sta/Elev= 30
       0 1635.33    29.5 1631.54    58.9 1626.52   147.3 1607.92   166.9 1602.22
   196.4 1591.61     216 1586.44   235.7 1583.56   265.1 1582.75   314.2 1576.68
   333.9 1575.72   441.9 1577.64   530.3  1576.4   559.8 1576.49  581.891576.903
   589.2    1577   608.8 1579.45  615.941579.356   638.3 1579.09   667.8 1580.21
   677.6 1581.21   726.7 1590.52   795.4 1600.15   815.1 1604.24   825.21606.964
   844.5 1611.95  872.441617.337   893.6 1622.64   903.4 1624.22   942.7 1625.98
#Mann= 7 ,-1 , 0
       0     .12       0   530.3    .045       0   559.8     .12       0
  581.89    .016       0  615.94     .12       0   825.2    .016       0
  872.44     .12       0
#XS Ineff= 2 , 0
       0                     610       0
Permanent Ineff=
       F       F
Bank Sta=530.3,559.8
XS Rating Curve= 0 ,0
Exp/Cntr=0.3,0.1

Type RM Length L Ch R = 1 ,47154   ,492.9,515.7,508.4
XS GIS Cut Line= 4
     1848242.806       213631.74     1848531.868      213899.969
     1848886.035      214126.532     1849458.952      214235.907
#Sta/Elev= 30
       0 1633.55    76.9 1624.47   105.8 1622.44   163.5  1621.3   211.6 1613.86
   288.5 1608.04   433.4 1579.53   482.3 1575.49   500.4 1574.92   515.4 1575.41
   599.7 1578.85   726.8  1579.3   756.1    1584   785.4 1594.78   795.2 1597.05
     805  1597.6  831.511593.201   843.9 1591.34   863.4 1591.27   873.1 1594.11
  889.671602.082   902.3 1605.82   931.4 1608.12  1028.6 1609.58    1087 1622.36
  1164.7 1635.19  1271.7 1656.23  1339.7 1671.67  1359.2 1674.49    1398  1675.1
#Mann= 5 ,-1 , 0
       0     .12       0   482.3    .045       0   515.4     .12       0
  831.51    .016       0  889.67     .12       0
Bank Sta=482.3,515.4
XS Rating Curve= 0 ,0
Exp/Cntr=0.3,0.1

Type RM Length L Ch R = 1 ,46638.3 ,506.2,506.2,504.4
XS GIS Cut Line= 3
     1848039.681      213873.927     1848680.306      214454.657
     1848849.577      214793.198
#Sta/Elev= 30
       0 1625.41    49.1 1623.17    68.8 1621.09   157.2 1600.29     226 1582.79
   245.6 1579.04   255.5 1578.16     285  1578.9   373.4 1578.61   501.1 1576.79
   569.9 1577.37   589.5 1576.67     619 1574.48   638.7 1573.67   649.6 1574.28
  758.191580.026  790.491581.391  828.321584.851   874.4 1588.82   893.8 1591.37
   903.5 1593.78   932.6 1604.49     952 1610.43   971.4 1613.31 1043.18 1621.33
  1078.2 1624.42  1107.3 1626.16 1153.261626.181  1234.4 1626.57  1243.2 1626.67
#Mann= 9 ,-1 , 0
       0     .12       0     619    .045       0   649.6     .12       0
  758.19    .016       0  790.49     .12       0  828.32     .06       0
 1043.18     .12       0 1153.26     .06       0  1234.4     .12       0
Bank Sta=619,649.6
XS Rating Curve= 0 ,0
Exp/Cntr=0.3,0.1

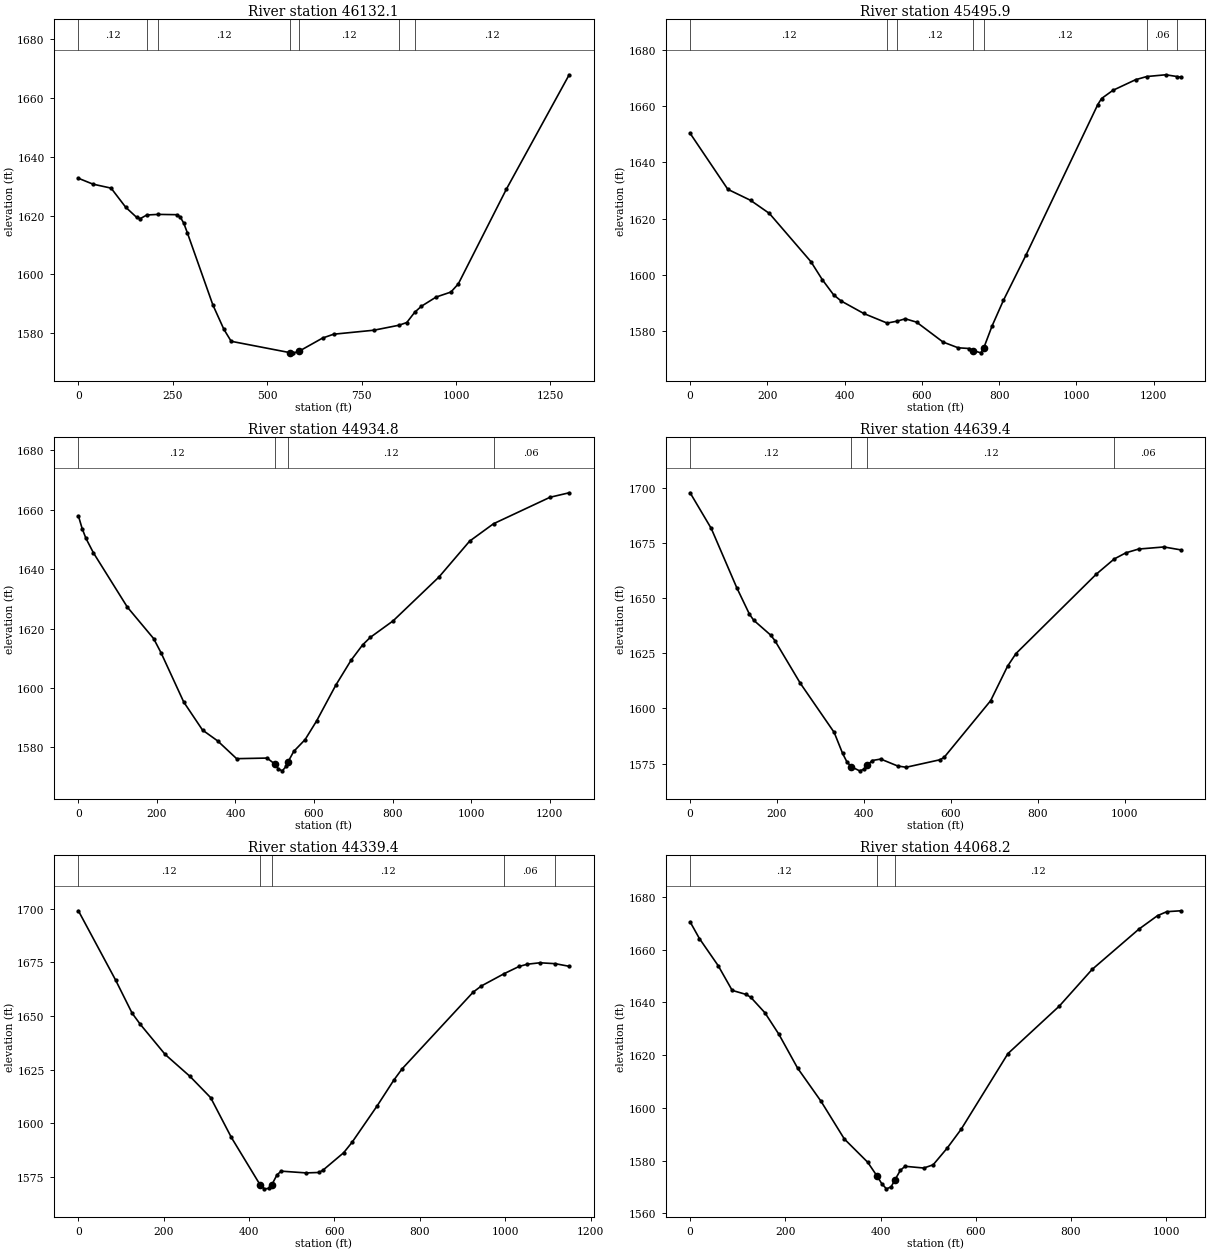
Type RM Length L Ch R = 1 ,46132.1 ,631,636.1,617.4
XS GIS Cut Line= 4
     1847633.431      214308.823     1847984.993      214366.115
     1848409.472      214748.927     1848544.889      215095.282
#Sta/Elev= 30
       0 1632.68    38.5 1630.68    86.6 1629.32   125.2 1622.83     154  1619.4
   163.7 1618.93  181.191620.182   211.71620.381   259.9 1620.28   269.6 1619.53
   279.2 1617.35   288.8 1614.03   356.2 1589.54   385.3 1581.27   404.6 1577.19
   559.6 1573.34   569.3 1573.26   583.2 1573.72   646.8  1578.3   675.9  1579.6
   782.5 1580.96  849.111582.661   869.7 1583.58  890.691587.072   908.4 1589.12
   947.4 1592.25   986.5 1593.95  1006.1 1596.72  1133.3 1628.94  1299.7  1667.9
#Mann= 7 ,-1 , 0
       0     .12       0  181.19    .016       0   211.7     .12       0
   559.6    .045       0   583.2     .12       0  849.11    .016       0
  890.69     .12       0
Bank Sta=559.6,583.2
XS Rating Curve= 0 ,0
Exp/Cntr=0.3,0.1

Type RM Length L Ch R = 1 ,45495.9 ,529.9,561.2,590.8
XS GIS Cut Line= 2
     1847518.847      214522.365     1848479.279      215353.838
#Sta/Elev= 30
       0 1650.38    97.7  1630.4   156.4 1626.49   205.2 1621.81   312.7 1604.62
     342 1598.24   371.3 1592.82   390.9  1590.6   449.5 1586.14  510.061582.718
  536.091583.415     557 1584.25   586.3 1583.05   654.7 1575.96   693.8 1573.91
   723.1 1573.65   732.9 1572.93   752.4 1572.11   760.4 1573.95   781.8 1581.74
   811.1 1590.84   869.7 1607.04  1055.4 1660.64  1065.1 1662.78  1094.4 1665.69
  1153.1 1669.48 1182.271670.617  1231.3 1671.24 1261.621670.593  1270.4 1670.36
#Mann= 7 ,-1 , 0
       0     .12       0  510.06     .06       0  536.09     .12       0
   732.9    .045       0   760.4     .12       0 1182.27     .06       0
 1261.62     .12       0
Bank Sta=732.9,760.4
XS Rating Curve= 0 ,0
Exp/Cntr=0.3,0.1

Type RM Length L Ch R = 1 ,44934.8 ,297.4,295.3,298.6
XS GIS Cut Line= 4
     1847456.347      214561.427     1847583.952       214881.74
     1847586.556      215123.927     1847354.279      215744.463
#Sta/Elev= 30
       0 1657.97     9.6 1653.69    19.2  1650.4    38.3 1645.52   124.5 1627.27
   191.6 1616.64   210.7  1611.8   268.2 1595.28   316.1 1585.83   354.5 1582.19
   402.9  1576.2   480.4  1576.4   499.8 1574.42   509.5 1572.69   519.2  1572.1
   528.9 1573.61   533.3 1574.99   548.2 1578.63   577.3 1582.63   606.5  1588.9
   655.2 1600.91   694.2 1609.33   723.4 1614.47   742.9 1617.02   801.4 1622.62
   918.3 1637.41   996.2 1649.47 1057.061655.328  1200.9 1664.24  1249.6 1665.75
#Mann= 4 ,-1 , 0
       0     .12       0   499.8    .045       0   533.3     .12       0
 1057.06     .06       0
Bank Sta=499.8,533.3
XS Rating Curve= 0 ,0
Exp/Cntr=0.3,0.1

Type RM Length L Ch R = 1 ,44639.4 ,307.8,300,289.1
XS GIS Cut Line= 3
     1847273.403      214575.386     1847306.706      214973.563
     1847279.867      215702.308
#Sta/Elev= 30
       0 1697.82    48.7 1681.62   107.2 1654.81   136.4 1642.78   146.2 1640.01
   185.2 1633.27   194.9  1630.8   253.4 1611.43   331.4  1589.1   350.8 1579.56
   360.6 1575.77   370.3 1573.59   389.8 1571.68   399.6 1572.36   407.1 1574.12
     419 1576.37   438.5 1577.02   477.4 1573.88   496.8  1573.3   574.6  1576.7
   584.3 1577.79   691.3 1603.52   730.2 1619.16   749.6 1624.91   934.3 1660.91
  975.371667.779  1002.4 1670.59  1031.6 1672.29  1089.9 1673.24  1128.8 1671.91
#Mann= 4 ,-1 , 0
       0     .12       0   370.3    .045       0   407.1     .12       0
  975.37     .06       0
Bank Sta=370.3,407.1
XS Rating Curve= 0 ,0
Exp/Cntr=0.3,0.1

Type RM Length L Ch R = 1 ,44339.4 ,277.2,271.3,262.4
XS GIS Cut Line= 3
     1846876.381      214613.942     1847020.263      215035.646
      1847195.14       215718.01
#Sta/Elev= 30
       0 1699.06    87.2 1666.79   125.9 1651.36   145.3 1646.11   203.4 1632.13
   261.5 1621.92     310    1612   358.4  1593.5   426.2 1571.29   435.9 1569.55
   445.6 1569.73   453.1 1571.41   465.1 1575.96   474.9 1577.79   533.6 1576.97
     563 1577.17   572.8 1578.19   621.7 1586.39   641.2 1591.21     700 1608.17
   739.1 1620.18   758.6 1625.45     925 1661.16   944.5 1664.07  997.931669.796
  1032.6 1673.13  1052.2 1674.18  1081.5 1674.84  1117.31674.422    1150  1673.2
#Mann= 5 ,-1 , 0
       0     .12       0   426.2    .045       0   453.1     .12       0
  997.93     .06       0  1117.3     .12       0
Bank Sta=426.2,453.1
XS Rating Curve= 0 ,0
Exp/Cntr=0.3,0.1

Type RM Length L Ch R = 1 ,44068.2 ,355.4,337.5,319.2
XS GIS Cut Line= 2
     1846565.722      214748.927     1847047.493      215660.386
#Sta/Elev= 30
       0 1670.56    19.6 1664.22    58.9 1653.97    88.4 1644.57   117.8 1643.03
   127.6 1641.92   157.1  1636.1   186.6  1627.9   225.8  1615.1   274.9 1602.55
     324 1588.22   373.1  1579.4   392.7 1574.17   402.6 1571.28   412.4 1569.31
   422.2 1570.05   430.7 1572.85   441.8 1576.36   451.6 1577.86   490.9  1577.2
   510.6 1578.43     540 1584.74   569.5 1591.93   667.7  1620.6   775.7 1638.63
   844.4  1652.5   942.6 1667.77   981.9 1672.91  1001.5 1674.42    1031 1674.76
#Mann= 3 ,-1 , 0
       0     .12       0   392.7    .045       0   430.7     .12       0
Bank Sta=392.7,430.7
XS Rating Curve= 0 ,0
Exp/Cntr=0.3,0.1

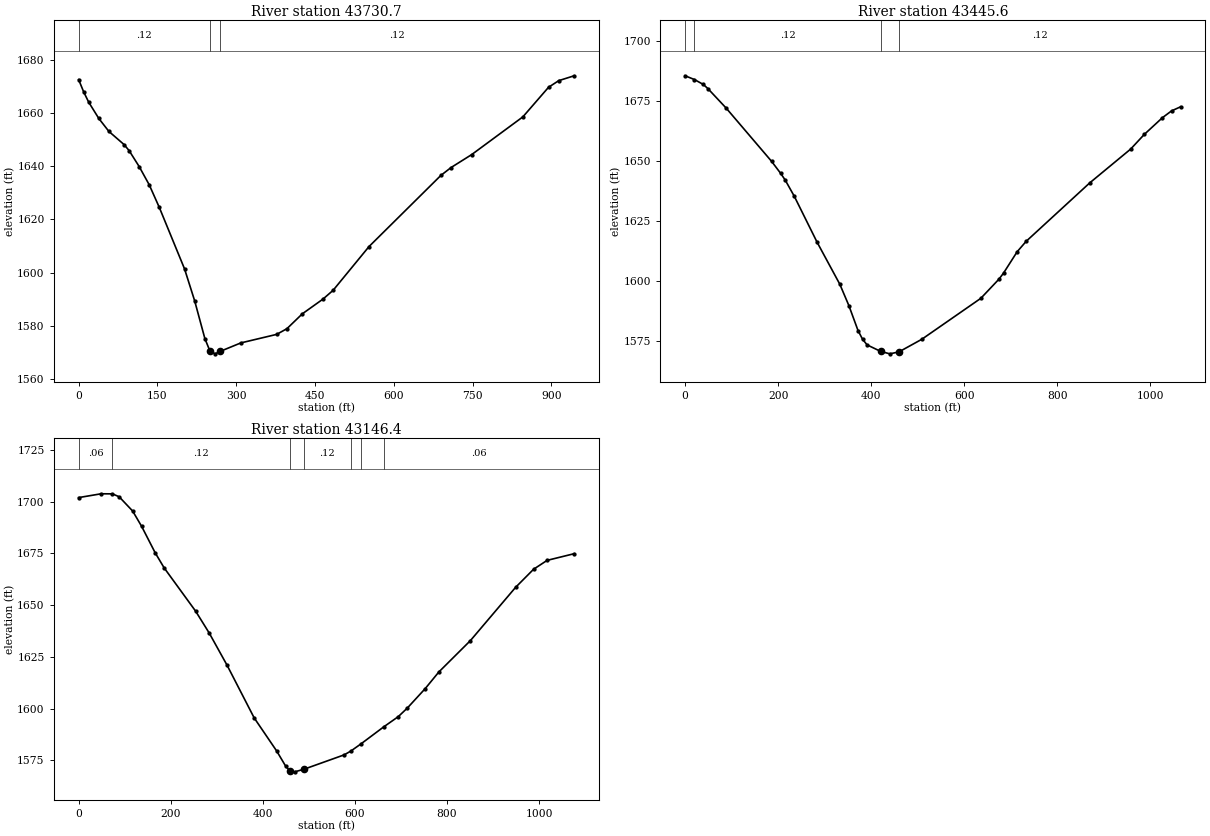
Type RM Length L Ch R = 1 ,43730.7 ,295.6,285.1,273.7
XS GIS Cut Line= 3
     1846239.324      215134.903      1846432.91      215241.115
      1847026.66      215652.573
#Sta/Elev= 30
       0 1672.48     9.6 1667.86    19.2 1663.98    38.4 1657.88    57.6 1653.02
    86.4 1648.09      96 1645.84   115.2 1639.83   134.4 1632.96   153.6 1624.46
   201.6 1601.39   220.8 1589.44   240.3 1575.22     250 1570.53   259.9  1569.5
   269.6 1570.44   308.7  1573.6     377 1576.81   396.5 1578.95   425.8 1584.53
   464.9 1590.03   484.4 1593.36   552.7 1609.78   689.4 1636.48   708.9 1639.46
     748  1644.3   845.6 1658.49   894.4 1669.59   913.9 1672.09   943.2 1673.91
#Mann= 3 ,-1 , 0
       0     .12       0     250    .045       0   269.6     .12       0
Bank Sta=250,269.6
XS Rating Curve= 0 ,0
Exp/Cntr=0.3,0.1

Type RM Length L Ch R = 1 ,43445.6 ,292.8,299.2,305.6
XS GIS Cut Line= 3
     1845989.207      215387.074     1846529.264      215561.427
     1847016.243      215665.594
#Sta/Elev= 30
       0 1685.34   20.211683.759    39.1 1681.73    48.9 1680.02    88.1 1671.91
   185.9 1649.69   205.5 1644.66   215.3 1641.86   234.8 1635.11   283.8 1615.97
   332.7 1598.44   352.2 1589.53   371.8 1579.16   381.6 1575.52   391.4 1573.16
   420.7 1570.44   440.3 1569.44   459.9 1570.26   508.8 1575.49   635.9 1592.59
   674.9 1600.58   684.7  1603.1     714    1612   733.5 1616.37   870.2 1640.72
   958.1  1654.8   987.4 1660.91  1026.4 1667.88    1046 1670.71  1065.5 1672.42
#Mann= 4 ,-1 , 0
       0     .06       0   20.21     .12       0   420.7    .045       0
   459.9     .12       0
Bank Sta=420.7,459.9
XS Rating Curve= 0 ,0
Exp/Cntr=0.3,0.1

Type RM Length L Ch R = 1 ,43146.4 ,316.1,323.7,330.5
XS GIS Cut Line= 3
     1845880.827      215582.261     1846435.514      215871.323
     1846664.681      216259.344
#Sta/Elev= 30
       0 1701.93    48.9 1703.77   73.451703.729      88 1702.32   117.3 1695.44
   136.8 1688.04   166.2 1675.28   185.7 1667.98   254.1 1647.06   283.4 1636.57
   322.5 1620.89   381.2 1595.52     430 1579.55   449.6  1572.2   459.3 1569.78
   469.1 1569.46   488.7 1570.67   576.6 1577.66   590.91579.461  612.631582.882
  662.271591.138   694.1 1596.12   713.7 1600.25   752.8 1609.71   782.2 1617.69
   850.8 1632.86   948.8 1658.55     988 1667.33  1017.4 1671.61  1076.1 1674.83
#Mann= 7 ,-1 , 0
       0     .06       0   73.45     .12       0   459.3    .045       0
   488.7     .12       0   590.9     .06       0  612.63     .12       0
  662.27     .06       0
Bank Sta=459.3,488.7
XS Rating Curve= 0 ,0
Exp/Cntr=0.3,0.1