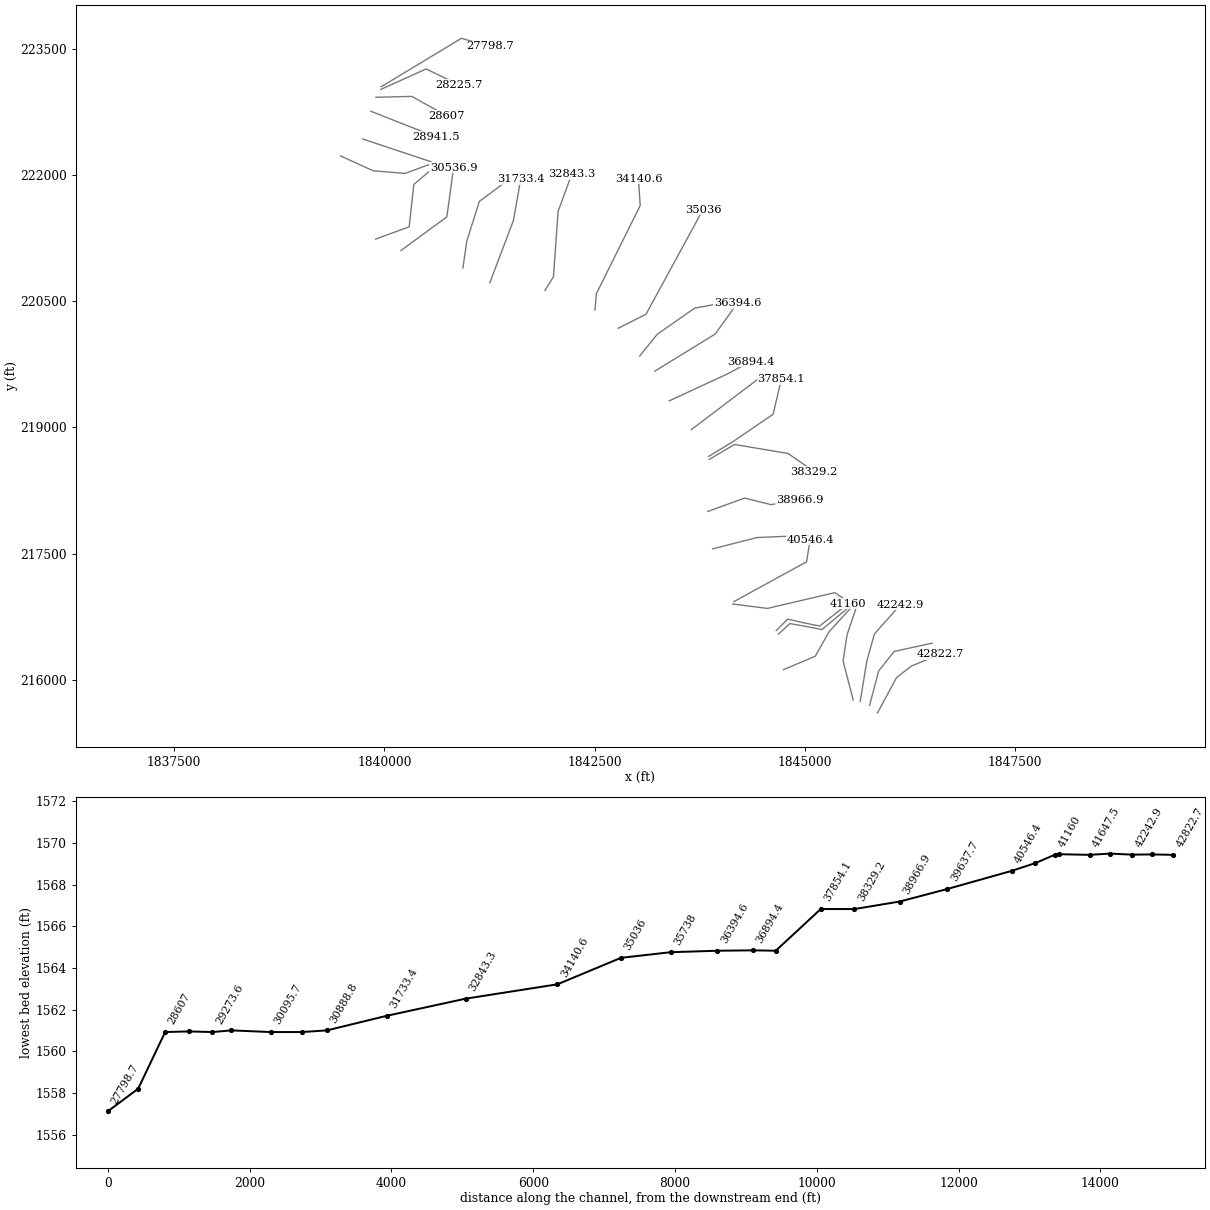
HEC-RAS study SUGARCK.prj: SUGARCK

--- SUGARCK.g01 (geometry) --- (continued)

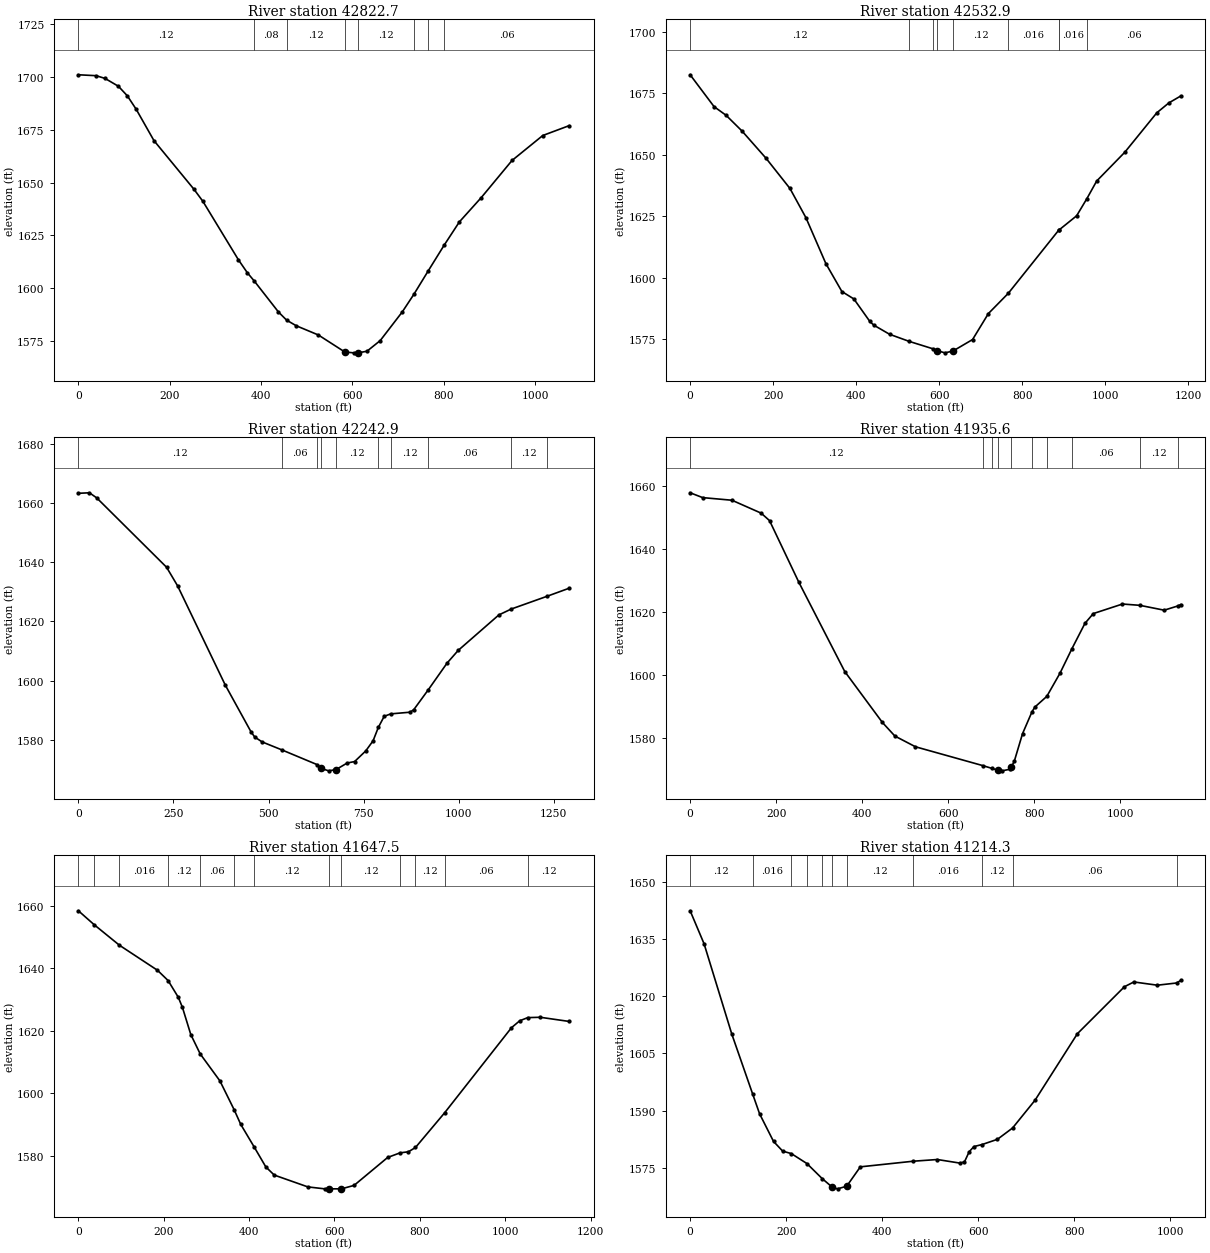
Type RM Length L Ch R = 1 ,42822.7 ,279.9,289.9,298.5
XS GIS Cut Line= 4
     1845862.597      215603.094     1846088.657      216023.006
     1846263.639      216160.386     1846609.993      216303.615
#Sta/Elev= 30
       0 1701.06    38.9 1700.63    58.4 1699.33    87.6 1695.62   107.1 1691.11
   126.5 1684.74   165.4  1669.9     253 1646.86   272.5 1641.16   350.4 1613.44
   369.8 1607.35  385.031603.414     438 1588.75  455.811584.907   476.9 1582.25
   525.3 1577.88   583.3 1569.82   602.6 1569.43   612.3 1569.44   631.7 1570.19
   660.7 1575.23     709 1588.81  734.33 1597.12  766.221608.386   800.61620.379
   833.9  1631.4     882 1642.96   949.2 1660.49  1016.5 1672.31  1074.2 1676.97
#Mann= 8 ,-1 , 0
       0     .12       0  385.03     .08       0  455.81     .12       0
   583.3    .045       0   612.3     .12       0  734.33     .06       0
  766.22     .12       0   800.6     .06       0
Bank Sta=583.3,612.3
XS Rating Curve= 0 ,0
Exp/Cntr=0.3,0.1

Type RM Length L Ch R = 1 ,42532.9 ,274.3,289.9,305.1
XS GIS Cut Line= 4
     1845768.847       215694.24     1845876.995       216103.53
     1846060.514      216334.865     1846513.639      216433.823
#Sta/Elev= 30
       0 1682.51    57.7 1669.54    86.6 1666.04   125.1 1659.62   182.8 1648.58
   240.5 1636.28     279 1624.39   327.1 1605.71   365.6 1594.38   394.5 1591.36
   432.9 1582.23   442.4 1580.72   480.5    1577  527.36 1574.13   585.3 1571.08
   594.8 1570.36   613.8 1569.45   632.9 1570.15   680.5 1574.86   718.6 1585.42
  766.611593.662  887.561619.221  887.821619.268   931.2 1625.17     956 1632.17
   979.5  1639.3  1047.2    1651  1124.4 1667.05  1153.4 1671.07  1182.4 1673.92
#Mann= 9 ,-1 , 0
       0     .12       0  527.36     .06       0   585.3     .12       0
   594.8    .045       0   632.9     .12       0  766.61    .016       0
  887.56     .12       0  887.82    .016       0     956     .06       0
Bank Sta=594.8,632.9
XS Rating Curve= 0 ,0
Exp/Cntr=0.3,0.1

Type RM Length L Ch R = 1 ,42242.9 ,302.4,307.4,311.6
XS GIS Cut Line= 4
     1845656.868      215738.511     1845734.993      216215.073
     1845826.139      216543.198     1846136.035      216892.157
#Sta/Elev= 30
       0 1663.38      29 1663.56    48.3 1661.82   231.8 1638.36   260.8 1632.06
   386.3 1598.44     454 1582.61   463.6 1580.88   482.9 1579.24  534.761576.539
  627.251571.565   638.6 1570.25   658.1 1569.44   677.5 1569.87   706.7 1572.09
   726.2 1572.58   755.4 1576.17   774.8 1579.61  788.571584.144     804 1587.89
  821.12 1588.72   872.1 1589.29   881.8 1590.15  920.181596.929   969.3 1605.91
   998.5  1610.2  1105.4 1622.21 1137.841624.197 1231.741628.507  1290.2 1631.25
#Mann= 10 ,-1 , 0
       0     .12       0  534.76     .06       0  627.25     .12       0
   638.6    .045       0   677.5     .12       0  788.57    .016       0
  821.12     .12       0  920.18     .06       0 1137.84     .12       0
 1231.74     .06       0
Bank Sta=638.6,677.5
XS Rating Curve= 0 ,0
Exp/Cntr=0.3,0.1

Type RM Length L Ch R = 1 ,41935.6 ,301.4,288.1,273.9
XS GIS Cut Line= 4
     1845573.535      215759.344     1845453.743      216220.282
     1845500.618      216532.782     1845612.597      216863.511
#Sta/Elev= 30
       0  1657.9    29.2 1656.36    97.2 1655.53   165.2 1651.42   184.7 1649.04
   252.7 1629.48   359.6 1601.07   447.1 1584.88   476.2 1580.55   524.1 1577.14
  680.191571.172  701.631570.285   715.6 1569.69   725.2 1569.49   744.4 1570.01
   747.4 1570.81   753.9 1572.53   773.1  1581.3  795.021588.241   801.9 1589.78
  829.551593.165   860.1  1600.5  888.181608.374   918.3 1616.39   937.7 1619.49
  1005.6 1622.53 1045.951622.114  1102.6 1620.57 1134.191621.909  1141.4 1622.37
#Mann= 10 ,-1 , 0
       0     .12       0  680.19     .06       0  701.63     .12       0
   715.6    .045       0   747.4     .12       0  795.02    .016       0
  829.55     .12       0  888.18     .06       0 1045.95     .12       0
 1134.19     .06       0
Bank Sta=715.6,747.4
XS Rating Curve= 0 ,0
Exp/Cntr=0.3,0.1

Type RM Length L Ch R = 1 ,41647.5 ,479.4,433.2,372.6
XS GIS Cut Line= 4
      1844745.41      216118.719     1845123.014      216277.573
     1845287.077       216569.24     1845560.514      216868.719
#Sta/Elev= 30
       0 1658.33   37.381653.832   96.161647.314   185.3 1639.31  210.181636.023
   234.1 1630.67   243.8 1627.43   263.4 1618.75  285.36 1612.58   331.6 1603.94
  364.911594.728   380.4 1590.04  412.411582.686   439.2 1576.43   458.9 1573.83
   537.6 1570.05     577 1569.43   586.8 1569.43   616.4 1569.43   645.9 1570.53
   724.6 1579.46   753.61580.932   773.3 1581.28   789.81582.648  858.061593.734
  1014.7 1620.94    1034 1623.16 1052.921624.175  1082.2 1624.28  1149.8 1622.95
#Mann= 13 ,-1 , 0
       0    .016       0   37.38     .06       0   96.16    .016       0
  210.18     .12       0  285.36     .06       0  364.91    .016       0
  412.41     .12       0   586.8    .045       0   616.4     .12       0
   753.6    .016       0   789.8     .12       0  858.06     .06       0
 1052.92     .12       0
Bank Sta=586.8,616.4
XS Rating Curve= 0 ,0
Exp/Cntr=0.3,0.1

Type RM Length L Ch R = 1 ,41214.3 ,57.5,54.4,53.7
XS GIS Cut Line= 5
     1844686.382      216541.462     1844820.497      216666.462
     1845007.997       216633.91     1845202.007      216594.848
     1845548.361      216883.476
#Sta/Elev= 30
       0 1642.39      29 1633.74    86.8 1610.04  130.221594.336   144.7 1589.13
   173.7  1581.9   192.8 1579.35  210.831578.702   243.31576.092   275.21572.135
   296.4 1569.86     307 1569.46   326.1 1570.14   354.6 1575.23  465.23 1576.71
     515 1577.15   562.1 1576.21   571.5 1576.52   581.3 1579.18   591.2 1580.55
  608.381581.086   640.2 1582.45  671.721585.413   718.6 1592.71   806.8 1610.15
   904.8 1622.47   924.4 1623.72   973.4 1622.87 1013.49 1623.45  1022.4 1624.15
#Mann= 11 ,-1 , 0
       0     .12       0  130.22    .016       0  210.83     .12       0
   243.3    .016       0   275.2     .12       0   296.4    .045       0
   326.1     .12       0  465.23    .016       0  608.38     .12       0
  671.72     .06       0 1013.49     .12       0
Bank Sta=296.4,326.1
XS Rating Curve= 0 ,0
Exp/Cntr=0.3,0.1

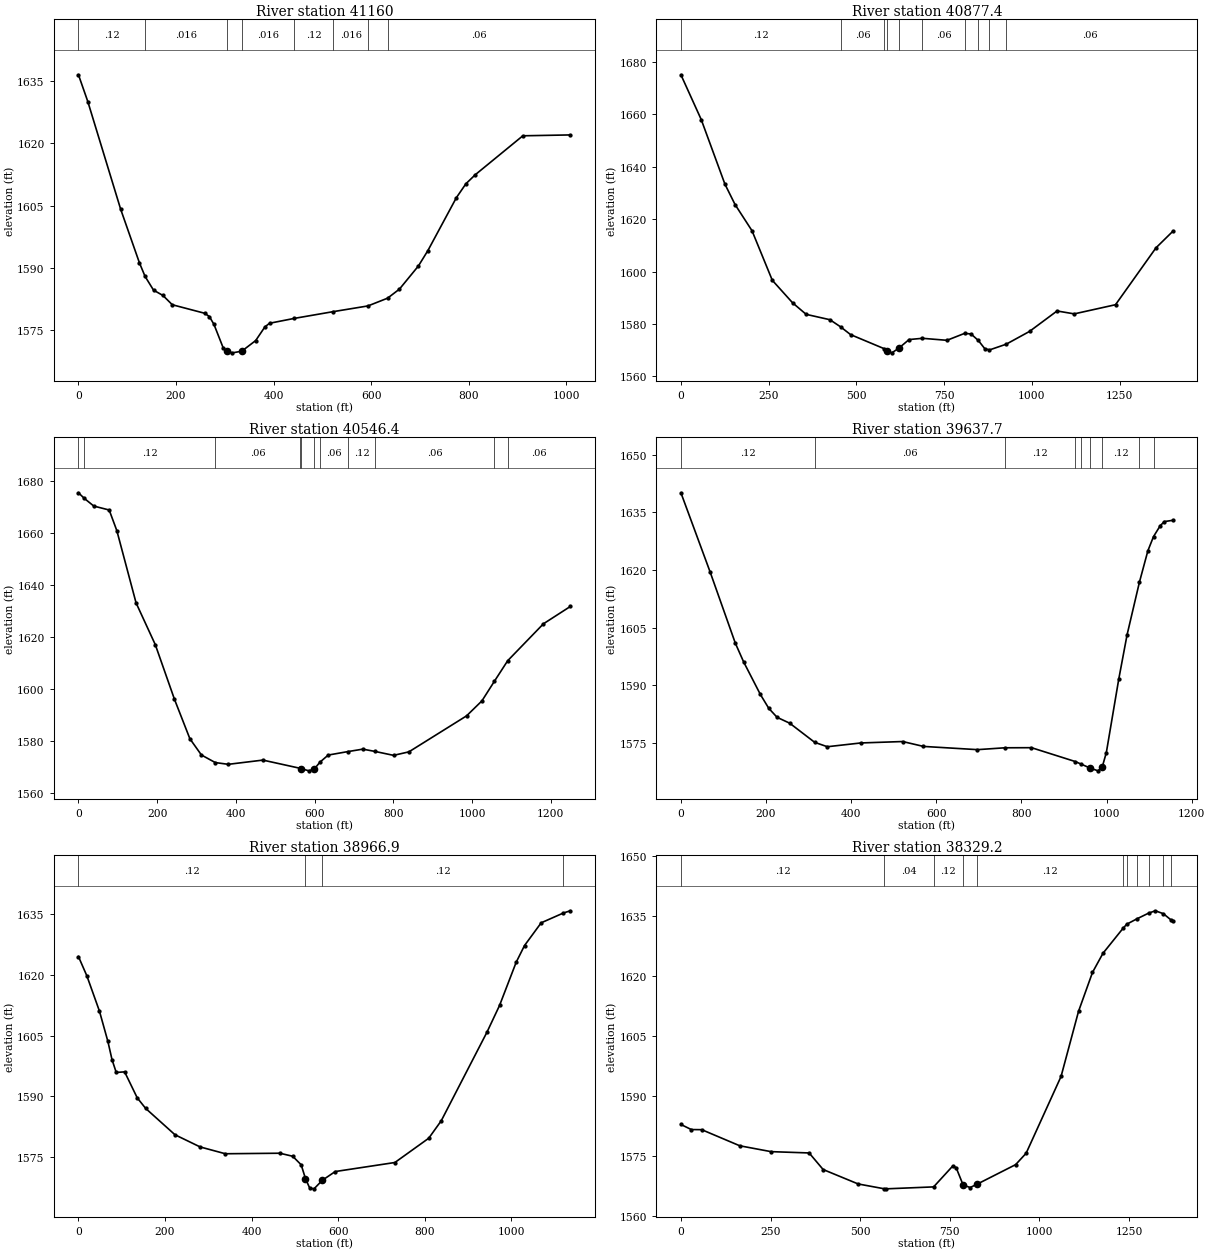
Type RM Length L Ch R = 1 ,41160   ,259.3,282.6,306.5
XS GIS Cut Line= 5
     1844659.038      216584.431     1844795.757      216719.848
     1844980.653      216676.879     1845174.663      216637.816
     1845511.903      216901.705
#Sta/Elev= 30
       0 1636.57    19.2  1630.1    86.6 1604.09   125.1 1591.14  136.591587.889
   153.9 1584.58   173.2 1583.29   192.4 1581.05   258.9 1578.99   268.4  1578.2
   277.8 1576.31   296.8 1570.62   304.2 1569.82   315.8 1569.44   334.8 1569.84
   363.3  1572.4   382.2  1575.7   391.7 1576.58  442.541577.758  522.221579.385
  593.461580.765  633.651582.632     658 1584.82   696.9 1590.41   716.4 1594.14
   774.8 1606.91   794.3 1610.26   813.7 1612.46     911 1621.84  1008.4 1622.05
#Mann= 8 ,-1 , 0
       0     .12       0  136.59    .016       0   304.2    .045       0
   334.8    .016       0  442.54     .12       0  522.22    .016       0
  593.46     .12       0  633.65     .06       0
#XS Ineff= 2 , 0
       0                     393       0
Permanent Ineff=
       F       F
Bank Sta=304.2,334.8
XS Rating Curve= 0 ,0
Exp/Cntr=0.3,0.1

Type RM Length L Ch R = 1 ,40877.4 ,319.9,331,341.9
XS GIS Cut Line= 4
     1844142.111      216899.101      1844553.57      216847.018
     1845355.653      217034.518      1845491.07      216943.372
#Sta/Elev= 30
       0 1675.16    57.9 1658.06   125.4 1633.42   154.3 1625.63   202.6 1615.63
   260.4 1596.72   318.3 1588.11   356.9 1583.72   424.6 1581.67  455.261578.928
   483.4 1575.99  578.891570.633   586.9  1569.9   601.1 1569.03   620.7 1570.79
   650.1  1574.1  688.161574.579     758 1573.81   808.11576.447   826.6 1576.25
   847.51573.741   865.8 1570.63  879.28 1570.14  926.821572.322   993.3  1577.2
  1071.8 1585.01  1120.8  1583.9  1238.4  1587.4  1353.7 1609.11  1401.7 1615.42
#Mann= 10 ,-1 , 0
       0     .12       0  455.26     .06       0  578.89     .12       0
   586.9    .045       0   620.7     .12       0  688.16     .06       0
   808.1     .12       0   847.5     .06       0  879.28    .016       0
  926.82     .06       0
Bank Sta=586.9,620.7
XS Rating Curve= 0 ,0
Exp/Cntr=0.3,0.1

Type RM Length L Ch R = 1 ,40546.4 ,923.9,908.7,874.1
XS GIS Cut Line= 3
     1844155.132      216927.747     1845019.716      217401.705
     1845061.382      217662.122
#Sta/Elev= 30
       0 1675.33   14.881673.177      39 1670.23    78.1 1668.72    97.6 1660.76
   146.4 1633.08   195.2 1617.08     244 1596.08   283.1 1580.97   312.4 1574.74
  347.611571.836   380.7 1571.16   468.6 1572.78  563.031569.638   566.2 1569.48
   585.7 1568.66   599.2 1569.36  613.481571.982   634.5 1574.71   684.41576.041
   722.4 1576.98  753.591576.102   800.5  1574.6   839.5 1575.94     986 1589.75
    1025 1595.49 1056.661603.004 1090.57 1610.92  1181.3 1625.07  1249.7 1631.72
#Mann= 11 ,-1 , 0
       0     .06       0   14.88     .12       0  347.61     .06       0
  563.03     .12       0   566.2    .045       0   599.2     .12       0
  613.48     .06       0   684.4     .12       0  753.59     .06       0
 1056.66    .016       0 1090.57     .06       0
Bank Sta=566.2,599.2
XS Rating Curve= 0 ,0
Exp/Cntr=0.3,0.1

Type RM Length L Ch R = 1 ,39637.7 ,681,670.8,638.9
XS GIS Cut Line= 3
     1843902.528      217555.351     1844426.134      217689.563
     1845040.549      217716.809
#Sta/Elev= 30
       0 1640.09    68.8 1619.44   127.8 1600.99   147.4  1596.1   186.7 1587.64
   206.4 1584.04     226  1581.7   255.5 1580.18  314.331575.195     344 1574.06
   422.6 1575.04   520.9 1575.41   569.8 1574.14   696.7  1573.3  761.191573.784
   823.6 1573.81  926.36 1570.21  939.75 1569.56   960.3 1568.56   979.8 1567.79
   989.6 1568.72   999.4 1572.53  1028.6 1591.65  1048.2  1603.2 1077.161616.852
    1097 1625.01 1110.29 1628.71  1126.3 1631.58    1136 1632.61  1155.6 1632.93
#Mann= 9 ,-1 , 0
       0     .12       0  314.33     .06       0  761.19     .12       0
  926.36     .06       0  939.75     .12       0   960.3    .045       0
   989.6     .12       0 1077.16    .016       0 1110.29     .06       0
Bank Sta=960.3,989.6
XS Rating Curve= 0 ,0
Exp/Cntr=0.3,0.1

Type RM Length L Ch R = 1 ,38966.9 ,634.6,637.7,661.6
XS GIS Cut Line= 4
     1843845.236      218000.663     1844282.736      218159.518
     1844597.841      218081.393     1844938.986      218141.288
#Sta/Elev= 30
       0 1624.52    19.4 1619.77    48.5 1611.06    67.9 1603.62    77.6 1599.06
    87.3 1595.92   106.7 1596.06   135.8 1589.65   155.2 1587.05     223 1580.54
   281.2 1577.53   339.4 1575.85   465.4 1575.98     495 1575.23   514.6 1573.12
   524.5 1569.72   534.3 1567.38   544.2 1567.19   563.8 1569.33   593.3 1571.46
   731.1 1573.69   809.3 1579.68   838.2 1583.99     944 1605.89   972.9 1612.45
  1011.4 1623.13  1030.6 1627.24  1069.1 1632.85 1120.471635.273  1136.5 1635.82
#Mann= 4 ,-1 , 0
       0     .12       0   524.5    .045       0   563.8     .12       0
 1120.47    .016       0
Bank Sta=524.5,563.8
XS Rating Curve= 0 ,0
Exp/Cntr=0.3,0.1

Type RM Length L Ch R = 1 ,38329.2 ,451.9,475.1,503.3
XS GIS Cut Line= 4
     1843863.466      218620.455     1844162.945      218797.538
     1844798.361      218690.768     1845110.861      218474.622
#Sta/Elev= 30
       0 1582.92      29 1581.65      58 1581.62   164.3 1577.59   251.3 1576.13
   357.7  1575.8   396.7 1571.66   494.4 1568.05  567.761566.835   572.4 1566.83
  704.911567.316   757.9  1572.5   767.7 1572.14   787.2  1567.8   806.8 1567.16
   826.3    1568   933.7 1572.88     963 1575.73  1060.4 1594.92  1109.2 1611.21
  1148.1 1620.93  1177.4 1625.72 1233.091631.929 1243.681632.982 1271.591634.305
 1304.571635.746  1323.5 1636.34 1345.831635.608 1368.29 1633.97  1372.2 1633.66
#Mann= 11 ,-1 , 0
       0     .12       0  567.76     .04       0  704.91     .12       0
   787.2    .045       0   826.3     .12       0 1233.09     .06       0
 1243.68     .12       0 1271.59     .06       0 1304.57    .016       0
 1345.83     .12       0 1368.29     .06       0
Bank Sta=787.2,826.3
XS Rating Curve= 0 ,0
Exp/Cntr=0.3,0.1

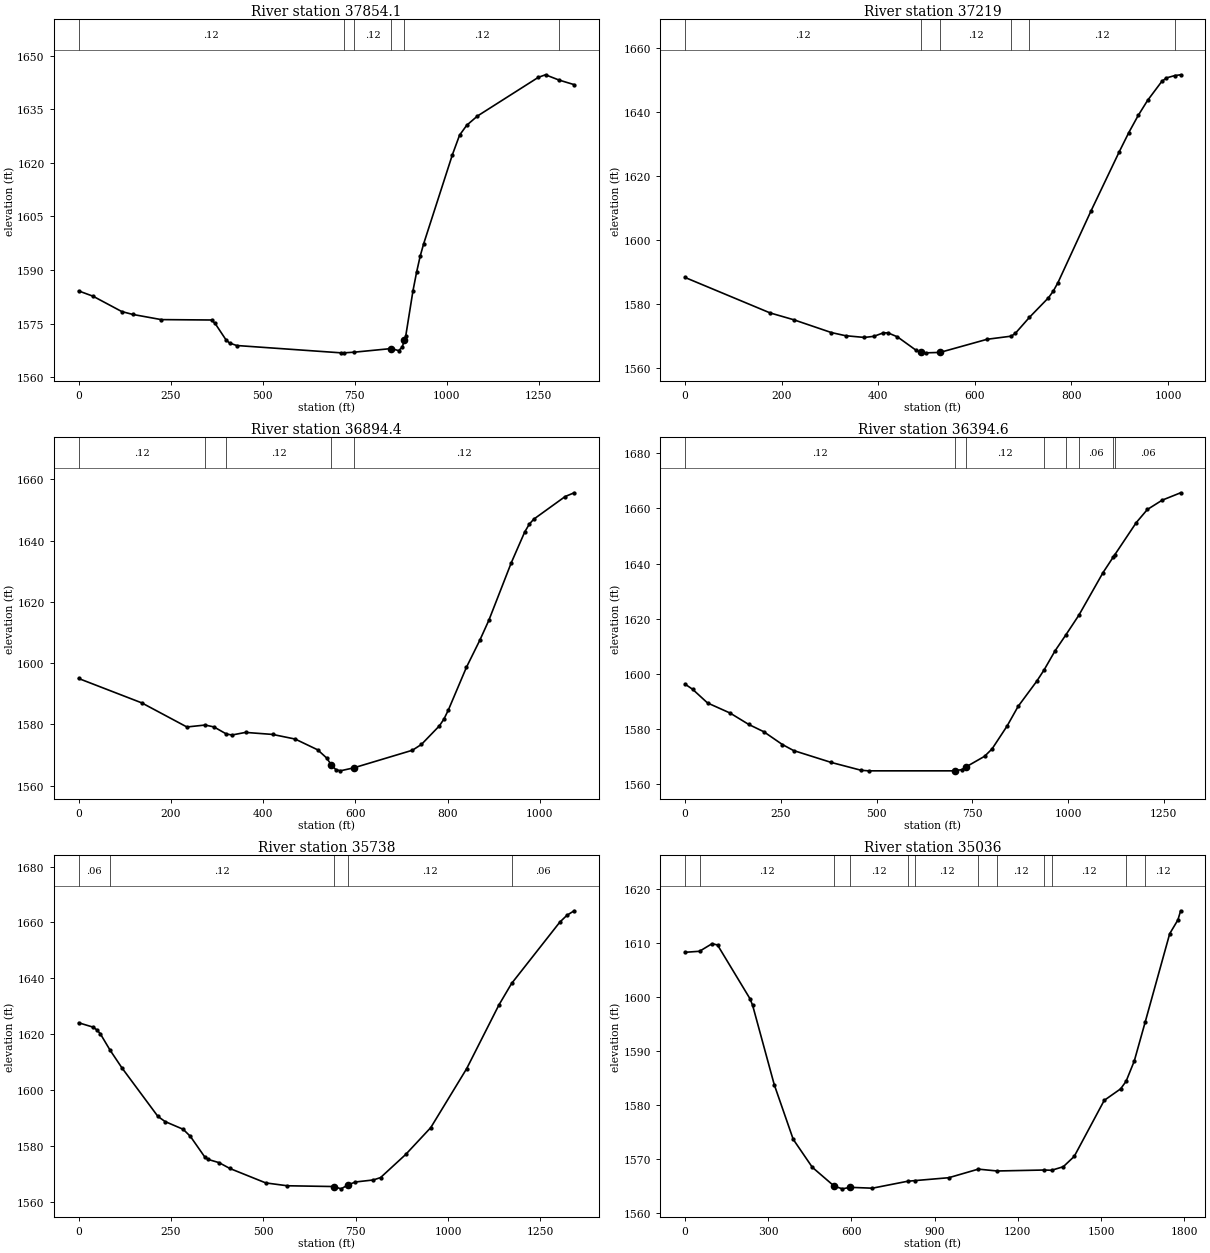
Type RM Length L Ch R = 1 ,37854.1 ,625.6,635.1,635.2
XS GIS Cut Line= 4
     1843853.049      218654.309     1844136.903      218826.184
     1844621.278      219156.913     1844720.236       219573.58
#Sta/Elev= 30
       0 1584.16      39 1582.68   117.1 1578.39   146.4 1577.59   224.5 1576.13
   361.2 1576.02   370.9 1575.05   400.3 1570.49     410 1569.58   429.6 1568.88
   713.1 1566.83  720.88 1566.83  748.441567.009   849.9 1568.03   869.5 1567.45
   879.2  1568.4   885.4 1570.42     889  1571.6   908.6 1584.22   918.4  1589.4
   928.1 1593.87   937.8 1597.42  1015.7 1622.28  1035.2 1627.75  1054.6 1630.51
  1083.8  1633.1  1249.3 1643.93  1268.7 1644.64 1305.461643.161  1346.6 1641.88
#Mann= 6 ,-1 , 0
       0     .12       0  720.88     .04       0  748.44     .12       0
   849.9    .045       0   885.4     .12       0 1305.46     .06       0
Bank Sta=849.9,885.4
XS Rating Curve= 0 ,0
Exp/Cntr=0.3,0.1

Type RM Length L Ch R = 1 ,37219   ,329.8,324.6,320.4
XS GIS Cut Line= 2
     1843649.924      218974.622     1844467.632      219594.413
#Sta/Elev= 30
       0 1588.32   175.9 1577.28   224.8 1575.15   302.9 1571.15   332.2 1570.17
   371.3 1569.63   390.9 1569.98   410.4 1571.06   420.2 1571.05   439.7 1569.81
   478.8 1565.57   488.6 1564.97   498.4 1564.83   527.7 1564.96   625.4 1569.06
  675.461570.034     684 1570.95     7131575.906   752.4 1582.01   762.2 1584.05
     772 1586.72   840.4 1609.06     899 1627.55   918.6 1633.48   938.1 1638.83
   957.6 1643.54     987 1649.45   996.7 1650.55 1014.091651.278    1026 1651.52
#Mann= 6 ,-1 , 0
       0     .12       0   488.6    .045       0   527.7     .12       0
  675.46     .04       0     713     .12       0 1014.09     .06       0
Bank Sta=488.6,527.7
XS Rating Curve= 0 ,0
Exp/Cntr=0.3,0.1

Type RM Length L Ch R = 1 ,36894.4 ,494.7,499.9,504.1
XS GIS Cut Line= 3
     1843386.586      219316.259     1844087.424      219641.288
     1844353.049      219784.518
#Sta/Elev= 30
       0 1594.98   136.9 1587.02   234.7 1579.16  274.331579.793   293.4 1579.17
  320.391576.864   332.5 1576.54   361.8 1577.39   420.5 1576.73   469.4 1575.22
   518.3  1571.7   537.8 1569.03   547.6 1566.81   557.4 1565.28   567.2 1564.85
   596.5 1565.83   723.6 1571.57   743.2 1573.47   782.3 1579.56     792 1581.75
   801.7 1584.75   840.7 1598.62   869.9 1607.51   889.4    1614     938 1632.76
   967.2 1642.81     977 1645.33   986.7 1646.96  1054.8 1654.35  1074.3 1655.57
#Mann= 5 ,-1 , 0
       0     .12       0  274.33     .06       0  320.39     .12       0
   547.6    .045       0   596.5     .12       0
Bank Sta=547.6,596.5
XS Rating Curve= 0 ,0
Exp/Cntr=0.3,0.1

Type RM Length L Ch R = 1 ,36394.6 ,653.9,656.6,656.7
XS GIS Cut Line= 3
     1843215.028      219669.934     1843931.174      220110.038
     1844196.799      220477.226
#Sta/Elev= 30
       0 1596.26    19.6  1594.4    58.6 1589.44   117.3 1585.79   166.2 1581.65
   205.3 1579.02   254.1 1574.36   283.4 1572.18   381.2 1567.89   459.4 1565.04
   478.9 1564.83   703.7 1564.83   722.7 1565.29     733 1566.22   781.9  1570.1
   801.5 1572.79   840.6 1581.06   869.5  1588.2   917.7 1597.24  937.491601.461
   965.9 1608.33  994.681614.235 1028.051621.249  1091.3 1636.73 1117.47 1642.26
 1121.631643.118    1178 1654.84    1207 1659.59  1245.6 1662.96  1293.8 1665.64
#Mann= 8 ,-1 , 0
       0     .12       0   703.7    .045       0     733     .12       0
  937.49     .06       0  994.68     .12       0 1028.05     .06       0
 1117.47     .12       0 1121.63     .06       0
Bank Sta=703.7,733
XS Rating Curve= 0 ,0
Exp/Cntr=0.3,0.1

Type RM Length L Ch R = 1 ,35738   ,632.6,701.9,714.9
XS GIS Cut Line= 4
     1843035.341      219849.622     1843243.307      220107.958
     1843688.986      220419.934      1844147.32      220503.268
#Sta/Elev= 30
       0 1624.14      39 1622.58    48.8 1621.65    58.5 1620.25   85.05 1614.36
     117 1608.05   214.6 1590.66   234.1 1588.81   282.9 1586.06   302.4 1583.54
   341.4 1576.16   351.1 1575.26   380.2 1574.12   409.4 1572.04   506.5 1566.88
   564.8 1565.86   691.1 1565.58   710.5 1564.76     730 1566.23   749.4 1567.21
     798 1567.94   817.4 1568.79   885.4 1577.05   953.3 1586.66  1050.4 1607.72
  1137.7 1630.49 1172.091638.187  1302.7 1660.13  1322.1 1662.59  1341.5 1664.18
#Mann= 5 ,-1 , 0
       0     .06       0   85.05     .12       0   691.1    .045       0
     730     .12       0 1172.09     .06       0
Bank Sta=691.1,730
XS Rating Curve= 0 ,0
Exp/Cntr=0.3,0.1

Type RM Length L Ch R = 1 ,35036   ,861.4,895.5,899.6
XS GIS Cut Line= 3
     1842780.132      220180.351     1843110.861      220347.018
     1843787.945      221591.809
#Sta/Elev= 30
       0 1608.31   52.021608.497    97.5 1609.91     117 1609.66   233.9 1599.72
   243.6 1598.48   321.6 1583.78     390 1573.66   458.9 1568.48   537.6    1565
   567.2 1564.49   594.6 1564.77   675.4 1564.61  802.451565.893  827.85 1566.01
   950.9 1566.55 1057.62 1568.14 1125.471567.798 1294.421567.976 1321.96 1567.93
  1364.2 1568.59  1403.6  1570.5  1511.8 1580.88  1570.9 1583.01 1590.611584.411
  1620.1 1588.16 1659.411595.362    1748 1611.76  1777.5  1614.3  1787.4    1616
#Mann= 12 ,-1 , 0
       0     .06       0   52.02     .12       0   537.6    .045       0
   594.6     .12       0  802.45     .04       0  827.85     .12       0
 1057.62     .06       0 1125.47     .12       0 1294.42     .06       0
 1321.96     .12       0 1590.61     .06       0 1659.41     .12       0
#XS Ineff= 2 , 0
       0                    1260       0
Permanent Ineff=
       F       F
Bank Sta=537.6,594.6
XS Rating Curve= 0 ,0
Exp/Cntr=0.3,0.1

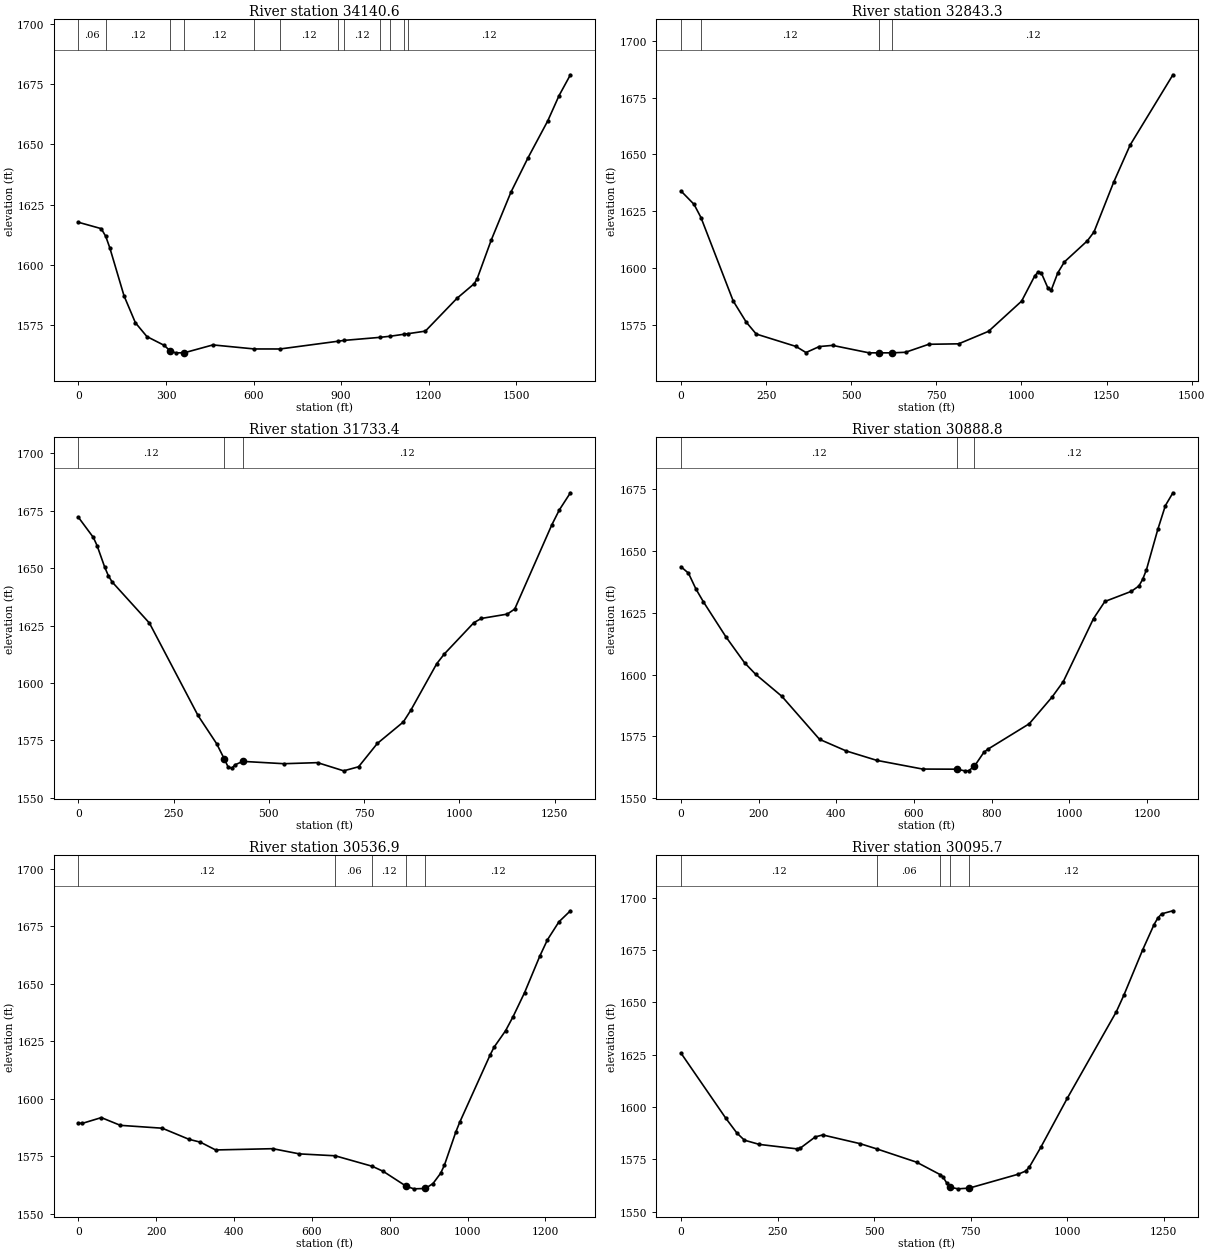
Type RM Length L Ch R = 1 ,34140.6 ,1229.4,1297.3,1312.9
XS GIS Cut Line= 4
     1842503.222      220397.365     1842520.584      220591.809
     1843041.417       221640.42     1843020.584      221959.865
#Sta/Elev= 30
       0  1617.6    78.1 1614.95   93.48 1611.75   107.4 1606.98   156.2 1586.98
   195.2 1575.75   234.6    1570   293.6 1566.36   313.3 1564.14     333 1563.22
   362.5 1563.24   460.9 1566.52  603.041564.836  690.771564.828  891.281568.082
  910.141568.399 1033.151569.668  1068.51570.136  1115.31570.953 1128.881571.185
    1189 1572.26  1297.2 1585.91  1356.2 1591.99    1366  1593.9  1414.6 1610.12
  1482.5 1630.18  1540.7 1644.42  1608.6 1659.85  1647.4  1670.4  1686.2 1679.04
#Mann= 12 ,-1 , 0
       0     .06       0   93.48     .12       0   313.3    .045       0
   362.5     .12       0  603.04     .06       0  690.77     .12       0
  891.28     .06       0  910.14     .12       0 1033.15     .06       0
  1068.5     .12       0  1115.3     .06       0 1128.88     .12       0
Bank Sta=313.3,362.5
XS Rating Curve= 0 ,0
Exp/Cntr=0.3,0.1

Type RM Length L Ch R = 1 ,32843.3 ,1112.9,1109.9,1070.4
XS GIS Cut Line= 4
     1841909.472      220630.004     1842010.167      220793.198
     1842065.722      221570.976     1842228.917       222015.42
#Sta/Elev= 30
       0 1633.88    38.4 1627.98   58.72 1622.17   153.4 1585.39   191.8 1576.04
     221 1570.82     338 1565.34   367.2 1562.66   406.2  1565.3   445.2 1565.82
   552.4 1562.53   581.6 1562.53   620.6 1562.53   659.6 1562.78   727.8  1566.3
   815.6  1566.5   903.3 1572.01  1000.5 1585.32  1039.2 1596.47  1048.8 1598.11
  1058.5  1597.7  1077.8  1591.1  1087.5 1590.16  1106.8 1597.78  1126.1 1602.59
  1193.8 1611.94  1213.1  1615.8    1271 1637.77  1319.4 1654.16    1445  1685.1
#Mann= 4 ,-1 , 0
       0     .06       0   58.72     .12       0   581.6    .045       0
   620.6     .12       0
Bank Sta=581.6,620.6
XS Rating Curve= 0 ,0
Exp/Cntr=0.3,0.1

Type RM Length L Ch R = 1 ,31733.4 ,839.8,844.5,844.5
XS GIS Cut Line= 3
     1841253.222      220720.282     1841534.472      221463.337
     1841621.278       221952.92
#Sta/Elev= 30
       0 1672.17    39.2  1663.4      49 1659.82    68.7 1650.58    78.5 1646.74
    88.3 1644.05   186.4 1626.09   313.9 1585.83   362.9 1573.52   382.5 1567.04
   392.4 1563.59   402.2 1562.85     412 1564.41   431.6 1565.83   539.5 1564.82
   627.8 1565.28   696.4 1561.71   735.6 1563.49   784.7 1573.64     853    1583
   872.5 1588.07   940.7 1608.39   960.2 1612.55  1038.2 1626.27  1057.7 1628.11
    1126 1630.01  1145.5 1632.22    1243 1668.94  1262.5 1675.38  1291.7 1682.88
#Mann= 3 ,-1 , 0
       0     .12       0   382.5    .045       0   431.6     .12       0
Bank Sta=382.5,431.6
XS Rating Curve= 0 ,0
Exp/Cntr=0.3,0.1

Type RM Length L Ch R = 1 ,30888.8 ,345.3,351.9,358.4
XS GIS Cut Line= 4
     1840933.778      220897.365     1840980.989      221221.227
     1841129.426      221689.977     1841489.334      221956.393
#Sta/Elev= 30
       0 1643.69    19.2  1641.1    38.5 1634.67    57.8 1629.46   115.5 1615.34
   163.6 1604.82   192.5 1600.08   259.9 1591.18   356.8 1573.77   425.6 1569.06
   504.3 1565.25   622.3 1561.73   710.8 1561.68   730.5 1561.01   740.6 1561.06
   755.6 1562.88   779.6 1568.44   789.5  1569.7   896.8 1580.08   955.3 1590.85
   984.5 1597.17  1062.3 1622.69  1091.5 1629.61  1159.7 1633.72  1179.2  1635.9
  1188.9 1638.59  1198.6 1642.48  1227.8 1658.79  1247.3 1668.44  1266.8 1673.65
#Mann= 3 ,-1 , 0
       0     .12       0   710.8    .045       0   755.6     .12       0
Bank Sta=710.8,755.6
XS Rating Curve= 0 ,0
Exp/Cntr=0.3,0.1

Type RM Length L Ch R = 1 ,30536.9 ,440.3,441.2,442.2
XS GIS Cut Line= 3
     1840197.667      221105.698     1840742.806      221505.004
     1840822.667      222088.337
#Sta/Elev= 30
       0 1589.51     9.8 1589.38    58.8 1591.89   107.7 1588.53   215.4 1587.28
     284 1582.46   313.4 1581.21   352.6 1577.83   499.5 1578.38     568 1576.12
  659.781575.296  755.281570.731   783.7  1568.5   842.6 1562.04   862.2 1560.93
   891.6 1561.09   911.2 1563.21   930.9 1567.69   940.7 1571.25   970.1 1585.71
   979.9 1589.83  1058.4 1619.22  1068.2 1622.48  1097.7 1629.61  1117.3 1635.82
  1146.8 1646.25    1186 1662.14  1205.6 1669.21  1235.1    1677  1264.5 1681.78
#Mann= 5 ,-1 , 0
       0     .12       0  659.78     .06       0  755.28     .12       0
   842.6    .045       0   891.6     .12       0
Bank Sta=842.6,891.6
XS Rating Curve= 0 ,0
Exp/Cntr=0.3,0.1

Type RM Length L Ch R = 1 ,30095.7 ,613.7,555.2,496
XS GIS Cut Line= 4
     1839895.584      221241.115     1840294.889      221386.948
     1840350.445       221890.42     1840610.861      222112.643
#Sta/Elev= 30
       0  1625.8   115.9 1594.72   144.9 1587.58   164.2 1584.19   202.9 1582.16
   299.5 1580.05   309.2 1580.41   347.8 1585.75   367.1 1586.69   464.1 1582.51
  508.171579.949   610.2 1573.67  670.961567.754   678.4 1566.63   688.1 1563.76
   697.8 1561.68   717.3 1560.93   746.6 1561.28   873.2 1567.91   892.7 1569.44
   902.4 1571.41   931.6 1580.71  1000.1 1604.12  1127.3 1645.53  1146.8 1653.42
  1195.7 1675.17  1225.1 1687.22  1234.8 1690.32  1244.6 1692.34    1274 1693.81
#Mann= 5 ,-1 , 0
       0     .12       0  508.17     .06       0  670.96     .12       0
   697.8    .045       0   746.6     .12       0
Bank Sta=697.8,746.6
XS Rating Curve= 0 ,0
Exp/Cntr=0.3,0.1

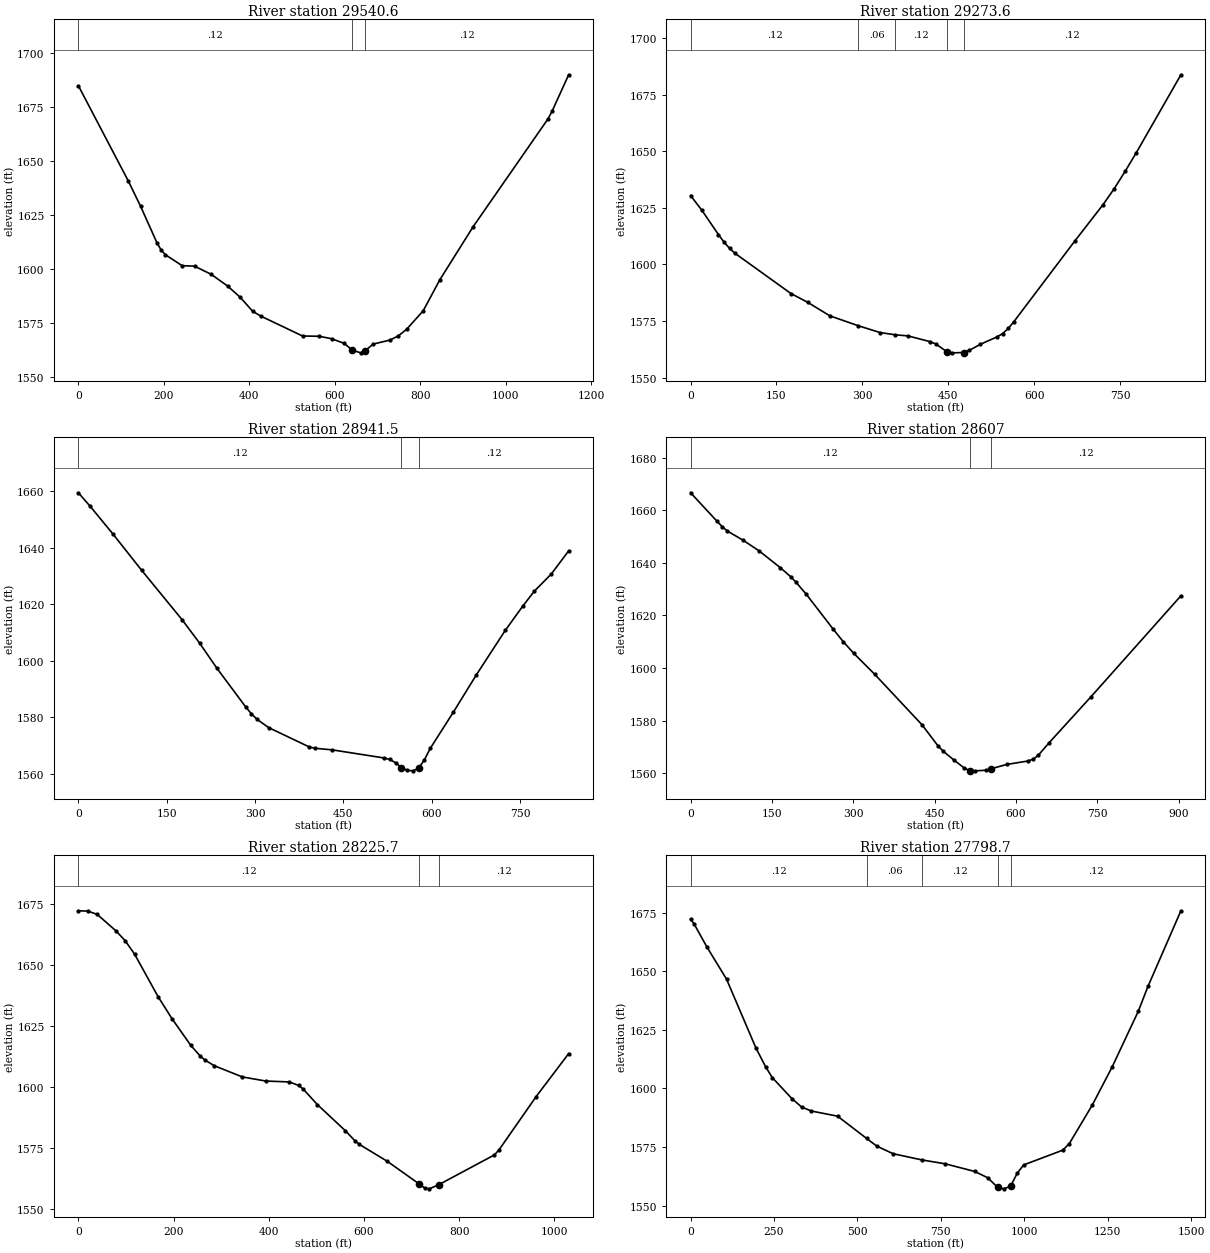
Type RM Length L Ch R = 1 ,29540.6 ,276.1,267,258
XS GIS Cut Line= 4
     1839478.917      222230.698     1839867.806      222053.615
     1840246.278      222022.365     1840565.722       222140.42
#Sta/Elev= 30
       0  1684.9   116.5 1640.85   145.7 1628.97   184.5 1611.78   194.2 1608.59
   203.9 1606.49   242.8 1601.44   271.9 1601.21   310.8 1597.43   349.6 1591.94
   378.8 1586.78   407.9  1580.3   427.3 1578.02   524.7 1568.82   563.6 1568.69
   592.8 1567.56   622.1  1565.4   641.5 1562.19     661 1561.01   670.8 1561.91
   690.2 1565.08   729.2 1566.93   748.6 1568.81   768.1 1571.89   807.1  1580.5
     846 1594.86   923.8 1619.44    1099 1669.43  1108.7 1673.01  1147.6 1689.96
#Mann= 3 ,-1 , 0
       0     .12       0   641.5    .045       0   670.8     .12       0
Bank Sta=641.5,670.8
XS Rating Curve= 0 ,0
Exp/Cntr=0.3,0.1

Type RM Length L Ch R = 1 ,29273.6 ,334.1,332.1,330
XS GIS Cut Line= 2
     1839742.806      222432.087     1840555.306      222161.254
#Sta/Elev= 30
       0 1630.46    19.5 1624.01    48.7 1613.19    58.4 1609.87    68.1 1607.11
    77.9 1604.86   175.2 1587.16   204.4 1583.28   243.3 1577.28  293.051572.896
   330.9  1569.9  357.84 1568.89   379.6 1568.42   418.5 1565.87   428.2 1564.86
   447.7 1561.42   457.4 1560.93   476.9 1561.06   486.6 1561.99   506.1 1564.71
   535.3 1567.99     545 1569.45   554.8 1571.71   564.5 1574.67   671.5  1610.5
   720.2 1626.39   739.7 1633.43   759.1 1641.22   778.6 1649.47   856.4 1683.87
#Mann= 5 ,-1 , 0
       0     .12       0  293.05     .06       0  357.84     .12       0
   447.7    .045       0   476.9     .12       0
Bank Sta=447.7,476.9
XS Rating Curve= 0 ,0
Exp/Cntr=0.3,0.1

Type RM Length L Ch R = 1 ,28941.5 ,340,334.5,329
XS GIS Cut Line= 2
     1839840.028      222761.948     1840614.334      222456.393
#Sta/Elev= 30
       0 1659.41    19.6 1654.73    58.8 1644.79   107.7  1631.9   176.3 1614.42
   205.7 1606.22     235 1597.35     284 1583.61   293.8 1581.16   303.6 1579.15
   323.2 1576.25   391.7 1569.45   401.5 1568.95   430.9 1568.39     519 1565.52
   528.8 1564.99   538.6 1563.81   548.5 1562.09   558.2 1561.13     568 1560.96
   577.8  1561.9   587.6  1564.9   597.4 1568.91   636.6 1581.72   675.7 1594.95
   724.7 1610.66   754.1 1619.16   773.7 1624.48     803 1630.66   832.4 1638.84
#Mann= 3 ,-1 , 0
       0     .12       0   548.5    .045       0   577.8     .12       0
Bank Sta=548.5,577.8
XS Rating Curve= 0 ,0
Exp/Cntr=0.3,0.1

Type RM Length L Ch R = 1 ,28607   ,378.7,381.3,383.9
XS GIS Cut Line= 3
     1839899.056      222928.615     1840326.139      222939.032
     1840742.806      222706.393
#Sta/Elev= 30
       0 1666.66    48.6 1655.85    58.3 1653.78      68 1652.08    97.1 1648.58
   126.2 1644.59   165.1 1638.24   184.5 1634.77   194.2  1632.7   213.6 1628.01
   262.2 1615.02   281.6 1610.02     301 1605.59   339.8 1597.59   427.2 1578.36
   456.4  1570.4   466.2 1568.33   485.6 1565.06   505.1 1561.95   514.9 1560.99
   524.6 1560.93   544.1 1561.14   553.8 1561.69     583 1563.35     622 1564.66
   631.7 1565.33   641.5 1566.89     661 1571.55   738.9 1589.18   904.4 1627.48
#Mann= 3 ,-1 , 0
       0     .12       0   514.9    .045       0   553.8     .12       0
Bank Sta=514.9,553.8
XS Rating Curve= 0 ,0
Exp/Cntr=0.3,0.1

Type RM Length L Ch R = 1 ,28225.7 ,389.4,427,463.9
XS GIS Cut Line= 3
     1839958.084      223022.365     1840496.278       223265.42
     1840892.111      223074.448
#Sta/Elev= 30
       0 1672.32    19.7 1672.19    39.4 1670.86    78.7 1664.13    98.4 1660.03
   118.1 1654.53   167.3 1637.12   196.8    1628   236.2 1617.08   255.9 1612.72
   265.7  1611.1   285.4 1608.74   344.5 1604.13   393.7 1602.45   442.9 1602.08
   462.6 1600.67   472.4 1599.13     502 1592.81     561 1582.04   580.7 1577.99
   590.5 1576.43   649.1 1569.49   714.7 1560.39   727.3 1558.61     737 1558.21
   756.6 1559.85   873.8 1572.11   883.5 1574.15   961.7 1596.07    1030  1613.7
#Mann= 3 ,-1 , 0
       0     .12       0   714.7    .045       0   756.6     .12       0
Bank Sta=714.7,756.6
XS Rating Curve= 0 ,0
Exp/Cntr=0.3,0.1

Type RM Length L Ch R = 1 ,27798.7 ,269.3,298.9,327.8
XS GIS Cut Line= 3
     1839961.556      223053.615     1840916.417      223630.004
     1841256.695      223532.782
#Sta/Elev= 30
       0 1672.34     9.8 1670.46    48.9 1660.44   107.6 1646.74   195.7 1617.31
     225 1609.21   244.6 1604.69   303.3 1595.71   332.6 1592.08     362 1590.37
   440.3 1588.18  527.44 1578.65   557.7  1575.4   606.6 1572.14  694.641569.439
   763.1 1567.82   851.2 1564.56   890.3 1561.86   919.7 1557.82   938.4 1557.13
   958.8 1558.23   978.4 1563.72   997.9 1567.34  1115.3 1573.66    1135  1576.5
  1203.8 1592.97  1262.8  1609.1  1341.4 1632.96  1370.9 1643.75  1469.2 1675.93
#Mann= 5 ,-1 , 0
       0     .12       0  527.44     .06       0  694.64     .12       0
   919.7    .045       0   958.8     .12       0
Bank Sta=919.7,958.8
XS Rating Curve= 0 ,0
Exp/Cntr=0.3,0.1