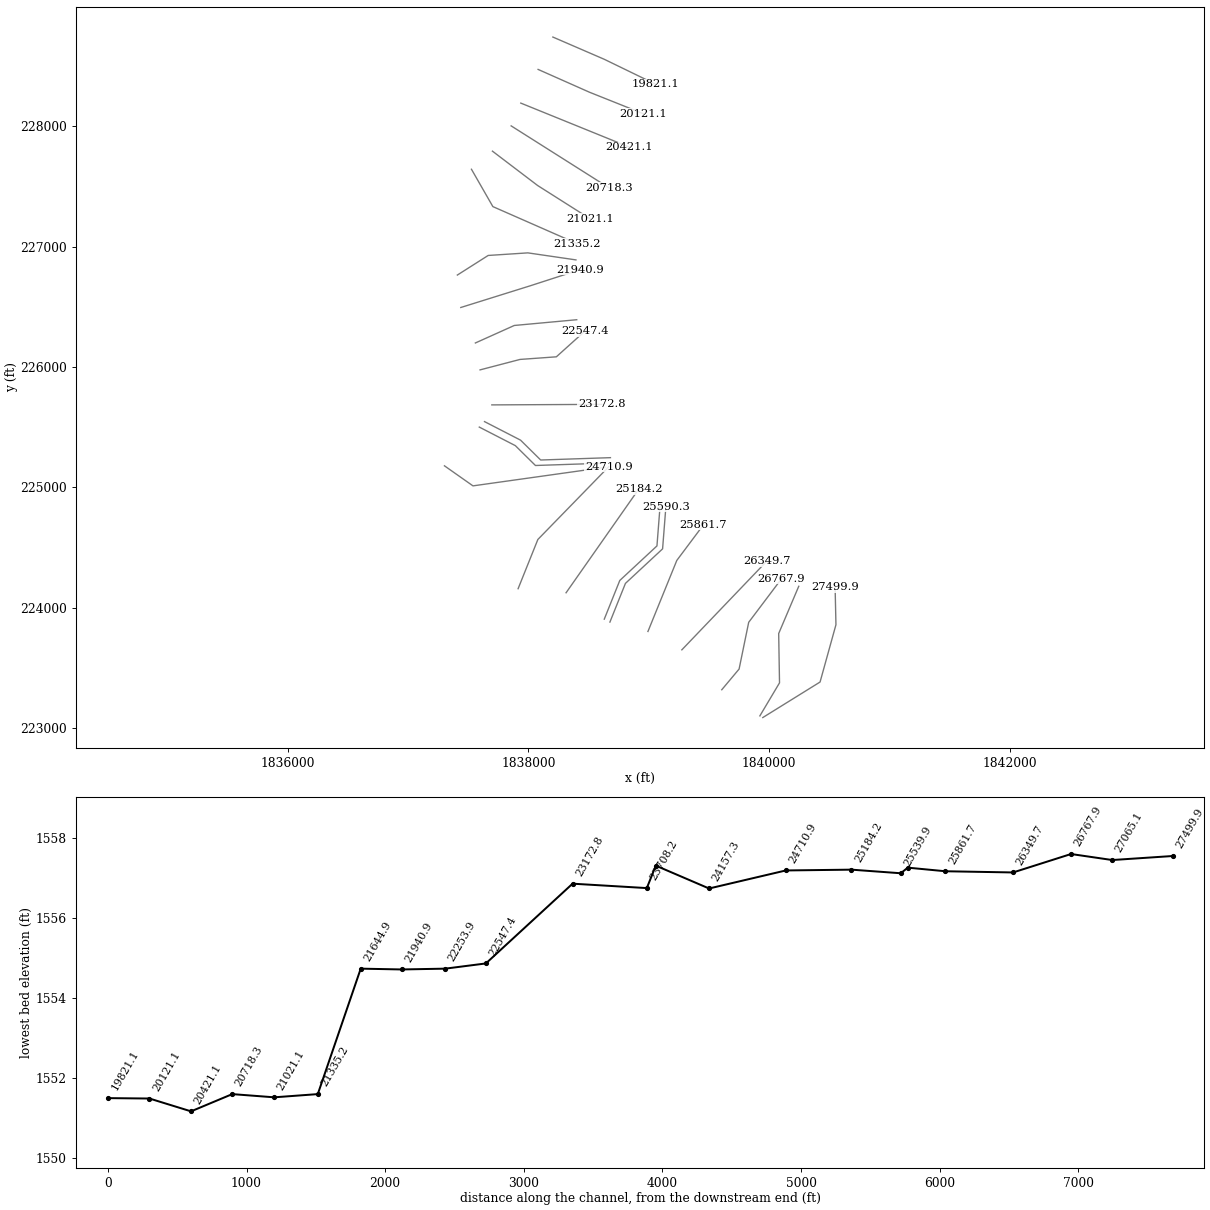
HEC-RAS study SUGARCK.prj: SUGARCK

--- SUGARCK.g01 (geometry) --- (continued)

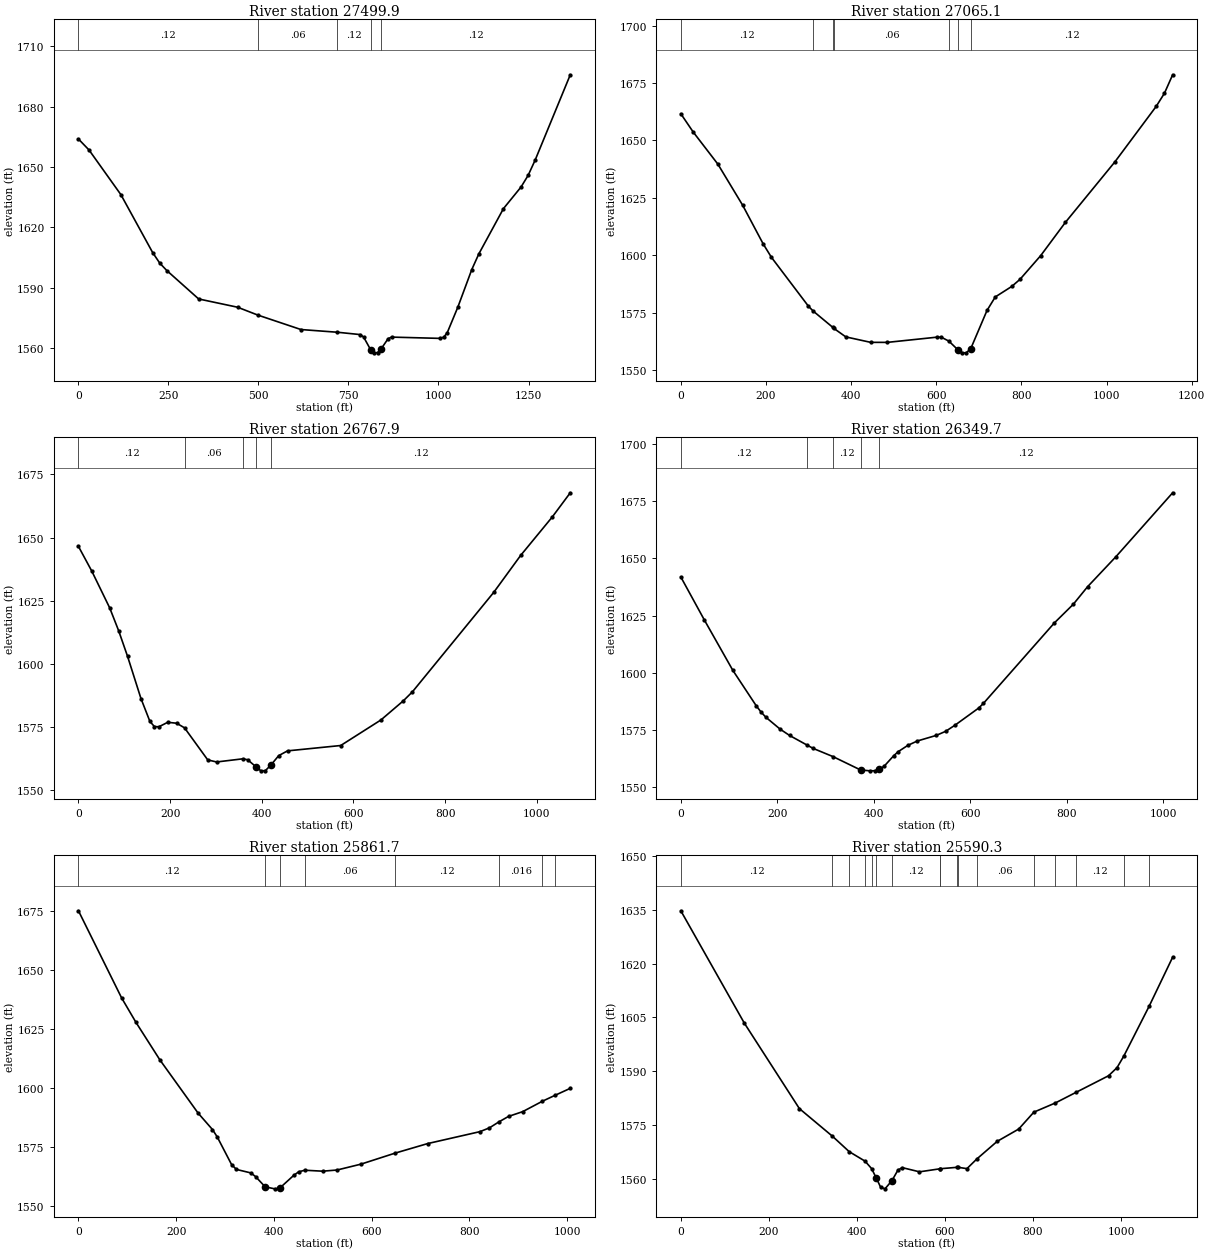
Type RM Length L Ch R = 1 ,27499.9 ,423.8,434.8,445.6
XS GIS Cut Line= 4
     1839947.667      223088.337     1840423.361      223383.476
     1840555.306       223859.17     1840548.361       224171.67
#Sta/Elev= 30
       0 1663.94    29.5 1658.46   117.9 1636.25   206.2 1607.41   225.9 1602.17
   245.5 1598.48   333.9 1584.35     442 1580.24  498.22 1576.33   617.9 1569.14
  719.471567.785   782.4 1566.63   792.1 1565.38   811.5 1559.08   821.2 1557.54
   830.8  1557.7   840.4 1559.43   859.9 1564.55   869.6 1565.37  1005.1 1564.73
  1014.8 1565.35  1024.4 1567.61  1053.5 1580.17  1092.5    1599  1112.1  1606.8
  1180.4 1629.31  1229.3 1640.07  1248.8  1645.8  1268.4 1653.43    1366 1695.91
#Mann= 5 ,-1 , 0
       0     .12       0  498.22     .06       0  719.47     .12       0
   811.5    .045       0   840.4     .12       0
Bank Sta=811.5,840.4
XS Rating Curve= 0 ,0
Exp/Cntr=0.3,0.1

Type RM Length L Ch R = 1 ,27065.1 ,306.7,297.2,287.7
XS GIS Cut Line= 4
     1839923.361      223102.226     1840086.556      223376.532
     1840079.611      223786.254     1840246.278      224178.615
#Sta/Elev= 30
       0 1661.63      29 1653.69      87 1639.68   145.1 1621.81   193.4 1604.92
   212.8 1599.07   299.8 1577.74   311.11575.607  356.651568.589  359.731568.062
   387.5 1564.39     446 1562.01     485    1562   602.1 1564.28   611.9 1564.24
  629.621562.546   650.9 1558.74   660.7  1557.5   670.4 1557.44   681.1 1559.31
   719.2 1575.93   738.6  1581.8   777.4 1586.39   796.8  1589.5   845.2 1599.79
   903.4 1614.33  1019.6 1640.68  1116.5 1664.83  1135.9 1670.56  1155.2 1678.62
#Mann= 7 ,-1 , 0
       0     .12       0   311.1     .06       0  356.65     .12       0
  359.73     .06       0  629.62     .12       0   650.9    .045       0
   681.1     .12       0
Bank Sta=650.9,681.1
XS Rating Curve= 0 ,0
Exp/Cntr=0.3,0.1

Type RM Length L Ch R = 1 ,26767.9 ,437,418.2,398.1
XS GIS Cut Line= 4
     1839606.857      223319.317     1839750.684      223491.117
     1839830.569      223879.648     1840102.904      224240.946
#Sta/Elev= 30
       0  1646.5    29.2 1636.68    68.2 1622.14    87.7 1613.11   107.2 1602.93
   136.4 1586.24   155.9 1577.18   165.6 1575.15   175.4 1575.03   194.8 1576.82
   214.3 1576.45  231.491574.621   282.1 1561.93   301.4  1561.1  358.431562.347
   369.2 1561.99   388.5 1559.02   398.2 1557.59   407.9 1557.66   420.7 1560.04
   436.9  1563.6   456.2  1565.5   572.3 1567.62   660.1 1577.75   709.2 1585.37
   728.9 1588.92     906 1628.25     965 1642.94  1033.8 1658.13  1073.2 1667.74
#Mann= 5 ,-1 , 0
       0     .12       0  231.49     .06       0  358.43     .12       0
   388.5    .045       0   420.7     .12       0
Bank Sta=388.5,420.7
XS Rating Curve= 0 ,0
Exp/Cntr=0.3,0.1

Type RM Length L Ch R = 1 ,26349.7 ,474.6,488,502.1
XS GIS Cut Line= 2
      1839275.26      223650.915     1839980.121      224387.026
#Sta/Elev= 30
       0 1641.86      49 1622.98   107.8 1601.05   156.8  1585.4   166.6 1582.74
   176.4 1580.52   205.8 1575.35   225.4 1572.59   262.11568.329   274.4 1566.92
  315.251563.362   372.4 1557.52     392 1557.13   401.8 1557.18   411.6 1557.74
   421.4 1559.16     441  1563.7   450.8 1565.56   470.4 1568.26     490 1570.17
   529.2 1572.61   548.8  1574.4   568.4 1577.12   617.4  1584.6   627.2 1586.64
   774.2 1621.81   813.4 1629.96   842.8 1637.58   901.6 1650.72  1019.2 1678.67
#Mann= 5 ,-1 , 0
       0     .12       0   262.1     .06       0  315.25     .12       0
   372.4    .045       0   411.6     .12       0
Bank Sta=372.4,411.6
XS Rating Curve= 0 ,0
Exp/Cntr=0.3,0.1

Type RM Length L Ch R = 1 ,25861.7 ,287.9,271.4,254.9
XS GIS Cut Line= 3
     1838993.592      223803.394     1839233.247      224393.454
     1839454.746      224689.391
#Sta/Elev= 30
       0 1675.11    88.2  1638.2   117.6 1627.81   166.6 1611.88     245 1589.25
   274.3 1582.31   284.1 1579.15   313.5 1567.41   323.3 1565.39   352.7 1563.92
   362.5 1562.35   382.1 1558.01   401.7 1557.16   411.5 1557.39   440.9 1562.93
   450.7 1564.38  463.061565.053   499.7 1564.65   529.1 1565.14   578.1 1567.63
  648.411572.332   714.7 1576.36   821.7 1581.42   841.2 1583.04   860.11585.519
   880.1 1587.88   909.2 1589.91  949.661594.343  975.091596.808  1006.5 1599.79
#Mann= 8 ,-1 , 0
       0     .12       0   382.1    .045       0   411.5     .12       0
  463.06     .06       0  648.41     .12       0   860.1    .016       0
  949.66     .12       0  975.09    .016       0
Bank Sta=382.1,411.5
XS Rating Curve= 0 ,0
Exp/Cntr=0.3,0.1

Type RM Length L Ch R = 1 ,25590.3 ,50.3,50.4,50.4
XS GIS Cut Line= 4
     1838677.684      223881.464     1838806.589      224202.819
     1839115.235      224489.679     1839142.469      224838.268
#Sta/Elev= 30
       0 1634.72   144.3 1603.41   269.3 1579.61  344.361571.914  382.561567.606
  418.521564.962  433.351562.899   444.2 1560.21     454 1557.68   463.8 1557.25
   479.7 1559.55   493.2 1562.47     503 1563.16   542.2 1561.99  588.061562.823
  589.051562.847  628.311563.255  630.211563.241     650 1562.88  672.43 1565.57
   718.6 1570.47   767.6 1573.91  802.021578.618  850.811581.176  898.871584.197
   971.6 1588.75     991 1591.02  1006.51594.273 1063.711608.081  1117.3 1621.78
#Mann= 17 ,-1 , 0
       0     .12       0  344.36    .016       0  382.56     .06       0
  418.52    .016       0  433.35     .12       0   444.2    .045       0
   479.7     .12       0  588.06     .06       0  589.05    .016       0
  628.31     .06       0  630.21     .12       0  672.43     .06       0
  802.02    .016       0  850.81     .06       0  898.87     .12       0
  1006.5     .06       0 1063.71     .12       0
Bank Sta=444.2,479.7
XS Rating Curve= 0 ,0
Exp/Cntr=0.3,0.1

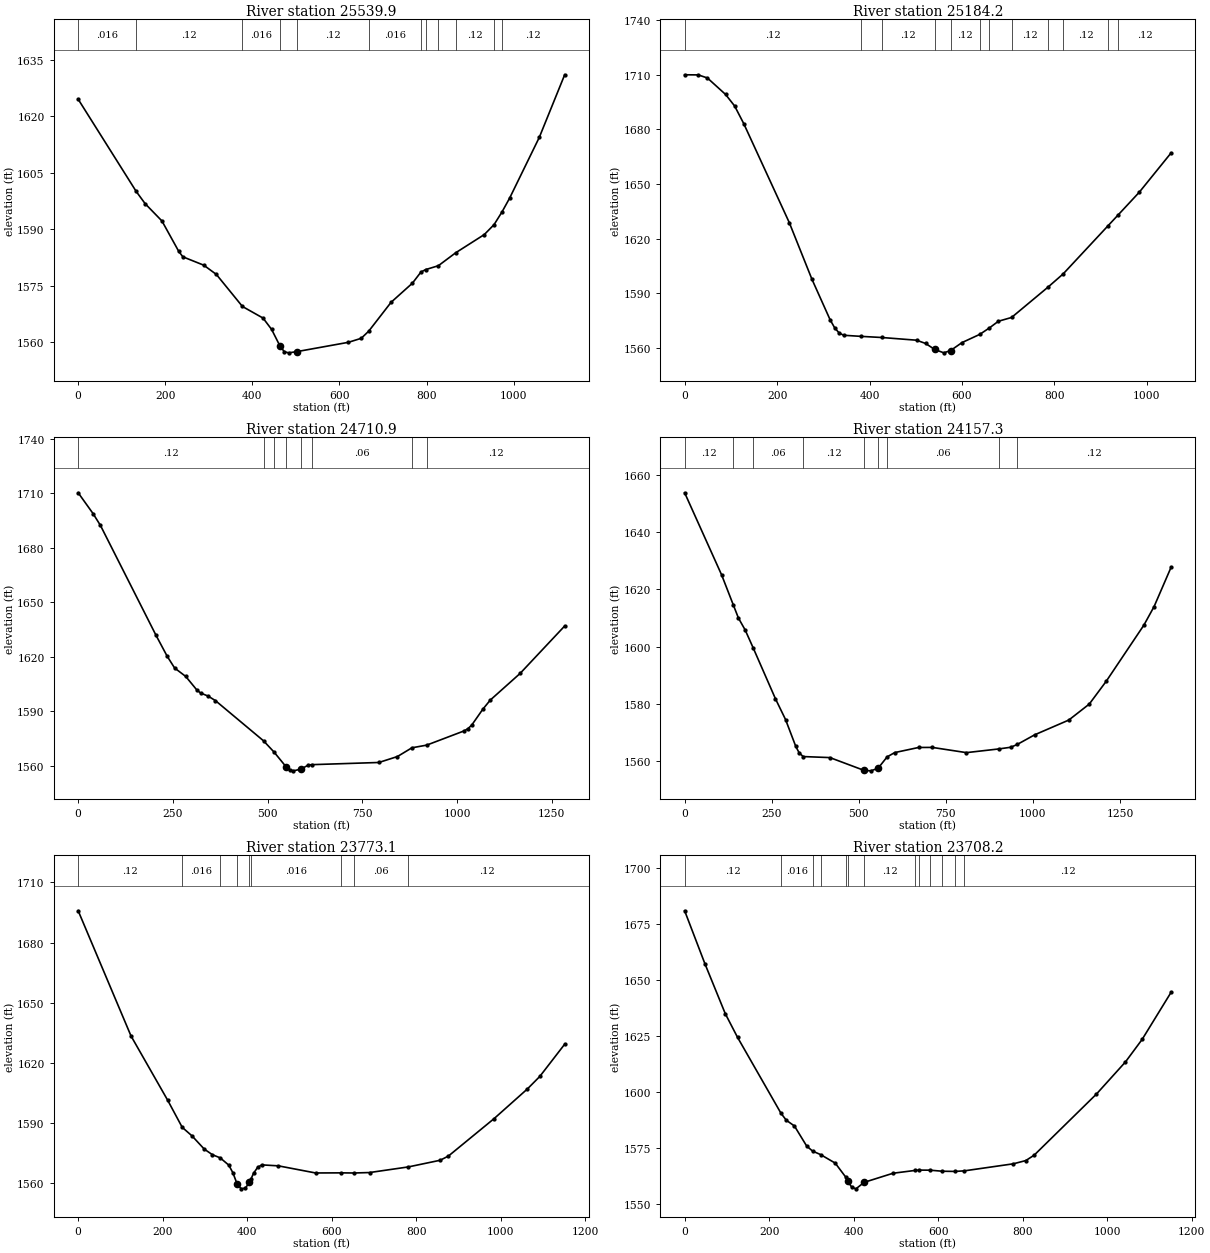
Type RM Length L Ch R = 1 ,25539.9 ,347.7,355.7,363.7
XS GIS Cut Line= 4
     1838630.809      223905.769     1838759.714      224227.125
      1839068.36      224513.984     1839095.594      224862.573
#Sta/Elev= 30
       0 1624.56  133.25 1600.04   153.9 1596.77   192.4 1592.18   230.8 1584.13
   240.4 1582.65   288.5 1580.42   317.4 1577.96  377.261569.439   424.6 1566.35
   444.2 1563.35   463.8 1558.85   473.6 1557.39   483.4 1557.11     503 1557.45
   620.6 1559.91     650 1560.97  667.271562.874   718.6 1570.55   767.6 1575.64
  787.271578.608  797.761579.241  827.241580.285  866.921583.721   932.7 1588.57
  955.151591.214   973.31594.575     991 1598.29    1059 1614.42  1117.3 1631.07
#Mann= 12 ,-1 , 0
       0    .016       0  133.25     .12       0  377.26    .016       0
   463.8    .045       0     503     .12       0  667.27    .016       0
  787.27     .06       0  797.76    .016       0  827.24     .06       0
  866.92     .12       0  955.15     .06       0   973.3     .12       0
Bank Sta=463.8,503
XS Rating Curve= 0 ,0
Exp/Cntr=0.3,0.1

Type RM Length L Ch R = 1 ,25184.2 ,480.5,473.3,465.5
XS GIS Cut Line= 2
     1838313.454      224124.873     1838917.621      224986.852
#Sta/Elev= 30
       0 1709.93    29.5 1709.86    49.2 1708.18    88.5 1699.14   108.2 1692.77
   127.9 1683.08   226.3 1628.79   275.4 1597.63   314.8 1575.33   324.6 1570.93
   334.5 1568.03   344.3 1566.85  380.84 1566.26  426.371565.626   501.7 1564.14
   521.4 1562.34   541.1 1559.05   560.8  1557.2   575.5 1558.48   600.1 1562.83
  638.451567.334  659.281570.859   678.8 1574.55  707.351576.629  785.561593.159
  818.961600.552  916.161627.028  937.091632.718   983.8 1645.46  1052.6 1667.05
#Mann= 12 ,-1 , 0
       0     .12       0  380.84     .06       0  426.37     .12       0
   541.1    .045       0   575.5     .12       0  638.45     .06       0
  659.28    .016       0  707.35     .12       0  785.56     .06       0
  818.96     .12       0  916.16     .06       0  937.09     .12       0
Bank Sta=541.1,575.5
XS Rating Curve= 0 ,0
Exp/Cntr=0.3,0.1

Type RM Length L Ch R = 1 ,24710.9 ,582,553.6,527.5
XS GIS Cut Line= 3
     1837915.017      224158.727     1838079.079      224567.581
     1838667.621      225171.748
#Sta/Elev= 30
       0 1710.23    39.2  1698.8    58.7 1692.28   205.6 1631.71     235 1620.21
   254.5 1613.78   283.9 1609.13   313.3 1601.66   323.1 1600.02   342.6 1598.35
   362.2 1595.84   489.2  1573.7  516.92 1567.52   548.4 1559.48   558.2 1557.65
     568 1557.18   587.6 1558.11   607.3 1560.33  615.921560.576   793.6 1561.78
   842.6 1565.05  880.751569.859  919.741571.326  1019.2 1579.21    1029 1580.46
  1038.8 1582.39  1068.2 1591.16  1087.8 1596.16  1166.3 1610.78    1284  1636.9
#Mann= 8 ,-1 , 0
       0     .12       0   489.2     .06       0  516.92     .12       0
   548.4    .045       0   587.6     .12       0  615.92     .06       0
  880.75    .016       0  919.74     .12       0
Bank Sta=548.4,587.6
XS Rating Curve= 0 ,0
Exp/Cntr=0.3,0.1

Type RM Length L Ch R = 1 ,24157.3 ,413.8,384.2,351.6
XS GIS Cut Line= 3
     1837303.037       225179.56     1837540.017      225012.894
     1838636.371      225166.974
#Sta/Elev= 30
       0 1653.71   106.2 1625.06  139.971614.517   154.5    1610   173.8 1605.85
  196.591599.665   260.8 1581.84   289.7 1574.62   319.1 1565.24   328.9 1562.98
  340.371561.709   417.1 1561.35   515.1 1556.89   534.7 1556.73   555.5 1557.65
  581.411561.606   603.2  1563.1   671.8 1564.88     711  1564.9     809 1563.08
  901.461564.361   936.4 1564.96  954.691565.917  1004.9 1569.29  1102.9 1574.44
  1161.7 1580.01  1210.7 1588.02  1318.5 1607.54  1347.9 1614.04  1396.8 1627.78
#Mann= 9 ,-1 , 0
       0     .12       0  139.97    .016       0  196.59     .06       0
  340.37     .12       0   515.1    .045       0   555.5     .12       0
  581.41     .06       0  901.46    .016       0  954.69     .12       0
Bank Sta=515.1,555.5
XS Rating Curve= 0 ,0
Exp/Cntr=0.3,0.1

Type RM Length L Ch R = 1 ,23773.1 ,64.9,64.9,64.9
XS GIS Cut Line= 4
     1837592.534      225501.175     1837892.013      225347.095
     1838059.114      225182.165     1838638.541      225201.696
#Sta/Elev= 30
       0  1695.9   125.1 1633.47   211.7  1601.5  246.231587.951   269.4 1583.69
   298.3 1577.12   317.6 1574.32  336.051572.746   356.4 1569.12   366.1 1565.31
   375.9 1559.87   385.7  1557.3   395.5 1557.66   405.3 1560.47  408.441561.956
     415 1565.06   424.8 1568.04   434.6 1569.24   473.8 1568.76   561.8 1565.21
  623.041565.265  652.611565.198   689.5 1565.42  781.151568.218   856.5 1571.54
   876.2 1573.65   984.3 1592.31  1062.9 1607.06  1092.4 1613.32  1151.3 1629.39
#Mann= 9 ,-1 , 0
       0     .12       0  246.23    .016       0  336.05     .12       0
   375.9    .045       0   405.3     .12       0  408.44    .016       0
  623.04     .12       0  652.61     .06       0  781.15     .12       0
Bank Sta=375.9,405.3
XS Rating Curve= 0 ,0
Exp/Cntr=0.3,0.1

Type RM Length L Ch R = 1 ,23708.2 ,505.8,535.4,564.7
XS GIS Cut Line= 4
     1837635.937      225546.748     1837935.416      225392.668
     1838102.517      225227.737     1838681.944      225247.269
#Sta/Elev= 30
       0 1680.92    48.1  1657.2    96.2 1634.95   125.1 1624.42  228.071590.463
   240.6 1587.37   259.8 1584.81   288.7 1575.88   302.71573.603  321.891572.019
   356.4 1568.22  380.831562.074   386.2 1560.15   395.5 1557.43   405.3 1556.74
   424.8 1559.64   493.3 1563.71  546.061564.979  554.711565.103  580.341565.081
  609.911564.602  639.491564.516  661.671564.769   777.9 1567.92   807.4 1569.37
   827.1 1571.77   974.5 1599.06  1043.2 1613.42  1082.6 1623.46  1151.3 1644.55
#Mann= 13 ,-1 , 0
       0     .12       0  228.07    .016       0   302.7     .12       0
  321.89    .016       0  380.83     .12       0   386.2    .045       0
   424.8     .12       0  546.06     .06       0  554.71     .12       0
  580.34     .06       0  609.91     .12       0  639.49     .06       0
  661.67     .12       0
Bank Sta=386.2,424.8
XS Rating Curve= 0 ,0
Exp/Cntr=0.3,0.1

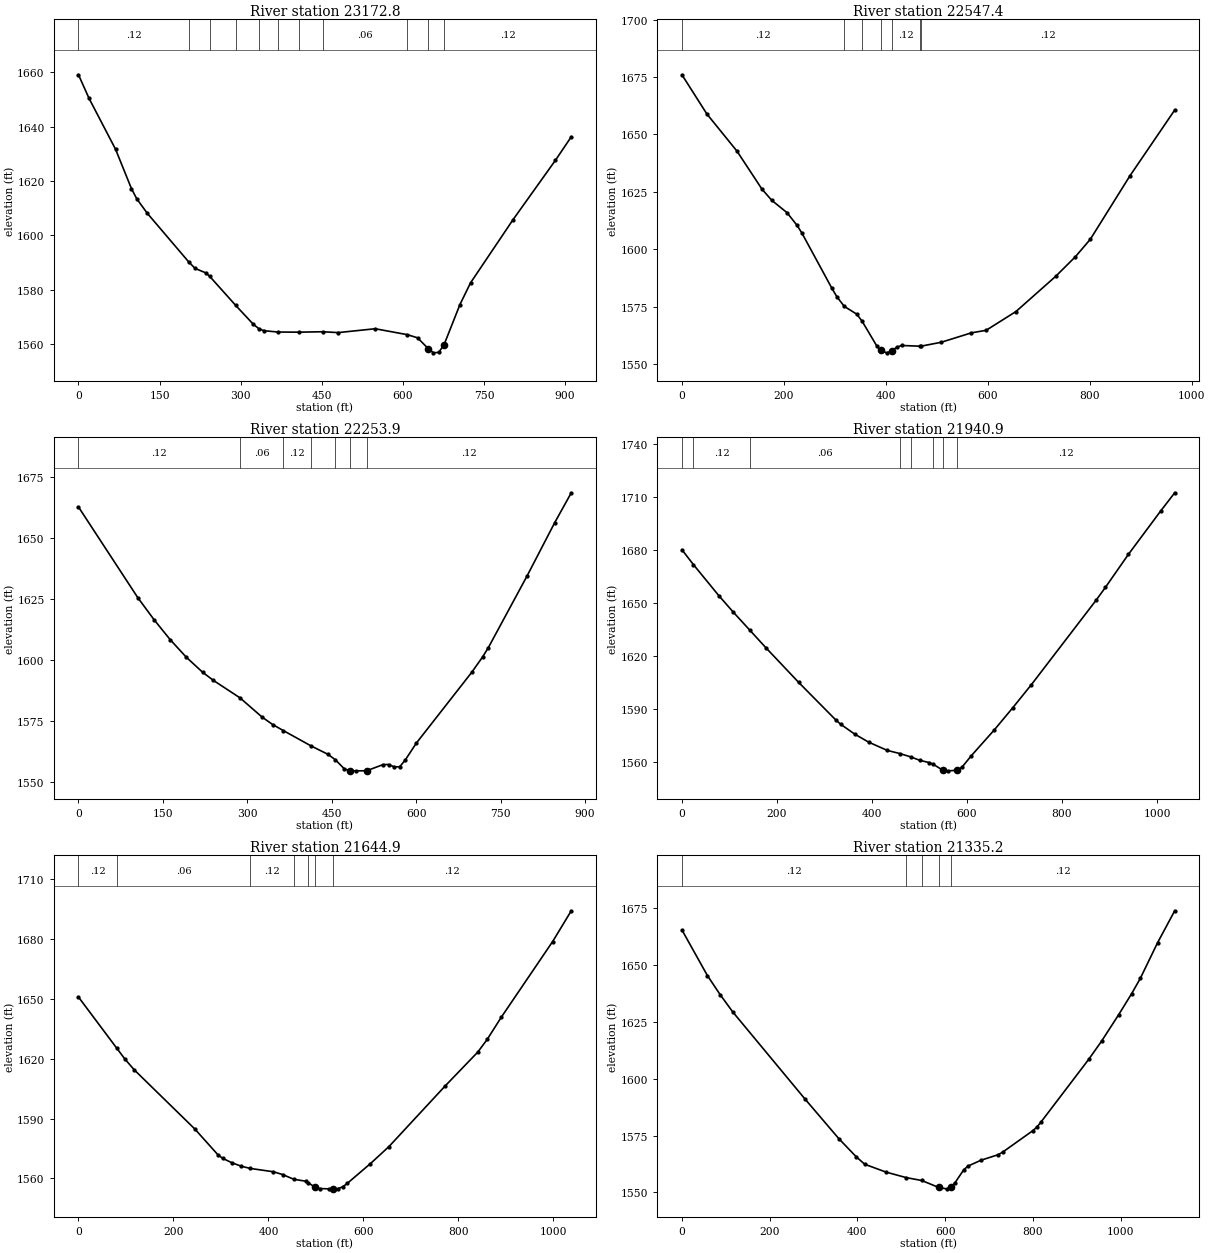
Type RM Length L Ch R = 1 ,23172.8 ,621.9,625.3,627.5
XS GIS Cut Line= 2
     1837696.701      225685.637     1838608.159      225689.977
#Sta/Elev= 30
       0 1659.08    19.6 1650.37    68.6 1631.68      98  1617.2   107.8 1613.46
   127.4 1608.12  203.631590.338   215.6  1587.9   235.2 1586.27  242.741584.954
  290.761574.294   323.4 1567.35  333.571565.741     343 1564.99  368.791564.502
  408.281564.449  451.741564.608   480.2 1564.29   548.8 1565.71  608.461563.523
   627.2 1562.37   646.8 1558.43   656.6 1556.85   666.4 1557.03   676.2 1559.85
   705.6 1574.62   725.2  1582.6   803.7 1605.79   882.1 1627.62   911.5 1636.29
#Mann= 11 ,-1 , 0
       0     .12       0  203.63    .016       0  242.74     .12       0
  290.76     .06       0  333.57     .12       0  368.79     .06       0
  408.28    .016       0  451.74     .06       0  608.46     .12       0
   646.8    .045       0   676.2     .12       0
Bank Sta=646.8,676.2
XS Rating Curve= 0 ,0
Exp/Cntr=0.3,0.1

Type RM Length L Ch R = 1 ,22547.4 ,292.8,293.5,294.2
XS GIS Cut Line= 4
     1837599.044      225976.435     1837931.076      226063.241
     1838232.725      226084.942      1838471.44      226299.786
#Sta/Elev= 30
       0 1675.94      49 1658.85   107.9 1642.72   156.9 1626.18   176.5 1621.21
   205.9 1615.96   225.5 1610.48   235.3 1607.05   294.2 1582.97     304 1579.28
  318.481575.103   343.2 1571.67  353.451568.643   382.2 1557.89   389.6 1556.02
   401.7 1554.86   411.5 1555.64   421.2  1557.3     431 1558.07  466.841557.747
  468.931557.756     509 1559.48   567.6 1563.55   596.8 1564.67   655.4 1572.86
   733.2 1588.16   772.1 1596.75   801.3 1604.34   879.2 1632.03   966.8 1660.59
#Mann= 7 ,-1 , 0
       0     .12       0  318.48    .016       0  353.45     .12       0
   389.6    .045       0   411.5     .12       0  466.84     .06       0
  468.93     .12       0
Bank Sta=389.6,411.5
XS Rating Curve= 0 ,0
Exp/Cntr=0.3,0.1

Type RM Length L Ch R = 1 ,22253.9 ,304.9,313,320.7
XS GIS Cut Line= 3
     1837559.982       226199.96     1837883.332      226345.359
     1838401.996      226393.102
#Sta/Elev= 30
       0 1662.69   105.4 1625.57   134.2 1616.58   162.9  1608.4   191.6  1601.2
   220.4 1595.09   239.6 1591.74  286.831584.601   325.8 1576.79     345 1573.66
  363.85 1571.21  413.221564.915     443 1561.51  456.51 1559.23   472.5 1555.48
   482.3 1554.76   492.1 1554.73   511.8 1554.76   541.3  1557.3   551.1 1557.32
   560.9 1556.34   570.7 1556.42   580.6  1559.2   600.2 1566.09   698.5 1595.03
   718.2 1601.44     728 1605.12   796.8 1634.44   845.9 1656.25   875.4  1668.5
#Mann= 7 ,-1 , 0
       0     .12       0  286.83     .06       0  363.85     .12       0
  413.22    .016       0  456.51     .12       0   482.3    .045       0
   511.8     .12       0
Bank Sta=482.3,511.8
XS Rating Curve= 0 ,0
Exp/Cntr=0.3,0.1

Type RM Length L Ch R = 1 ,21940.9 ,305.1,296.1,287
XS GIS Cut Line= 3
      1837439.03      226494.761     1838020.219      226676.377
     1838427.691      226808.431
#Sta/Elev= 30
       0 1680.12   24.261671.648    78.6 1653.78     108 1644.76  142.221634.683
   176.8 1624.51   245.5 1604.93   324.1 1583.49   333.9 1581.17   363.4 1575.58
   392.8 1571.02   432.1  1566.3  458.461564.529   481.2 1562.66   500.9 1560.65
   520.5  1559.4  528.681558.474     550 1554.91   559.8 1554.71   579.4 1555.02
   589.3 1556.72   608.9 1563.23   657.6 1577.97   696.5 1590.55   735.5 1603.59
   871.8 1651.51   891.2 1658.71   939.9 1677.56    1008 1702.22  1037.2 1712.42
#Mann= 8 ,-1 , 0
       0     .06       0   24.26     .12       0  142.22     .06       0
  458.46     .12       0   481.2    .016       0  528.68     .12       0
     550    .045       0   579.4     .12       0
Bank Sta=550,579.4
XS Rating Curve= 0 ,0
Exp/Cntr=0.3,0.1

Type RM Length L Ch R = 1 ,21644.9 ,327.3,309.7,291.2
XS GIS Cut Line= 4
     1837410.242      226764.196     1837666.319      226926.956
     1837996.196      226948.411     1838395.485      226890.064
#Sta/Elev= 30
       0 1650.97   80.861625.213    97.9  1619.8   117.4 1614.45   244.7 1584.81
   293.6 1571.81   303.4 1570.05   322.9 1567.83   342.3 1566.11  361.541564.973
   410.4  1563.3   429.8  1561.9  453.37 1559.52   478.4 1558.56  483.761557.761
   497.9 1555.56   507.6 1554.86     527 1554.73   536.8 1554.73   546.5 1554.85
   556.2 1555.72   565.9 1557.47   614.6 1567.38   653.7 1575.95   771.8 1606.31
   840.7 1623.37   860.4 1629.69   889.9 1640.77   998.2 1678.81  1037.5 1694.27
#Mann= 7 ,-1 , 0
       0     .12       0   80.86     .06       0  361.54     .12       0
  453.37    .016       0  483.76     .12       0   497.9    .045       0
   536.8     .12       0
Bank Sta=497.9,536.8
XS Rating Curve= 0 ,0
Exp/Cntr=0.3,0.1

Type RM Length L Ch R = 1 ,21335.2 ,323.1,314.1,308.9
XS GIS Cut Line= 3
      1837527.43      227643.102     1837705.381      227332.772
     1838406.336      227024.612
#Sta/Elev= 30
       0 1665.37      58 1645.34      87 1636.97     116 1629.31   280.4  1591.1
   357.7 1573.65     397 1565.76   416.6 1562.41   465.7 1558.93  511.331556.533
  546.711555.265   585.5 1552.19   603.2  1551.6     613  1552.2   622.8 1554.36
   642.4 1559.96   652.2  1561.6   681.7 1564.17     721 1566.61   730.8 1567.68
   799.5  1577.1   809.3 1578.76   819.1 1581.09   927.1 1608.44   956.6 1616.48
   995.8 1628.18  1025.3  1637.4  1044.9 1644.06  1084.2 1659.71  1123.4 1673.79
#Mann= 5 ,-1 , 0
       0     .12       0  511.33    .016       0  546.71     .12       0
   585.5    .045       0     613     .12       0
Bank Sta=585.5,613
XS Rating Curve= 0 ,0
Exp/Cntr=0.3,0.1

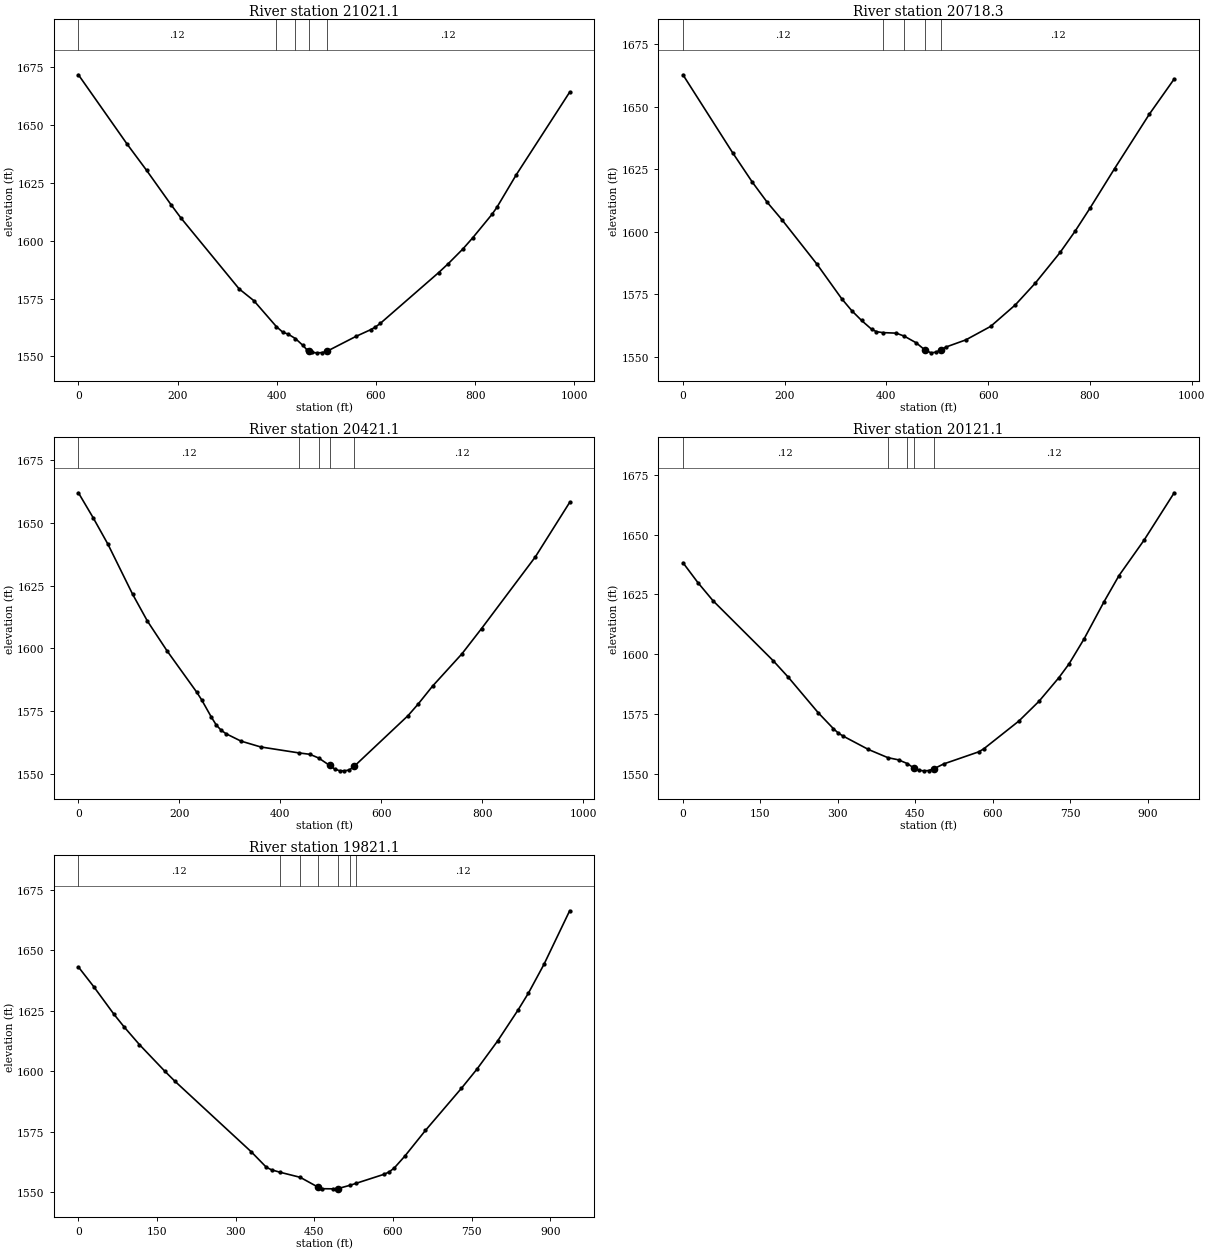
Type RM Length L Ch R = 1 ,21021.1 ,299.4,302.8,302.7
XS GIS Cut Line= 3
     1837701.789       227793.39     1838077.167      227508.006
     1838515.461       227230.02
#Sta/Elev= 30
       0 1671.67    98.2 1641.71   137.5 1630.37   186.6 1615.58   206.3 1609.91
   324.2 1579.13   353.7 1574.08  399.191562.861   412.6 1560.35   422.4 1559.66
  437.451557.706   451.9  1554.9   461.7 1552.64     464 1552.41   471.5 1551.67
   481.3 1551.52   491.1 1551.62   500.9 1552.16   559.7 1558.63   589.1  1561.5
   598.8 1562.66   608.6 1564.21   726.2 1586.15   745.7 1590.03   775.1 1596.36
   794.7 1601.12   833.9 1611.34   843.7 1614.33   882.8 1628.42   990.6 1664.16
#Mann= 5 ,-1 , 0
       0     .12       0  399.19    .016       0  437.45     .12       0
     464    .045       0   500.9     .12       0
Bank Sta=464,500.9
XS Rating Curve= 0 ,0
Exp/Cntr=0.3,0.1

Type RM Length L Ch R = 1 ,20718.3 ,290.6,297.2,304.1
XS GIS Cut Line= 2
     1837857.291      228003.345     1838673.263      227486.852
#Sta/Elev= 30
       0 1662.75    97.6 1631.61   136.6 1619.77   165.8 1611.74   195.1 1604.68
   263.4 1587.05   312.2  1573.2   331.6 1568.51   351.2 1564.53   370.7 1561.06
   380.4 1560.07  392.781559.687   419.4 1559.47  435.241558.254   458.5 1555.61
   475.9  1552.7   487.7  1551.6   497.5 1551.87   507.2 1552.86     517 1553.92
     556 1556.77   604.8 1562.16   653.6 1570.81   692.6 1579.46   741.4 1591.72
   770.6 1600.14   799.9 1609.34   848.6 1625.28   916.9 1647.02   965.7 1661.07
#Mann= 5 ,-1 , 0
       0     .12       0  392.78    .016       0  435.24     .12       0
   475.9    .045       0   507.2     .12       0
Bank Sta=475.9,507.2
XS Rating Curve= 0 ,0
Exp/Cntr=0.3,0.1

Type RM Length L Ch R = 1 ,20421.1 ,301.2,300,300.2
XS GIS Cut Line= 3
     1837937.313        228192.6     1838416.561      227998.186
     1838839.009      227826.701
#Sta/Elev= 30
       0 1661.96    29.3 1651.98    58.6 1641.42   107.3 1621.56   136.6 1610.86
   175.6 1598.97   234.2 1582.56     244  1579.5   263.5 1572.52   273.2 1569.39
     283  1567.3   292.7 1565.93     322 1563.02     361 1560.69  436.511558.323
   458.6 1557.75  475.951556.276   497.7 1553.32   507.4 1551.92   517.2 1551.22
   526.9 1551.17   536.6 1551.52   546.3 1552.97     653 1573.18   672.4 1577.64
   701.5 1584.92   759.7 1597.79   798.5 1607.84   905.2 1636.44   973.1 1658.13
#Mann= 5 ,-1 , 0
       0     .12       0  436.51    .016       0  475.95     .12       0
   497.7    .045       0   546.3     .12       0
Bank Sta=497.7,546.3
XS Rating Curve= 0 ,0
Exp/Cntr=0.3,0.1

Type RM Length L Ch R = 1 ,20121.1 ,299.6,300,297.2
XS GIS Cut Line= 3
     1838081.088      228472.362     1838506.998      228283.308
     1838957.591      228103.392
#Sta/Elev= 30
       0 1638.25    29.1  1629.9    58.2  1622.4   174.7  1597.4   203.9 1590.53
   262.1 1575.66   291.2  1569.1     301 1567.19   310.7 1565.91   359.2 1560.39
  396.791556.984   417.4 1556.07  434.651554.501   446.6 1552.73   456.3 1551.75
     466 1551.49   475.7 1551.61   485.4 1552.31   504.8 1554.36   572.7 1559.41
   582.4 1560.65   650.4 1572.24   689.2 1580.43     728 1590.35   747.4 1596.01
   776.5  1606.4   815.3 1621.96   844.4  1632.9     893 1647.69   951.2 1667.39
#Mann= 5 ,-1 , 0
       0     .12       0  396.79    .016       0  434.65     .12       0
   446.6    .045       0   485.4     .12       0
Bank Sta=446.6,485.4
XS Rating Curve= 0 ,0
Exp/Cntr=0.3,0.1

Type RM Length L Ch R = 1 ,19821.1 ,290,300,311.4
XS GIS Cut Line= 3
     1838203.776      228741.277     1838630.797      228556.551
     1839055.029       228350.52
#Sta/Elev= 30
       0 1643.15    29.1 1635.05    67.8 1623.61    87.2 1618.38   116.3  1611.1
   164.8 1600.09   184.2 1595.92   329.6 1566.81   358.6 1560.38   368.3 1559.36
  384.141558.378  423.011556.257   457.8 1552.11   465.3 1551.55   484.9  1551.5
   494.7 1551.59  518.871553.019  529.981553.807   583.2 1557.53     593 1558.52
   602.8 1560.21   622.5    1565   661.8 1575.61   730.6 1593.06     760 1600.92
   799.3 1612.51   838.6 1625.41   858.3 1632.36   887.8 1644.18   936.9 1666.36
#Mann= 7 ,-1 , 0
       0     .12       0  384.14    .016       0  423.01     .12       0
   457.8    .045       0   494.7     .12       0  518.87     .06       0
  529.98     .12       0
Bank Sta=457.8,494.7
XS Rating Curve= 0 ,0
Exp/Cntr=0.3,0.1