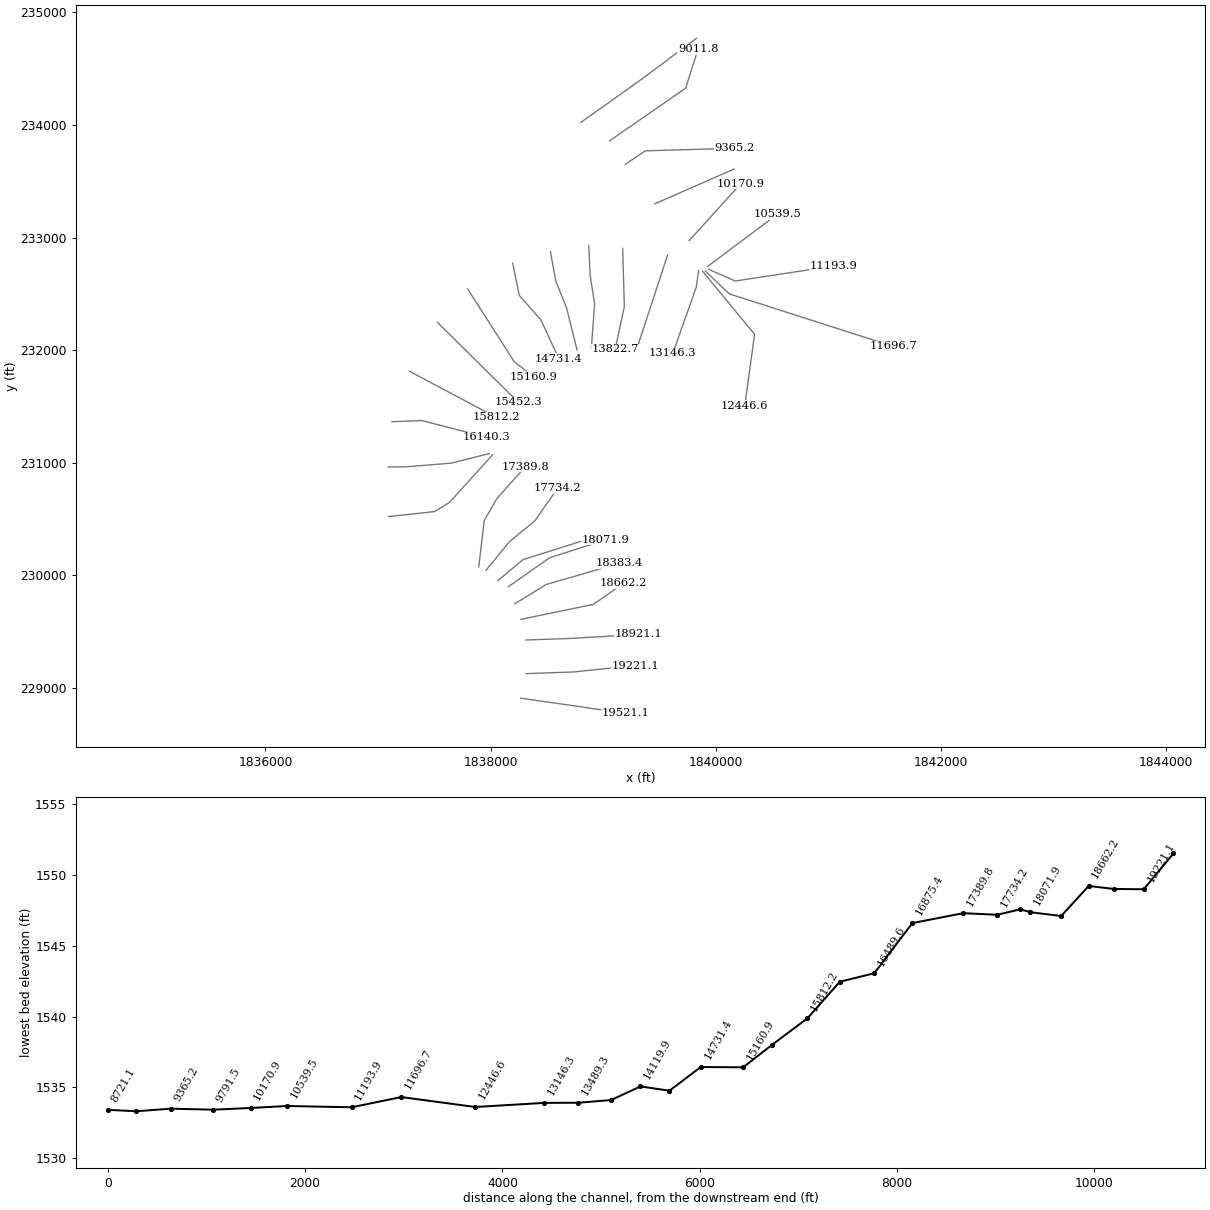
HEC-RAS study SUGARCK.prj: SUGARCK

--- SUGARCK.g01 (geometry) --- (continued)

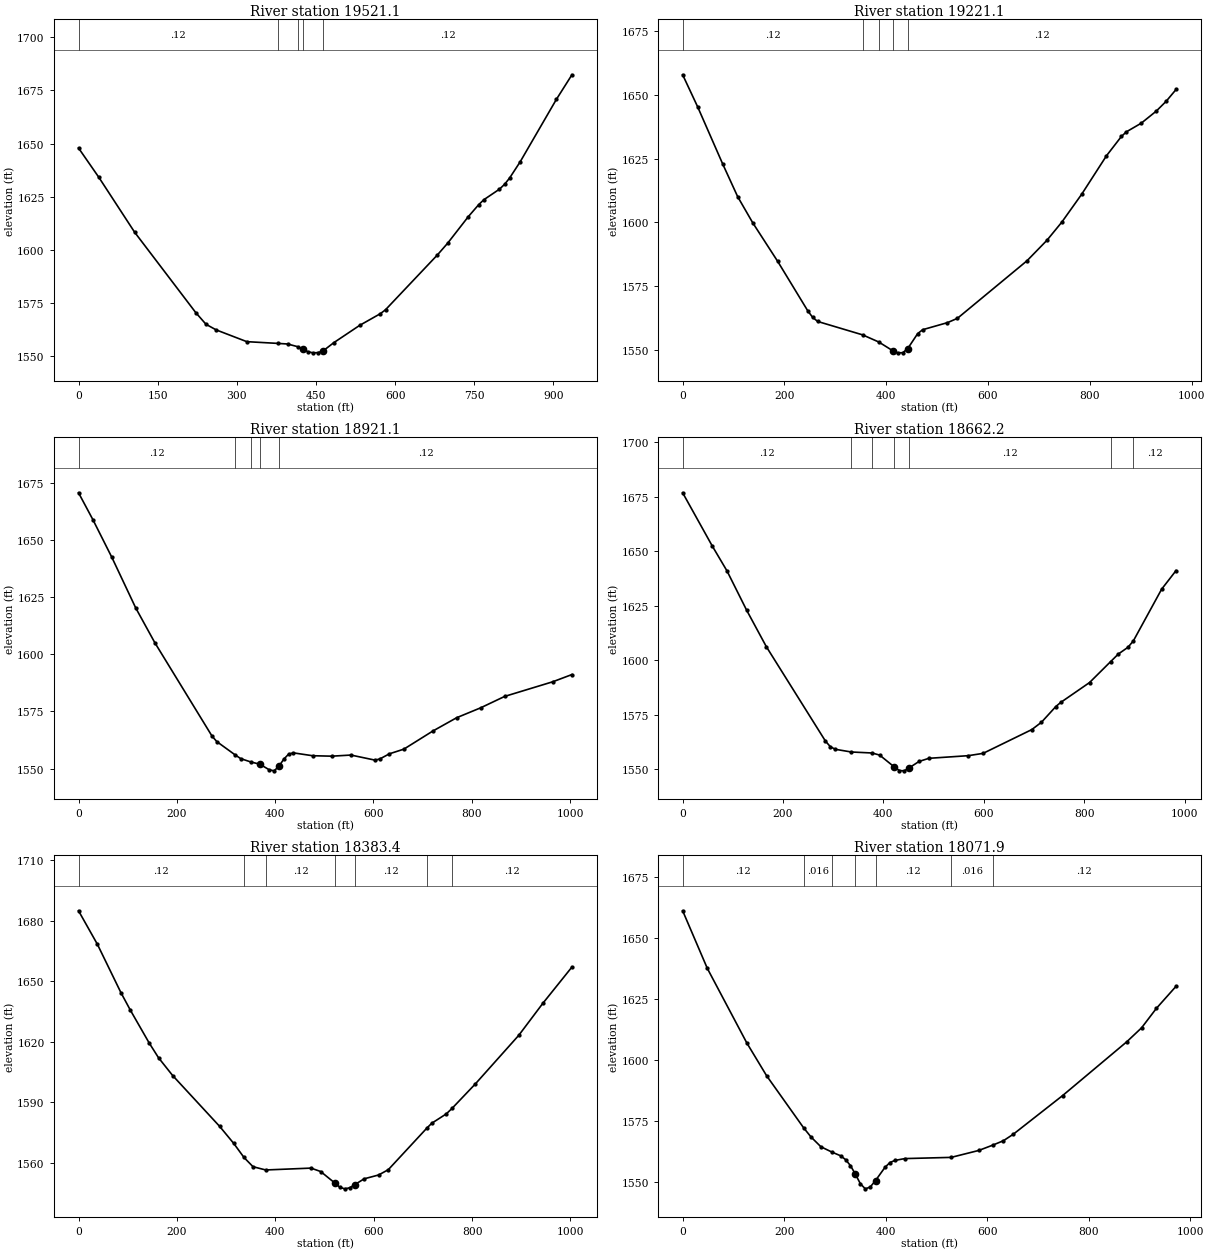
Type RM Length L Ch R = 1 ,19521.1 ,293.4,300,309.4
XS GIS Cut Line= 3
     1838269.133       228907.64     1838709.174      228845.072
     1839194.471      228773.069
#Sta/Elev= 30
       0 1647.87    38.6 1634.05   106.3 1608.27   222.2 1570.44   241.6 1564.95
   260.9 1562.31   318.9 1556.78  377.74 1555.96   396.2 1555.68  415.781554.386
   425.1 1553.25   434.8 1552.03   444.5 1551.52   454.3 1551.63   464.1 1552.55
   483.7 1556.29   532.8 1564.44     572 1569.94   581.8 1571.79     680 1597.54
   699.6 1603.11   738.8 1615.62   758.5 1621.26   768.3 1623.58   797.7 1628.51
   807.5 1630.81   817.3 1633.88     837 1641.39   905.6 1670.76   935.1 1682.33
#Mann= 5 ,-1 , 0
       0     .12       0  377.74    .016       0  415.78     .12       0
   425.1    .045       0   464.1     .12       0
Bank Sta=425.1,464.1
XS Rating Curve= 0 ,0
Exp/Cntr=0.3,0.1

Type RM Length L Ch R = 1 ,19221.1 ,299.8,300,298.2
XS GIS Cut Line= 3
     1838316.579       229126.15     1838738.968      229141.002
     1839282.708      229198.236
#Sta/Elev= 30
       0 1657.79    29.5 1645.23    78.6 1622.92   108.1 1610.09   137.6  1599.9
   186.8 1584.75   245.7 1565.46   255.6 1562.82   265.4 1561.26  353.451556.031
  385.191553.244   412.8 1549.81   422.6 1548.99   432.4 1549.04   442.2 1550.67
   461.7  1556.5   471.5 1558.04   520.3 1560.81   539.8 1562.49   676.5 1585.01
   715.6 1593.01   744.8  1600.1   783.9 1611.03   832.7 1626.11     862 1633.66
   871.8 1635.47     901 1638.85   930.3 1643.54   949.9 1647.41   969.4 1652.04
#Mann= 5 ,-1 , 0
       0     .12       0  353.45    .016       0  385.19     .12       0
   412.8    .045       0   442.2     .12       0
Bank Sta=412.8,442.2
XS Rating Curve= 0 ,0
Exp/Cntr=0.3,0.1

Type RM Length L Ch R = 1 ,18921.1 ,252.5,258.9,264.5
XS GIS Cut Line= 3
      1838311.28      229424.734     1838699.181       229438.27
     1839313.697      229474.039
#Sta/Elev= 30
       0 1670.75    29.1 1659.03    67.9 1642.44   116.4 1620.31   155.2 1605.12
   271.7 1564.17   281.4 1561.79  318.311556.034   329.9 1554.36  350.581552.891
   368.7 1551.93   388.1 1549.45   397.9 1549.01   407.7 1551.04   417.4 1554.08
   427.2 1556.29     437 1556.88   476.1 1555.63   515.2 1555.43   554.2 1555.92
   603.1  1553.7   612.9 1554.21   632.4 1556.47   661.7  1558.5   720.3 1566.38
   769.2 1572.27     818  1576.6   866.9  1581.6   964.6    1588  1003.7 1591.17
#Mann= 5 ,-1 , 0
       0     .12       0  318.31    .016       0  350.58     .12       0
   368.7    .045       0   407.7     .12       0
Bank Sta=368.7,407.7
XS Rating Curve= 0 ,0
Exp/Cntr=0.3,0.1

Type RM Length L Ch R = 1 ,18662.2 ,275.6,278.8,281.6
XS GIS Cut Line= 3
     1838270.408      229608.657     1838914.148      229741.626
     1839181.076      229928.258
#Sta/Elev= 30
       0 1676.87    58.9 1652.47    88.3 1641.01   127.5 1622.95   166.8 1606.18
   284.5 1562.86   294.3 1560.29   304.1 1559.11  335.921557.872  377.341557.414
   392.4 1556.46   421.9 1550.95   431.7 1549.36   441.5 1549.22   451.3  1550.6
   470.9 1553.52   490.5 1554.97     569 1556.18   598.5 1557.24   695.6 1568.16
   714.8 1571.52   743.5 1578.75   753.1 1580.61   810.6 1589.75  852.381599.308
   868.1 1602.87   887.2 1605.94  897.891608.876   954.3 1632.64     983 1641.17
#Mann= 7 ,-1 , 0
       0     .12       0  335.92    .016       0  377.34     .12       0
   421.9    .045       0   451.3     .12       0  852.38    .016       0
  897.89     .12       0
Bank Sta=421.9,451.3
XS Rating Curve= 0 ,0
Exp/Cntr=0.3,0.1

Type RM Length L Ch R = 1 ,18383.4 ,301.3,311.5,317
XS GIS Cut Line= 3
     1838215.969      229747.347     1838493.142      229917.408
     1839144.183       230106.21
#Sta/Elev= 30
       0 1684.84    38.3 1668.26    86.1 1644.33   105.2 1635.68   143.5  1619.4
   162.6 1612.04   191.3 1603.24   286.9 1578.03   315.6 1569.57  336.371562.633
   354.7 1558.06  380.571556.446   472.6 1557.37   492.2 1555.68   521.7 1549.85
   531.5 1547.83   541.3  1547.1   551.1 1547.62     561  1549.1   580.6 1552.06
   610.1 1553.97   629.7 1556.59  708.291577.247   718.2 1579.62   747.6 1584.23
  759.22 1586.94   806.6 1599.06     895 1623.18   944.1 1639.08    1003 1656.97
#Mann= 7 ,-1 , 0
       0     .12       0  336.37    .016       0  380.57     .12       0
   521.7    .045       0     561     .12       0  708.29    .016       0
  759.22     .12       0
Bank Sta=521.7,561
XS Rating Curve= 0 ,0
Exp/Cntr=0.3,0.1

Type RM Length L Ch R = 1 ,18071.9 ,112.4,102.7,93.7
XS GIS Cut Line= 3
      1838158.94      229898.744      1838525.26      230155.689
      1839025.26      230315.411
#Sta/Elev= 30
       0 1661.08    48.6 1637.52   126.4 1607.04   165.4 1593.63  238.231572.364
   252.9 1568.58   272.4 1564.58  294.581562.354   311.3 1560.89     321 1559.32
   330.7 1556.86   340.4 1553.36   350.2 1549.46   359.9 1547.37   369.6 1548.11
   380.1 1550.78   398.8 1556.19   408.5 1558.14   418.3 1558.99   437.7 1559.74
  529.111560.235   583.5 1563.07   611.11565.248   632.1 1567.05   651.6 1569.71
   748.8 1585.52   875.1  1607.5   904.3 1613.21   933.5 1621.17   972.3 1630.21
#Mann= 7 ,-1 , 0
       0     .12       0  238.23    .016       0  294.58     .12       0
   340.4    .045       0   380.1     .12       0  529.11    .016       0
   611.1     .12       0
Bank Sta=340.4,380.1
XS Rating Curve= 0 ,0
Exp/Cntr=0.3,0.1

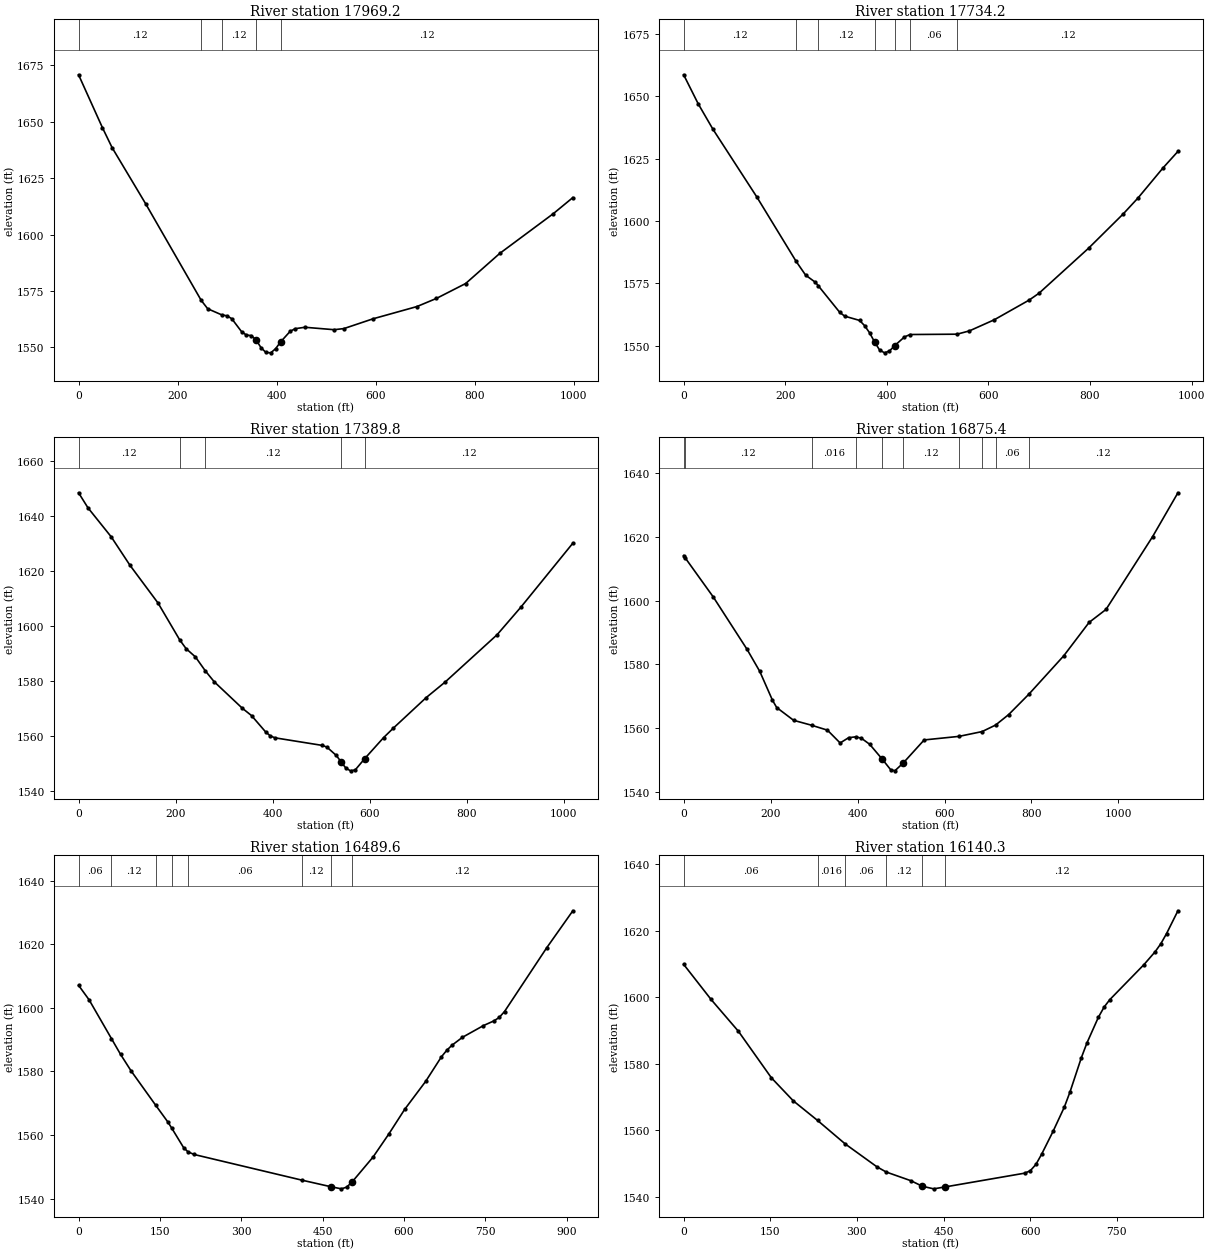
Type RM Length L Ch R = 1 ,17969.2 ,219.4,235,253.3
XS GIS Cut Line= 3
      1838065.19      229952.564     1838287.412      230138.328
      1838962.76      230351.869
#Sta/Elev= 30
       0 1670.87    48.3 1647.36    67.6 1638.61   135.2 1613.76  247.611570.831
   260.7 1567.12  289.371564.378   299.5    1564   309.3 1562.71     329 1556.98
   338.8 1555.45   348.7 1555.22   358.5 1553.27   368.3 1549.88   378.2 1547.74
     388 1547.57   397.8 1549.41   407.7 1552.37   427.4 1557.16   437.2 1558.27
   456.9 1558.91   515.9 1557.83   535.6 1558.32   594.6 1562.67   683.1 1568.09
   722.5  1571.7   781.5 1578.31   850.4 1591.67   958.6 1609.31   997.9 1616.42
#Mann= 5 ,-1 , 0
       0     .12       0  247.61    .016       0  289.37     .12       0
   358.5    .045       0   407.7     .12       0
#XS Ineff= 2 , 0
       0                     452       0
Permanent Ineff=
       F       F
Bank Sta=358.5,407.7
XS Rating Curve= 0 ,0
Exp/Cntr=0.3,0.1

Type RM Length L Ch R = 1 ,17734.2 ,330.7,344.4,358.1
XS GIS Cut Line= 4
     1837960.492      230045.477     1838167.621       230298.05
     1838395.051       230485.55      1838596.44      230773.744
#Sta/Elev= 30
       0 1658.68    28.8 1646.98    57.6 1636.86   144.1 1609.67  221.471583.848
   240.2 1578.32   259.4 1575.47  264.911574.115   307.4 1563.39     317  1561.9
   346.3 1560.19   356.1 1558.12   365.9 1555.27   375.8 1551.57   385.6 1548.36
   395.4 1547.19   405.2 1547.93   415.1 1550.02   434.7 1553.57  445.681554.535
  538.091554.667   562.4 1555.98   611.6 1560.46     680 1568.33   699.5 1571.08
   797.2 1589.16   865.6 1602.95   894.8 1609.37   943.7 1621.35     973 1627.95
#Mann= 7 ,-1 , 0
       0     .12       0  221.47    .016       0  264.91     .12       0
   375.8    .045       0   415.1     .12       0  445.68     .06       0
  538.09     .12       0
Bank Sta=375.8,415.1
XS Rating Curve= 0 ,0
Exp/Cntr=0.3,0.1

Type RM Length L Ch R = 1 ,17389.8 ,533.2,514.5,494.1
XS GIS Cut Line= 4
     1837895.051      230074.092     1837943.662       230485.55
     1838054.773      230679.994     1838308.388      230963.363
#Sta/Elev= 30
       0 1648.36    19.3 1642.91    67.4 1632.32     106 1621.99   163.8 1608.28
  208.451594.886   221.6 1591.71   240.9 1588.69  261.09 1583.67   279.4  1579.7
   337.2 1570.09   356.5 1567.37   385.4 1561.46     395 1560.02   404.7  1559.3
     502 1556.55   511.7 1555.94   531.2 1552.88   540.9 1550.59   550.6 1548.34
   560.4  1547.3   570.1 1547.63   589.6 1551.72   628.5 1559.36     648 1562.71
   716.3 1573.91   755.3 1579.55   862.5 1596.77   911.3 1606.75  1018.6 1630.04
#Mann= 5 ,-1 , 0
       0     .12       0  208.45    .016       0  261.09     .12       0
   540.9    .045       0   589.6     .12       0
Bank Sta=540.9,589.6
XS Rating Curve= 0 ,0
Exp/Cntr=0.3,0.1

Type RM Length L Ch R = 1 ,16875.4 ,403.2,385.8,367.3
XS GIS Cut Line= 4
     1837094.704      230522.008     1837500.954      230565.411
     1837632.898      230645.272     1838018.315      231070.619
#Sta/Elev= 30
       0 1614.16    3.281613.504    68.1 1601.18   145.9 1584.72   175.1 1577.81
   204.3 1568.76     214 1566.47   252.9 1562.46   294.21560.912   330.7 1559.37
   359.9 1555.35   379.4    1557  395.491557.271   408.6 1556.85   427.8 1554.94
   456.8 1550.26     476 1546.97   485.7  1546.6     505 1549.06   553.2  1556.3
  633.311557.418  686.441558.923  717.371560.964   747.6 1564.27  793.791570.628
   874.1 1582.69   932.5 1593.19   971.4 1597.26  1078.4 1620.08  1136.8 1633.88
#Mann= 10 ,-1 , 0
       0    .016       0    3.28     .12       0   294.2    .016       0
  395.49     .12       0   456.8    .045       0     505     .12       0
  633.31     .06       0  686.44     .12       0  717.37     .06       0
  793.79     .12       0
Bank Sta=456.8,505
XS Rating Curve= 0 ,0
Exp/Cntr=0.3,0.1

Type RM Length L Ch R = 1 ,16489.6 ,361.9,349.3,336.5
XS GIS Cut Line= 4
      1837089.16      230961.777      1837244.01      230962.981
      1837650.26      230995.967     1837988.801      231081.036
#Sta/Elev= 30
       0 1607.11    19.4 1602.55   60.571590.362    77.4 1585.39    96.8 1580.19
  142.371569.334   164.6 1564.11  171.991562.114   193.7 1556.03  201.671554.724
   213.1 1553.87  411.441545.811   465.4 1543.72   484.8 1543.06   494.4  1543.6
   504.2 1545.18     543 1553.05   572.1 1560.31   601.2 1568.03     640 1576.86
   669.1  1584.6   678.8 1586.63   688.5 1588.24   707.9 1590.75   746.7 1594.44
   766.1 1595.93   775.8 1597.01   785.5 1598.86     863 1618.85   911.5 1630.57
#Mann= 8 ,-1 , 0
       0     .06       0   60.57     .12       0  142.37    .016       0
  171.99     .12       0  201.67     .06       0  411.44     .12       0
   465.4    .045       0   504.2     .12       0
Bank Sta=465.4,504.2
XS Rating Curve= 0 ,0
Exp/Cntr=0.3,0.1

Type RM Length L Ch R = 1 ,16140.3 ,336.6,328.1,319.2
XS GIS Cut Line= 3
     1837124.218      231364.022     1837389.843      231374.439
     1837961.023      231226.869
#Sta/Elev= 30
       0 1609.86    47.5 1599.32    94.9 1589.75   151.9  1575.8   189.9 1568.87
  231.821563.004  279.711555.945   334.6 1549.08   350.71547.512   393.6 1544.89
   413.3 1543.23     433 1542.46   452.6 1543.03   590.3 1547.16   600.1 1547.88
     610 1549.81   619.8 1552.85   639.5 1559.68   659.1 1566.99     669 1571.58
   688.6 1581.84   698.4 1586.32   718.1 1593.98     728 1597.04   737.8 1599.26
   796.8 1609.75   816.4 1613.66   826.3 1616.08   836.1  1619.1   855.8 1625.95
#Mann= 6 ,-1 , 0
       0     .06       0  231.82    .016       0  279.71     .06       0
   350.7     .12       0   413.3    .045       0   452.6     .12       0
Bank Sta=413.3,452.6
XS Rating Curve= 0 ,0
Exp/Cntr=0.3,0.1

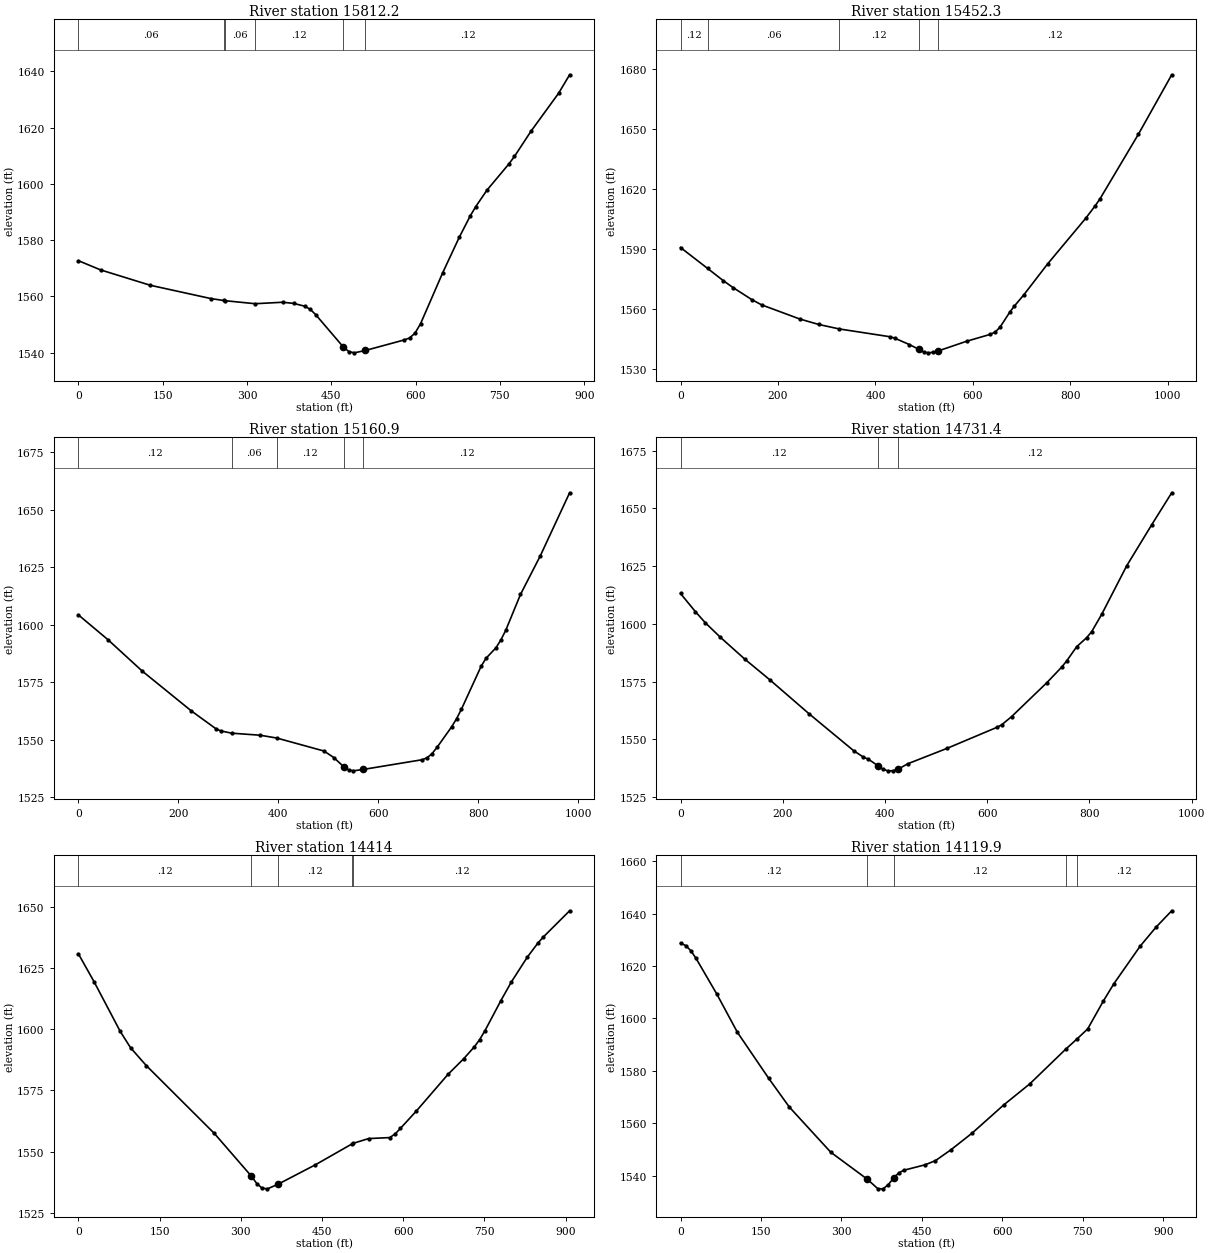
Type RM Length L Ch R = 1 ,15812.2 ,371.3,359.9,348
XS GIS Cut Line= 2
     1837280.468      231811.939     1838052.311      231401.847
#Sta/Elev= 30
       0 1572.67    39.3  1569.4   127.7 1563.93   235.7 1559.19  258.451558.504
  261.351558.425  314.35 1557.36   363.4 1557.88     383 1557.47   402.6 1556.48
   412.5 1555.36   422.3 1553.44   471.4 1541.95   481.2 1540.34     491 1539.88
   510.7 1540.73   579.4 1544.45   589.2 1545.17     599 1546.91   608.9  1550.3
   648.2 1568.39   677.6 1580.98   697.2 1588.62   707.1 1591.95   726.7 1597.71
     766 1607.11   775.8 1609.76   805.3 1618.75   854.4 1632.25     874 1638.82
#Mann= 6 ,-1 , 0
       0     .06       0  258.45     .12       0  261.35     .06       0
  314.35     .12       0   471.4    .045       0   510.7     .12       0
Bank Sta=471.4,510.7
XS Rating Curve= 0 ,0
Exp/Cntr=0.3,0.1

Type RM Length L Ch R = 1 ,15452.3 ,299.6,291.4,283.5
XS GIS Cut Line= 2
     1837528.732      232245.967     1838245.746      231537.633
#Sta/Elev= 30
       0 1590.62   55.761580.132    88.1    1574   107.6 1570.63   146.8 1564.52
   166.4 1561.97   244.6 1554.91   283.8 1552.16  325.781549.934   430.6 1546.01
   440.3 1545.25   469.7 1542.12   489.3 1539.72     499 1538.47   508.8    1538
   518.6 1538.26   528.4 1538.92   587.1 1543.79     636 1547.26   645.8 1548.43
   655.6  1550.8   675.2 1558.17     685 1561.35   704.6 1567.03   753.5 1582.49
   831.8 1605.33   851.3 1611.59   861.1 1615.08   939.4 1647.14  1007.9  1676.9
#Mann= 5 ,-1 , 0
       0     .12       0   55.76     .06       0  325.78     .12       0
   489.3    .045       0   528.4     .12       0
Bank Sta=489.3,528.4
XS Rating Curve= 0 ,0
Exp/Cntr=0.3,0.1

Type RM Length L Ch R = 1 ,15160.9 ,423.3,429.5,433.6
XS GIS Cut Line= 3
     1837796.093      232544.578     1838209.287      231898.744
     1838379.426      231765.064
#Sta/Elev= 30
       0 1604.28      59 1593.51   127.8 1579.82   226.1 1562.48   275.2 1554.73
   285.1 1553.79  306.611552.809   363.7 1551.92   396.81550.704   491.5 1545.04
   511.1  1542.2   530.8 1538.24   540.6 1536.82   550.4 1536.42   570.1 1537.03
   688.1 1541.26   697.9 1542.13   707.7 1543.89   717.6  1546.6     747 1555.58
   756.9 1559.14   766.7  1563.3     806 1581.93   815.9 1585.43   835.6 1589.95
   845.4 1593.33   855.2 1597.54   884.7 1613.16   924.1 1629.84   983.1 1657.42
#Mann= 5 ,-1 , 0
       0     .12       0  306.61     .06       0   396.8     .12       0
   530.8    .045       0   570.1     .12       0
Bank Sta=530.8,570.1
XS Rating Curve= 0 ,0
Exp/Cntr=0.3,0.1

Type RM Length L Ch R = 1 ,14731.4 ,330.5,317.3,304.9
XS GIS Cut Line= 4
     1838197.135      232772.008     1838254.426      232487.286
     1838445.825       232270.85     1838606.857      231924.786
#Sta/Elev= 30
       0 1613.16      29 1605.34    48.4 1600.53    77.4 1594.34   125.8 1584.76
   174.3  1575.9   251.7 1561.09   338.6 1545.18   357.8 1542.37   367.5 1541.48
   386.7 1538.58   396.4 1537.06     406 1536.44   415.6 1536.46   425.3  1537.1
   444.5 1539.49   521.6 1546.18   618.5 1555.21   628.3 1556.34   647.9 1559.93
   716.4 1574.51   745.7  1581.3   755.5 1583.99   775.1 1590.15   794.7 1594.07
   804.5 1596.68     824 1604.14     873 1625.17   921.9 1642.91     961 1656.73
#Mann= 3 ,-1 , 0
       0     .12       0   386.7    .045       0   425.3     .12       0
Bank Sta=386.7,425.3
XS Rating Curve= 0 ,0
Exp/Cntr=0.3,0.1

Type RM Length L Ch R = 1 ,14414   ,302.5,294.1,285.7
XS GIS Cut Line= 4
     1838532.204      232874.439     1838578.608      232617.995
     1838676.301      232370.967     1838768.315      232001.175
#Sta/Elev= 30
       0  1630.8      29 1619.38    77.2 1599.12    96.5 1592.38   125.5 1585.11
     251 1557.43   319.6 1539.92   329.5 1536.92   339.3 1535.03   349.2 1534.77
   368.8 1536.66   437.7  1544.6   505.11553.098  508.071553.409     536 1555.31
   575.1 1555.72   584.9 1557.19   594.6 1559.44     624 1566.52   682.6 1581.54
   711.9    1588   731.4 1592.83   741.2 1595.79     751 1599.44   780.3 1611.68
   799.8 1619.36   829.2 1629.48   848.7  1635.2   858.5 1637.65   907.3 1648.41
#Mann= 5 ,-1 , 0
       0     .12       0   319.6    .045       0   368.8     .12       0
   505.1     .06       0  508.07     .12       0
Bank Sta=319.6,368.8
XS Rating Curve= 0 ,0
Exp/Cntr=0.3,0.1

Type RM Length L Ch R = 1 ,14119.9 ,301.7,297.2,292.3
XS GIS Cut Line= 4
     1838872.482      232928.258     1838884.635      232667.842
     1838924.447      232407.407     1838895.051        232016.8
#Sta/Elev= 30
       0 1628.74     9.7 1627.79    19.3 1625.83      29 1622.89    67.6 1609.34
   106.2 1594.69   164.1 1577.29   202.8 1566.27   280.2 1549.01   348.5  1538.7
     368  1535.1   377.8 1535.07   387.6  1536.7   397.3 1539.19   407.1 1541.18
   416.8 1542.18   455.9 1544.22   475.4 1545.82   504.6 1550.01   543.8 1556.32
   602.5 1567.02   651.5 1575.12  718.351588.318  739.091592.151   759.2 1596.02
   788.6 1606.72   808.2 1613.29   857.1 1627.58   886.5 1634.77   915.9 1641.05
#Mann= 5 ,-1 , 0
       0     .12       0   348.5    .045       0   397.3     .12       0
  718.35    .016       0  739.09     .12       0
Bank Sta=348.5,397.3
XS Rating Curve= 0 ,0
Exp/Cntr=0.3,0.1

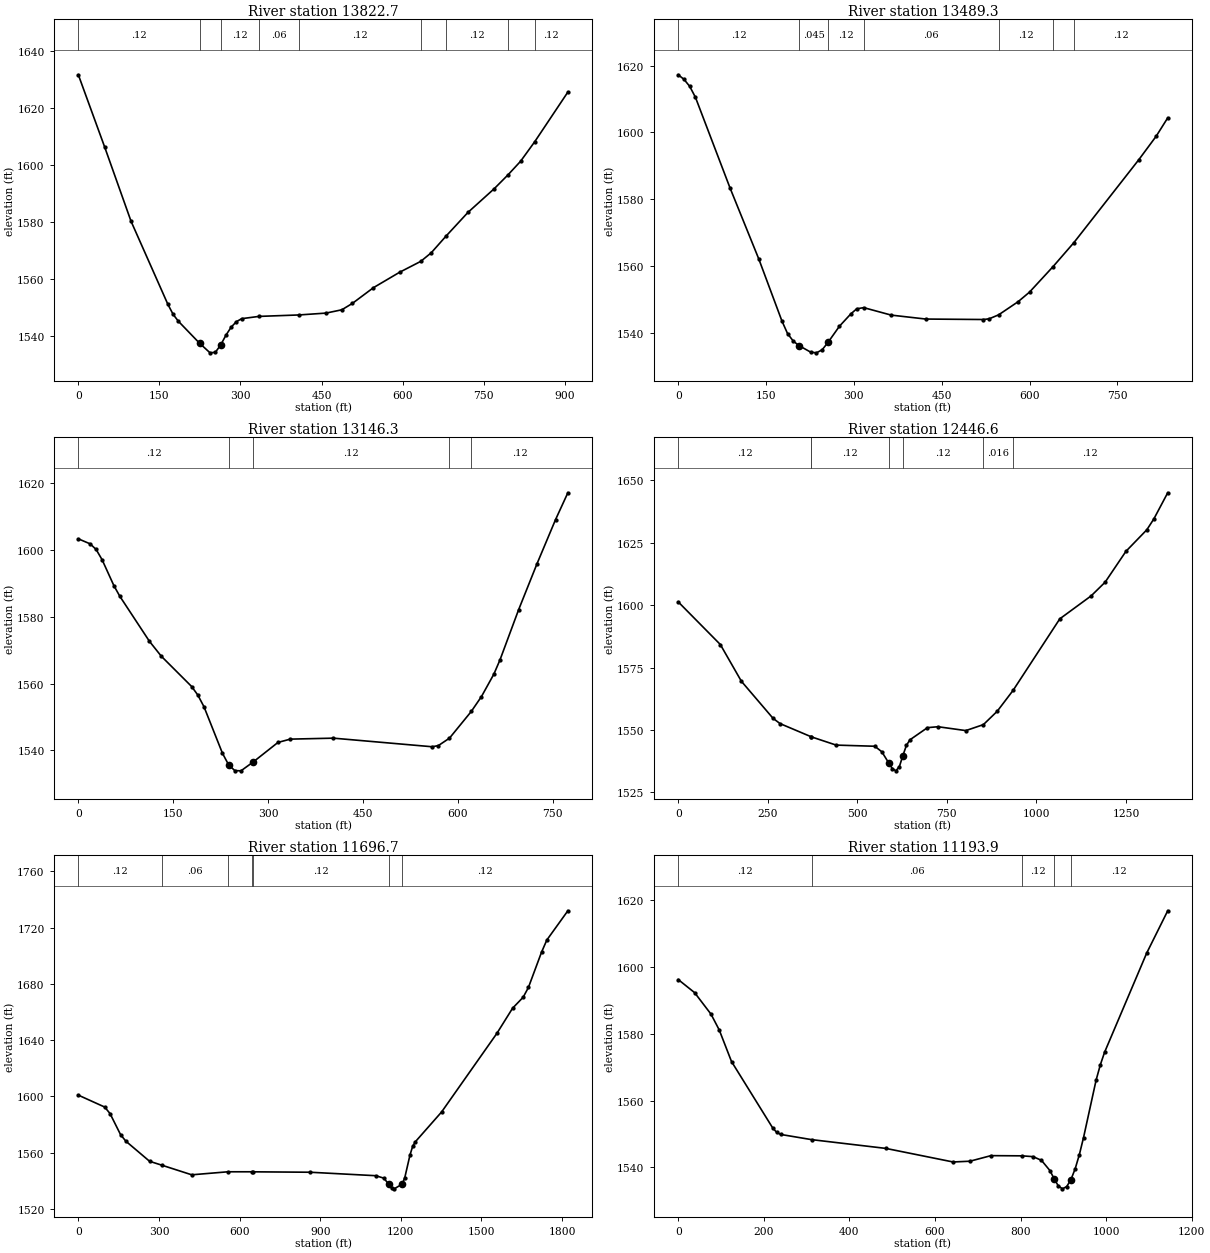
Type RM Length L Ch R = 1 ,13822.7 ,345.4,333.4,321.2
XS GIS Cut Line= 3
     1839173.697      232903.085     1839188.454      232386.592
     1839106.857      232006.383
#Sta/Elev= 30
       0  1631.5    48.8 1606.15    97.5  1580.2   165.7 1551.08   175.5 1547.54
   185.2 1545.15   224.2 1537.49   243.7 1534.11   253.5 1534.31   263.2 1536.81
     273 1540.27   282.7  1543.1   292.5 1545.04   302.2 1546.08  334.121546.873
  408.221547.381   458.2 1548.03   487.5 1549.19     507 1551.43   545.9 1556.93
   594.5 1562.35  633.421566.143   652.8 1569.14  680.151574.979   720.9 1583.32
   769.5 1591.62  794.93 1596.46   818.1  1601.2  844.411608.085   905.6 1625.44
#Mann= 9 ,-1 , 0
       0     .12       0   224.2    .045       0   263.2     .12       0
  334.12     .06       0  408.22     .12       0  633.42    .016       0
  680.15     .12       0  794.93    .016       0  844.41     .12       0
Bank Sta=224.2,263.2
XS Rating Curve= 0 ,0
Exp/Cntr=0.3,0.1

Type RM Length L Ch R = 1 ,13489.3 ,343.7,343.1,343.3
XS GIS Cut Line= 2
     1839572.135      232843.189     1839311.718      232048.918
#Sta/Elev= 30
       0 1617.28     9.8 1615.93    19.7  1613.8    29.5 1610.51    88.5 1583.36
   137.7 1562.03     177 1543.53   186.8 1539.67   196.7  1537.4   206.5 1536.07
   226.2 1534.13     236 1533.92   245.8 1534.83   255.7 1537.02   275.4 1541.91
     295 1545.63   304.8 1547.11  316.731547.473   363.8 1545.23   422.8 1544.05
   521.2 1543.91     531 1544.12   547.21545.317   580.2 1549.22   599.9 1552.12
  640.15 1559.78  675.561566.937   786.7 1591.86   816.2 1598.86   835.9 1604.36
#Mann= 7 ,-1 , 0
       0     .12       0   206.5    .045       0   255.7     .12       0
  316.73     .06       0   547.2     .12       0  640.15    .016       0
  675.56     .12       0
Bank Sta=206.5,255.7
XS Rating Curve= 0 ,0
Exp/Cntr=0.3,0.1

Type RM Length L Ch R = 1 ,13146.3 ,662,699.7,736.8
XS GIS Cut Line= 3
     1839848.176      232707.772     1839827.343      232559.335
      1839619.01      231970.793
#Sta/Elev= 30
       0 1603.27    18.7 1601.77    28.1  1600.1    37.5 1597.06    56.2 1589.29
    65.6  1586.1   112.4 1572.65   131.2 1568.18   179.2 1559.12   188.9 1556.59
   198.7 1553.08   227.9 1539.18   237.7  1535.7   247.4 1533.99   257.2 1533.91
   276.7 1536.58   315.7  1542.4   335.2 1543.39   403.5 1543.68   559.6 1541.11
   569.4 1541.46  586.971543.679   621.41551.652   637.6 1556.13   657.2 1562.83
   666.9  1567.1   696.2 1582.02   725.4 1595.82   754.7 1609.01   774.2 1617.04
#Mann= 5 ,-1 , 0
       0     .12       0   237.7    .045       0   276.7     .12       0
  586.97    .016       0   621.4     .12       0
Bank Sta=237.7,276.7
XS Rating Curve= 0 ,0
Exp/Cntr=0.3,0.1

Type RM Length L Ch R = 1 ,12446.6 ,728.2,749.9,771
XS GIS Cut Line= 3
     1839884.635       232699.96     1840345.572      232140.064
     1840257.925      231504.879
#Sta/Elev= 30
       0 1601.31   117.6 1584.22   176.4  1569.5   264.6 1554.68   284.2 1552.55
  370.951547.284  371.591547.238     441 1543.93   548.8 1543.47   568.4 1541.25
     588 1536.71   597.7 1534.54   607.6 1533.62   617.4 1535.32   627.2 1539.74
     637  1543.8   646.8 1546.04   695.8 1550.92   725.2 1551.29   802.9 1549.74
  851.891552.133   890.4 1557.47   934.81565.851  1065.2 1594.51  1152.7 1603.71
  1191.6 1609.17  1249.8 1621.55  1308.1 1630.18  1327.6  1634.5  1366.4    1645
#Mann= 7 ,-1 , 0
       0     .12       0  370.95     .06       0  371.59     .12       0
     588    .045       0   627.2     .12       0  851.89    .016       0
   934.8     .12       0
Bank Sta=588,627.2
XS Rating Curve= 0 ,0
Exp/Cntr=0.3,0.1

Type RM Length L Ch R = 1 ,11696.7 ,486.6,502.8,520.1
XS GIS Cut Line= 3
     1839908.072      232702.564     1840121.614      232499.439
     1841575.634      232033.525
#Sta/Elev= 30
       0 1600.91    98.2 1592.43   117.9 1587.82   157.2 1572.82   176.8 1568.19
   265.2 1553.89  309.941551.178     422 1544.29  556.66 1546.44  647.761546.434
  649.431546.418   862.4 1546.12  1107.1 1543.65  1136.4 1541.93    1156 1537.47
  1165.8 1534.79  1175.4 1534.32    1205 1537.68  1214.7 1542.19  1234.3 1558.51
  1244.1  1564.5  1253.9 1567.74  1351.8 1588.96  1557.3 1644.75    1616  1662.7
  1655.2 1670.46  1674.8  1677.4  1723.7 1702.52  1743.3 1711.12  1821.6 1731.92
#Mann= 7 ,-1 , 0
       0     .12       0  309.94     .06       0  556.66     .12       0
  647.76     .06       0  649.43     .12       0    1156    .045       0
    1205     .12       0
Bank Sta=1156,1205
XS Rating Curve= 0 ,0
Exp/Cntr=0.3,0.1

Type RM Length L Ch R = 1 ,11193.9 ,638.6,654.4,667.8
XS GIS Cut Line= 3
     1839936.718      232718.189     1840173.697      232614.022
     1841048.697      232746.835
#Sta/Elev= 30
       0 1596.26    38.4 1592.33    76.7 1585.89    95.9 1581.17   124.6 1571.71
   220.5  1551.9   230.1  1550.5   239.7 1549.88   311.7 1548.33     485 1545.71
   642.4 1541.64   681.7 1541.87   730.9 1543.54  803.131543.479   829.2 1543.24
   848.9 1542.13   868.5 1539.09   878.4 1536.65   888.2 1534.48     898  1533.6
   907.9 1534.29   917.7 1536.35   927.6 1539.59   937.4 1543.83   947.2 1548.96
   976.7 1566.22   986.6  1570.8   996.4  1574.5  1094.7 1604.16  1143.9 1616.84
#Mann= 5 ,-1 , 0
       0     .12       0   311.7     .06       0  803.13     .12       0
   878.4    .045       0   917.7     .12       0
Bank Sta=878.4,917.7
XS Rating Curve= 0 ,0
Exp/Cntr=0.3,0.1

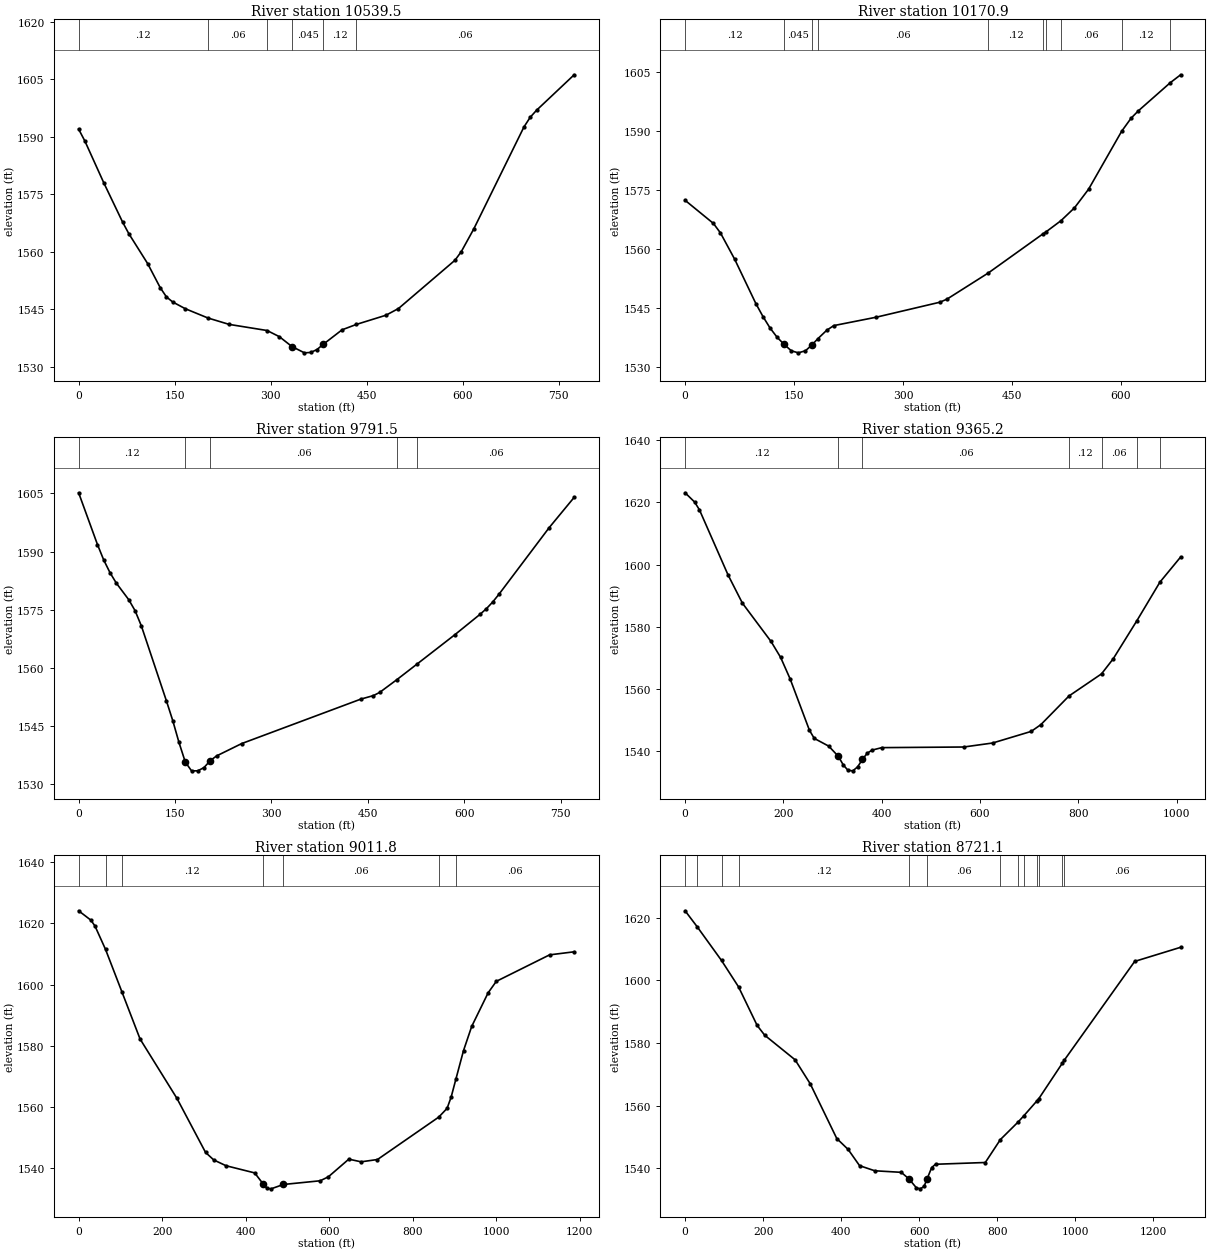
Type RM Length L Ch R = 1 ,10539.5 ,357.1,368.6,381
XS GIS Cut Line= 2
     1839928.905      232744.231     1840548.697      233207.772
#Sta/Elev= 30
       0 1592.04     9.8 1588.92    39.2 1578.07    68.6 1567.82    78.4 1564.77
   107.8 1556.97   127.4  1550.7   137.2 1548.27     147 1546.95   166.6  1545.2
   202.11542.772   235.1 1541.11  294.351539.513   313.5 1537.91   333.1 1535.34
   352.7 1533.69   362.5 1533.79   372.3 1534.55   382.1 1535.92   411.5  1539.7
  433.981541.112     480  1543.5   499.6 1545.25   587.8 1557.84   597.6 1560.06
   617.2 1566.01   695.6 1592.62   705.4 1595.15   715.2 1596.96     774 1606.22
#Mann= 6 ,-1 , 0
       0     .12       0   202.1     .06       0  294.35     .12       0
   333.1    .045       0   382.1     .12       0  433.98     .06       0
Bank Sta=333.1,382.1
XS Rating Curve= 0 ,0
Exp/Cntr=0.3,0.1

Type RM Length L Ch R = 1 ,10170.9 ,395.2,379.4,363.7
XS GIS Cut Line= 2
     1839764.843      232973.397     1840223.176      233478.606
#Sta/Elev= 30
       0 1572.37      39 1566.48    48.7 1564.06    68.2 1557.39    97.4 1546.09
   107.2 1542.78   116.9 1539.88   126.7  1537.5   136.4 1535.69   146.2 1534.07
   155.9 1533.55   165.7 1534.08   174.1 1535.48  183.011537.191   194.9 1539.29
   204.6 1540.48   263.1 1542.62   350.8 1546.44   360.6 1547.23  417.411553.885
  492.341563.795  497.141564.388   517.41567.188     536 1570.46   555.4  1575.2
  600.891589.937   613.9 1593.27   623.7 1595.11  667.851602.305   682.1 1604.32
#Mann= 10 ,-1 , 0
       0     .12       0   136.4    .045       0   174.1     .12       0
  183.01     .06       0  417.41     .12       0  492.34     .06       0
  497.14     .12       0   517.4     .06       0  600.89     .12       0
  667.85     .06       0
Bank Sta=136.4,174.1
XS Rating Curve= 0 ,0
Exp/Cntr=0.3,0.1

Type RM Length L Ch R = 1 ,9791.5  ,440.6,426.3,411.7
XS GIS Cut Line= 2
     1839457.551      233298.918      1840163.28      233608.814
#Sta/Elev= 30
       0 1605.18    29.3 1591.82      39 1587.85    48.8 1584.56    58.5  1581.9
      78 1577.58    87.8 1574.76    97.6 1570.82   136.6 1551.46   146.4  1546.4
   156.1 1540.75   165.9  1535.7   175.6 1533.43   185.4 1533.43   195.1 1534.29
   204.9 1536.09   214.6 1537.28   253.7 1540.47     439 1551.94   458.6 1552.85
   468.3 1553.67  494.741556.925  526.071560.943   585.4 1568.58   624.4 1573.82
   634.2 1575.26   643.9 1576.96   653.7 1578.97   731.8 1596.16   770.8    1604
#Mann= 5 ,-1 , 0
       0     .12       0   165.9    .045       0   204.9     .06       0
  494.74     .12       0  526.07     .06       0
Bank Sta=165.9,204.9
XS Rating Curve= 0 ,0
Exp/Cntr=0.3,0.1

Type RM Length L Ch R = 1 ,9365.2  ,331.5,353.4,375.4
XS GIS Cut Line= 3
     1839197.135      233650.481     1839374.218      233770.272
     1840168.489       233793.71
#Sta/Elev= 30
       0 1623.12    19.4 1620.13    29.2 1617.62    87.5 1596.61   116.6 1587.55
   174.9 1575.19   194.4 1570.06   213.8 1563.11     253 1546.59   262.8 1543.96
   292.3 1541.46   311.9 1538.17   321.7 1535.44   331.5 1533.66   341.3  1533.5
   351.1 1534.79     361 1537.21   370.8 1539.21   380.6 1540.18   400.2 1540.98
     567 1541.18   625.8 1542.47   704.3 1546.21   723.9 1548.38  781.261557.636
  847.381564.755   871.1 1569.59  919.121581.826  966.191594.306  1008.4 1602.42
#Mann= 7 ,-1 , 0
       0     .12       0   311.9    .045       0     361     .06       0
  781.26     .12       0  847.38     .06       0  919.12     .12       0
  966.19     .06       0
Bank Sta=311.9,361
XS Rating Curve= 0 ,0
Exp/Cntr=0.3,0.1

Type RM Length L Ch R = 1 ,9011.8  ,290.6,290.7,291.7
XS GIS Cut Line= 3
      1839056.51      233858.814     1839733.593      234327.564
     1839842.968      234673.918
#Sta/Elev= 30
       0 1624.09    29.4 1621.02    39.2  1619.1    64.41611.486  103.741597.586
   147.1 1582.24   235.3 1562.88   303.9 1545.22   323.5 1542.76   352.9 1540.87
   421.6 1538.52   441.2 1535.04     451  1533.5   460.8 1533.32   490.2 1534.74
   578.4 1535.95     598 1537.24     647 1543.01   676.4 1542.14   715.7 1542.89
  862.391556.737   882.4  1559.6   892.2 1563.33  903.611569.221   921.7 1578.45
   941.3 1586.34   980.6  1597.3  1000.2 1601.05  1127.8  1609.7  1186.7  1610.7
#Mann= 7 ,-1 , 0
       0     .12       0    64.4    .016       0  103.74     .12       0
   441.2    .045       0   490.2     .06       0  862.39    .016       0
  903.61     .06       0
Bank Sta=441.2,490.2
XS Rating Curve= 0 ,0
Exp/Cntr=0.3,0.1

Type RM Length L Ch R = 1 ,8721.1  ,288.7,300,303.3
XS GIS Cut Line= 3
     1838801.777      234022.929     1839301.365      234377.165
     1839829.015      234769.822
#Sta/Elev= 30
       0 1622.21   31.041617.092   93.371606.335  136.92 1597.93   184.7 1585.59
   204.1 1582.47   281.9 1574.63   320.8 1566.95   388.8 1549.49     418 1545.99
   447.2 1540.82   486.1 1539.19   554.1 1538.69   573.6 1536.62     593 1533.73
   602.7 1533.42   612.4 1534.17   619.9 1536.48   632.1 1540.23   641.9 1541.27
   769.5 1541.83  808.171549.154  853.911554.798  867.681556.667  902.311561.571
  906.661562.214  966.92 1573.53  971.391574.405  1152.4 1606.04  1270.2 1610.55
#Mann= 13 ,-1 , 0
       0     .06       0   31.04     .12       0   93.37    .016       0
  136.92     .12       0   573.6    .045       0   619.9     .06       0
  808.17    .016       0  853.91     .12       0  867.68     .06       0
  902.31     .12       0  906.66     .06       0  966.92     .12       0
  971.39     .06       0
Bank Sta=573.6,619.9
XS Rating Curve= 0 ,0
Exp/Cntr=0.3,0.1