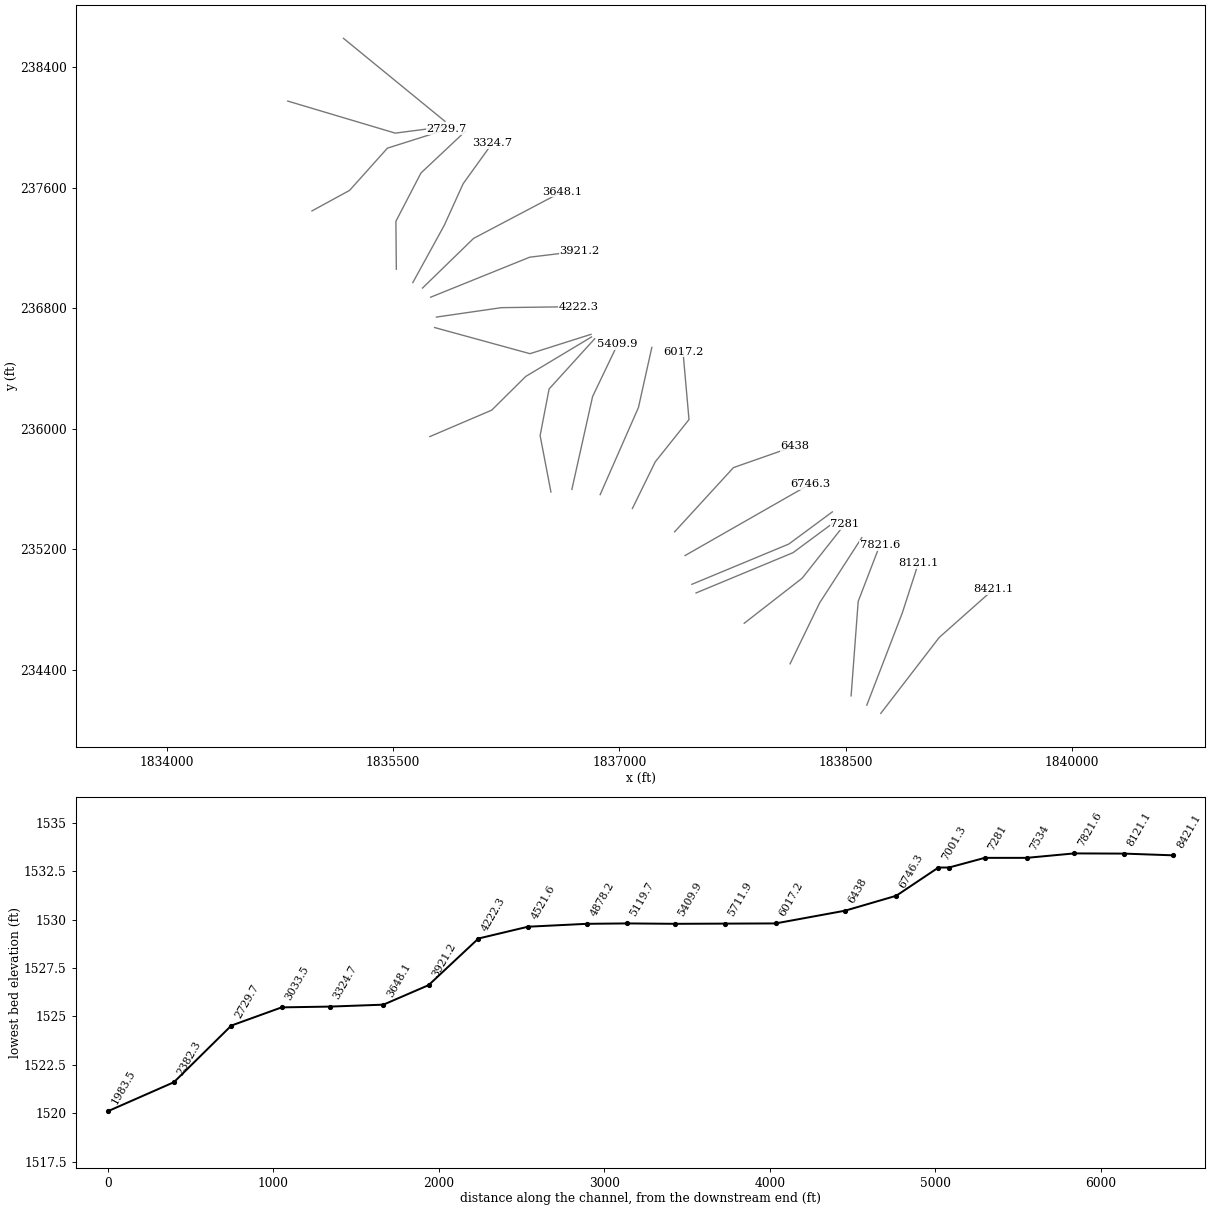
HEC-RAS study SUGARCK.prj: SUGARCK

--- SUGARCK.g01 (geometry) --- (continued)

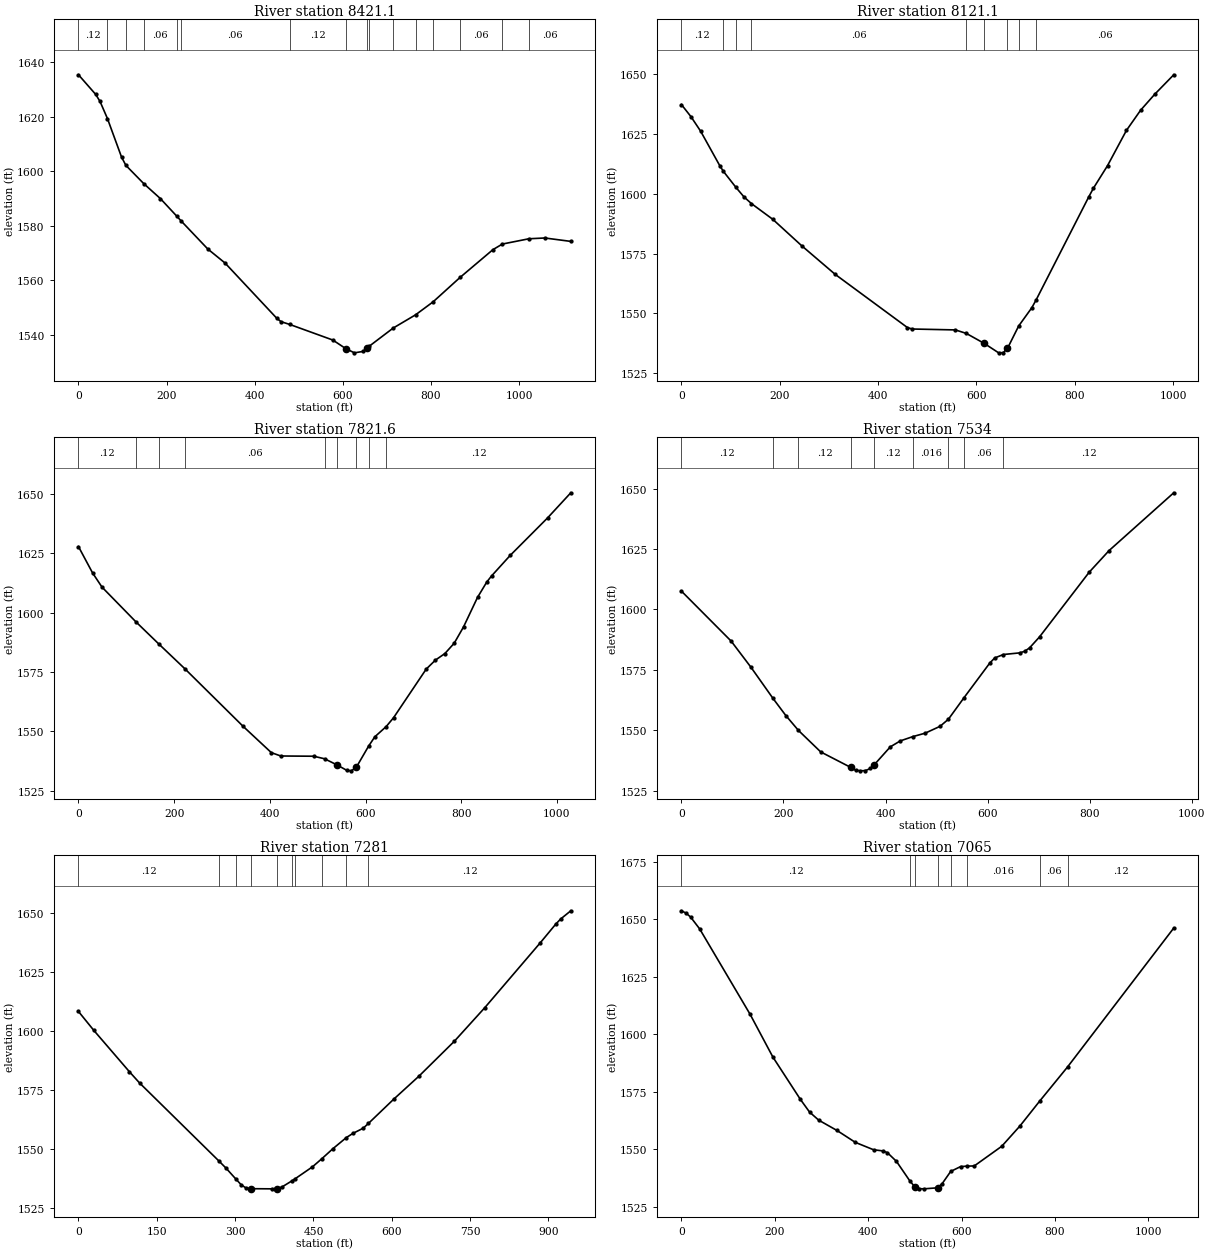
Type RM Length L Ch R = 1 ,8421.1  ,289.2,300,320
XS GIS Cut Line= 3
     1838731.275      234110.815     1839118.753      234615.097
     1839478.471      234934.956
#Sta/Elev= 30
       0 1635.45    39.1 1628.24    48.9 1625.66   65.76 1619.37    97.8  1605.2
  107.681602.164  148.161595.478   185.9 1589.98  223.211583.501  232.38 1581.87
   293.5 1571.46   332.6 1566.32   450.1 1546.01   459.8 1544.77  479.061543.783
   577.2 1538.03   606.6 1534.88   626.2 1533.33   645.8 1533.85   655.6  1535.2
  659.341535.696  714.191542.426  765.021547.293  804.931552.076  865.991561.027
   940.5 1571.22  962.021573.285 1022.261575.225  1058.4 1575.51  1117.3 1574.26
#Mann= 16 ,-1 , 0
       0     .12       0   65.76    .016       0  107.68     .12       0
  148.16     .06       0  223.21     .12       0  232.38     .06       0
  479.06     .12       0   606.6    .045       0   655.6     .12       0
  659.34     .06       0  714.19    .016       0  765.02     .06       0
  804.93     .12       0  865.99     .06       0  962.02     .12       0
 1022.26     .06       0
Bank Sta=606.6,655.6
XS Rating Curve= 0 ,0
Exp/Cntr=0.3,0.1

Type RM Length L Ch R = 1 ,8121.1  ,288.5,299.5,308.3
XS GIS Cut Line= 3
     1838638.741      234165.494     1838873.666      234776.928
     1838979.978      235106.502
#Sta/Elev= 30
       0 1637.41    19.6 1632.29    39.1 1626.25    78.2 1611.74   85.431609.416
  110.891602.718   127.1 1598.76  142.341595.941   185.8 1589.35   244.4 1578.32
   312.8 1566.28   459.5 1544.03   469.3  1543.4   557.2 1543.02  579.361541.563
   615.9 1537.37   645.2 1533.42     655 1533.52   662.5 1535.36   664.6 1535.88
  685.921544.669   712.7 1552.33  721.561555.646   828.2 1598.64   837.8 1602.33
   866.6 1611.81   905.1 1626.59     934 1635.06   962.8 1641.76  1001.3 1649.88
#Mann= 9 ,-1 , 0
       0     .12       0   85.43    .016       0  110.89     .12       0
  142.34     .06       0  579.36     .12       0   615.9    .045       0
   662.5     .12       0  685.92    .016       0  721.56     .06       0
Bank Sta=615.9,662.5
XS Rating Curve= 0 ,0
Exp/Cntr=0.3,0.1

Type RM Length L Ch R = 1 ,7821.6  ,303.3,287.6,270.5
XS GIS Cut Line= 3
     1838534.663      234226.995     1838581.683      234854.474
     1838724.912      235227.737
#Sta/Elev= 30
       0 1627.81    29.5 1616.72    49.2 1610.75  120.051596.145  168.581586.692
  221.981576.465   344.1 1552.16   403.1 1541.09   422.8 1539.68   491.6 1539.58
  514.221538.516   540.8 1535.88   560.4 1533.67   570.2 1533.43   580.7 1534.93
  606.631543.911   619.4 1547.76  643.081552.051   658.5 1555.77   726.8 1576.26
   746.2 1580.06   765.8 1582.79   785.3 1587.15   804.8 1594.01     834 1606.42
   853.5 1612.94   863.3 1615.44   902.3  1624.1   980.3 1639.85    1029 1650.46
#Mann= 9 ,-1 , 0
       0     .12       0  120.05    .016       0  168.58     .12       0
  221.98     .06       0  514.22     .12       0   540.8    .045       0
   580.7     .12       0  606.63    .016       0  643.08     .12       0
Bank Sta=540.8,580.7
XS Rating Curve= 0 ,0
Exp/Cntr=0.3,0.1

Type RM Length L Ch R = 1 ,7534    ,268.8,253,238.2
XS GIS Cut Line= 3
     1838130.294      234439.977     1838325.607      234843.623
     1838605.555      235277.651
#Sta/Elev= 30
       0 1607.56    97.5 1586.87   136.5    1576  179.571563.145   204.7 1556.06
  229.411549.912     273 1541.03   331.4 1534.67   341.2 1533.48   350.9  1533.2
   360.7 1533.31   370.4 1534.17   376.9 1535.48   409.4 1543.12   428.9 1545.58
  453.861547.383   477.6 1548.77   506.9 1551.62  523.261554.549  553.68 1563.41
   604.3 1577.78   614.1 1579.92  631.141581.329   662.8    1582   672.6 1582.65
   682.3 1584.07   701.8  1588.6   799.2 1615.38   838.2 1624.34   964.9 1648.24
#Mann= 9 ,-1 , 0
       0     .12       0  179.57    .016       0  229.41     .12       0
   331.4    .045       0   376.9     .12       0  453.86    .016       0
  523.26     .12       0  553.68     .06       0  631.14     .12       0
Bank Sta=331.4,376.9
XS Rating Curve= 0 ,0
Exp/Cntr=0.3,0.1

Type RM Length L Ch R = 1 ,7281    ,226,216,205.8
XS GIS Cut Line= 3
     1837826.475      234709.074     1838210.589      235008.553
     1838492.707      235366.626
#Sta/Elev= 30
       0 1608.43    29.2 1600.46    97.4 1582.91   116.9 1578.13  268.841545.035
   282.5    1542  302.141537.187   311.7 1534.91   321.5 1533.46   331.2 1533.26
   370.2  1533.2   379.9 1533.32   389.6 1533.97  408.411536.528  414.251537.366
   448.1 1542.53  465.841545.925   487.1 1550.19   513.11554.959   525.9 1556.75
   545.3 1558.92  555.19 1560.92   603.4 1571.15     652 1580.98   719.8 1595.78
     778    1610   884.7 1637.63   913.8 1645.41   923.5 1647.66   942.9 1651.14
#Mann= 10 ,-1 , 0
       0     .12       0  268.84     .06       0  302.14    .016       0
   331.2    .045       0   379.9     .04       0  408.41     .12       0
  414.25    .016       0  465.84     .12       0   513.1    .016       0
  555.19     .12       0
Bank Sta=331.2,379.9
XS Rating Curve= 0 ,0
Exp/Cntr=0.3,0.1

Type RM Length L Ch R = 1 ,7065    ,63.7,63.7,63.7
XS GIS Cut Line= 3
     1837507.464      234910.463     1838149.826      235177.824
      1838438.02      235391.366
#Sta/Elev= 30
       0 1653.75     9.8 1652.75    19.6 1651.04    39.2 1645.83     147 1608.73
     196 1590.04   254.8 1571.65   274.4 1566.14     294 1562.61   333.2 1558.11
   372.4 1552.94   411.6 1549.71   431.2 1549.22     441 1548.48   460.6 1544.66
  489.01 1536.22   499.8 1533.58   509.6 1532.77   519.4  1532.7   548.8 1533.15
   558.6 1534.99   576.81540.284   597.8 1542.37  612.671542.604   627.2 1542.66
     686 1551.21   724.9 1560.02  767.161570.849  826.961585.735  1054.5 1646.23
#Mann= 8 ,-1 , 0
       0     .12       0  489.01    .016       0   499.8    .045       0
   548.8     .04       0   576.8     .06       0  612.67    .016       0
  767.16     .06       0  826.96     .12       0
Bank Sta=499.8,548.8
XS Rating Curve= 0 ,0
Exp/Cntr=0.3,0.1

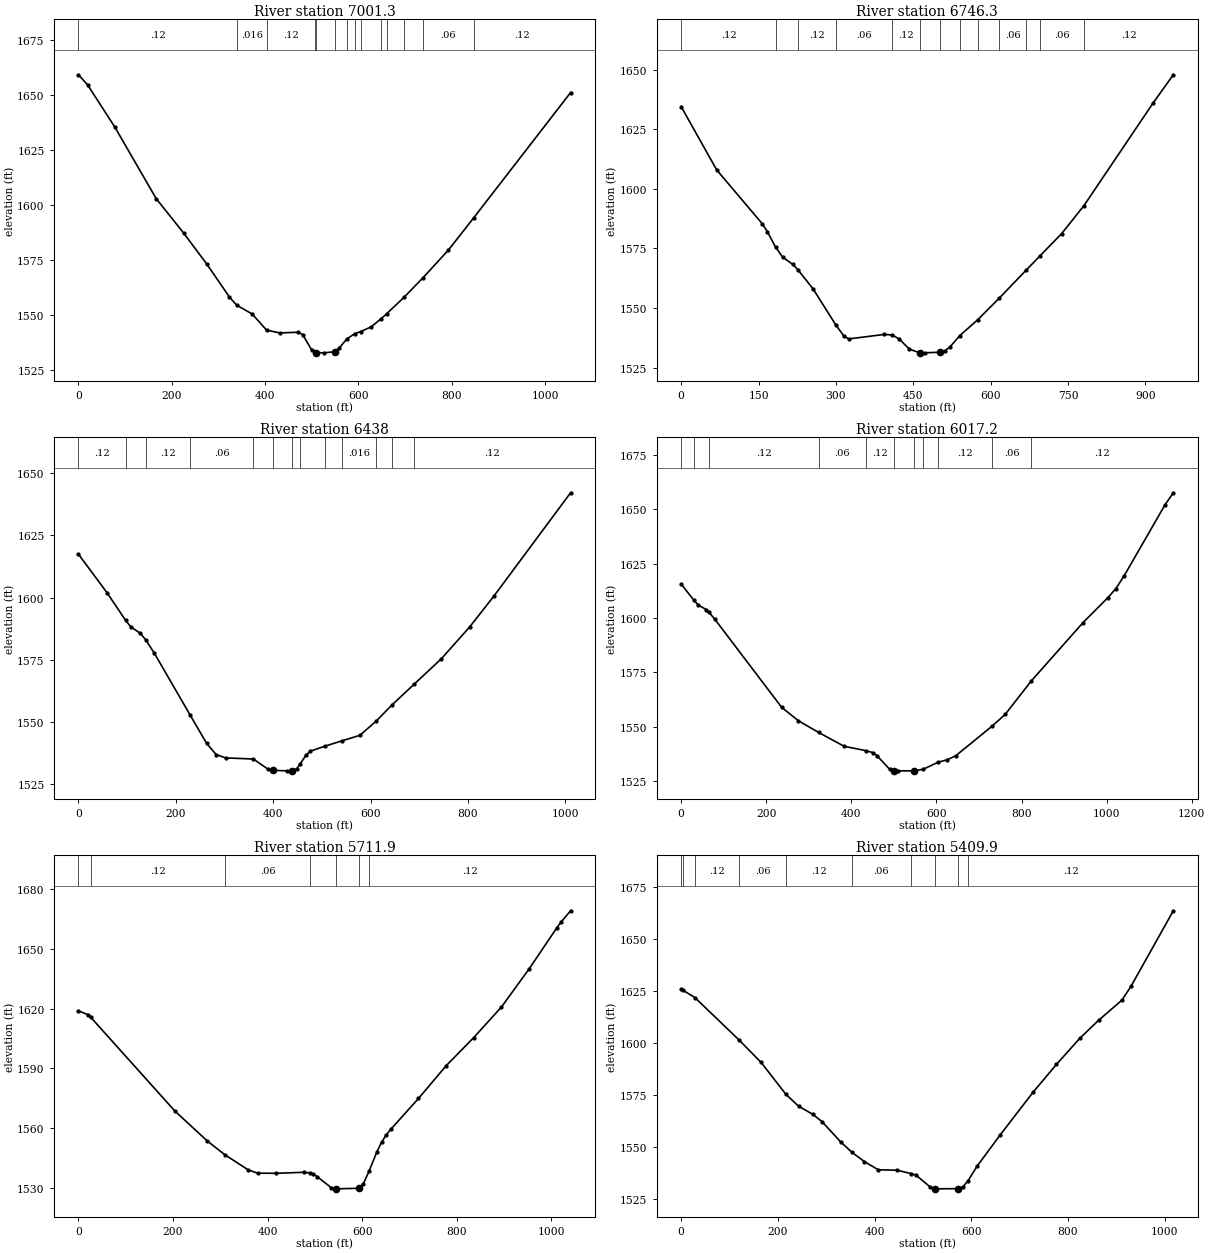
Type RM Length L Ch R = 1 ,7001.3  ,250.3,255,259.7
XS GIS Cut Line= 3
     1837479.687      234967.755     1838122.048      235235.116
     1838410.242      235448.658
#Sta/Elev= 30
       0 1659.32    19.6 1654.73    78.4 1635.35   166.6 1602.91   225.4 1587.24
   274.4 1573.29   323.4 1558.14  338.861554.429   372.4 1550.36  403.061543.047
   431.2 1541.77   470.4 1542.07   480.2 1541.05   499.8    1534  506.791533.144
   509.6  1532.8   525.1  1532.7   548.8 1533.17   558.6 1534.81     5751539.042
   592.81541.506  604.621542.395   627.2 1544.52     6491548.335  660.191550.455
  697.191557.905  738.171566.871   792.7  1579.5  847.071594.234  1054.5 1651.21
#Mann= 14 ,-1 , 0
       0     .12       0  338.86    .016       0  403.06     .12       0
  506.79    .016       0   509.6    .045       0   548.8     .04       0
     575    .016       0   592.8     .06       0  604.62     .12       0
     649     .06       0  660.19     .12       0  697.19    .016       0
  738.17     .06       0  847.07     .12       0
#XS Ineff= 2 , 0
       0     460                       0
Permanent Ineff=
       F       F
Bank Sta=509.6,548.8
XS Rating Curve= 0 ,0
Exp/Cntr=0.3,0.1

Type RM Length L Ch R = 1 ,6746.3  ,296.6,308.3,319.9
XS GIS Cut Line= 2
     1837434.548      235158.727     1838262.673      235632.685
#Sta/Elev= 30
       0 1634.44    68.9 1607.91   157.4 1585.31   167.2 1582.02  183.291575.458
   196.7 1571.36   216.4 1568.34  226.891565.929   255.8 1558.03  299.651543.005
   314.8 1538.47   324.6 1537.07   393.5 1538.95  409.561538.739     423 1536.96
   442.6  1532.8   462.3 1531.26   472.2 1531.24   501.7 1531.52   511.5 1532.14
   521.4 1533.77   540.51538.508   574.91545.095  616.551554.133  669.441566.022
  696.071571.966   737.8 1581.24  780.831592.908   914.8 1635.89   954.2  1647.8
#Mann= 13 ,-1 , 0
       0     .12       0  183.29    .016       0  226.89     .12       0
  299.65     .06       0  409.56     .12       0   462.3    .045       0
   501.7     .04       0   540.5     .12       0   574.9    .016       0
  616.55     .06       0  669.44     .12       0  696.07     .06       0
  780.83     .12       0
Bank Sta=462.3,501.7
XS Rating Curve= 0 ,0
Exp/Cntr=0.3,0.1

Type RM Length L Ch R = 1 ,6438    ,418.3,420.8,423.5
XS GIS Cut Line= 4
     1837365.159      235316.122     1837674.364      235654.211
     1837755.321       235742.73     1838163.714      235886.158
#Sta/Elev= 30
       0 1617.45    58.5 1602.04   96.891590.877   107.2 1588.37   126.7 1585.71
  137.891583.172     156 1577.66  228.821553.074   263.2 1541.52   282.7 1537.03
   302.2 1535.67  359.351535.208   389.9 1531.07   399.7 1530.66   428.9 1530.47
   438.7 1530.52   448.4 1531.33  455.021533.113   467.4 1536.75   476.6 1538.38
  505.661540.319   542.41542.587   578.1 1544.72  611.821550.475   643.51556.814
  689.891565.311   745.4 1575.44   804.4 1588.41   853.6 1600.66    1011 1642.11
#Mann= 13 ,-1 , 0
       0     .12       0   96.89    .016       0  137.89     .12       0
  228.82     .06       0  359.35     .12       0   399.7    .045       0
   438.7     .04       0  455.02    .016       0  505.66     .12       0
   542.4    .016       0  611.82     .12       0   643.5     .06       0
  689.89     .12       0
Bank Sta=399.7,438.7
XS Rating Curve= 0 ,0
Exp/Cntr=0.3,0.1

Type RM Length L Ch R = 1 ,6017.2  ,295.6,305.3,314.8
XS GIS Cut Line= 4
     1837085.589      235471.227      1837236.73      235780.529
     1837460.589      236061.505     1837420.659      236512.894
#Sta/Elev= 30
       0 1615.58   29.531608.263    39.3 1606.11      59 1603.83   65.321602.598
    78.7 1599.54   236.1    1559   275.4 1552.83  323.071547.434   383.1 1541.09
  433.351539.108   451.1 1538.15   460.8 1536.63   489.9 1530.58   499.6 1529.82
   509.3 1529.81   548.2 1529.81  568.79 1530.53  603.451533.718   625.8 1534.95
   645.2  1536.7   730.4 1550.28   761.4 1555.69  822.831571.067   944.5 1597.88
  1002.4 1609.23  1021.7  1613.5    1041 1619.32  1137.4 1652.04  1156.7 1657.51
#Mann= 11 ,-1 , 0
       0     .12       0   29.53    .016       0   65.32     .12       0
  323.07     .06       0  433.35     .12       0   499.6    .045       0
   548.2     .04       0  568.79    .016       0  603.45     .12       0
   730.4     .06       0  822.83     .12       0
Bank Sta=499.6,548.2
XS Rating Curve= 0 ,0
Exp/Cntr=0.3,0.1

Type RM Length L Ch R = 1 ,5711.9  ,294.5,302,309.4
XS GIS Cut Line= 3
     1836872.048      235563.241      1837125.52      236141.366
     1837214.358      236540.954
#Sta/Elev= 30
       0 1618.87    19.4 1616.97    25.71615.677   203.9 1568.72   271.9 1553.84
  309.661546.837   359.3 1539.24   378.8 1537.65   417.6 1537.57   475.9 1538.08
  489.37 1537.75   495.3 1537.34     505  1535.9   534.1 1530.44   543.8  1529.8
   592.4 1530.09   602.1 1532.16   614.71538.789   631.2  1548.4     641 1553.14
   650.7 1556.76   660.5 1559.62     719    1575   777.4 1591.35   835.9  1605.5
   894.4 1620.74   952.9 1639.82  1011.4 1660.34  1021.1 1663.45  1040.6 1668.89
#Mann= 7 ,-1 , 0
       0    .016       0    25.7     .12       0  309.66     .06       0
  489.37     .12       0   543.8    .045       0   592.4     .04       0
   614.7     .12       0
Bank Sta=543.8,592.4
XS Rating Curve= 0 ,0
Exp/Cntr=0.3,0.1

Type RM Length L Ch R = 1 ,5409.9  ,289.1,290.2,291.3
XS GIS Cut Line= 3
     1836684.548      235597.963     1836821.701      236214.283
     1836988.367      236563.241
#Sta/Elev= 30
       0 1625.88    3.731625.226   28.391621.704  119.931601.272   165.1 1590.63
  216.481575.272   242.8 1569.51     272 1565.65   291.4 1562.09   330.3 1552.27
  352.881547.437   378.8 1542.91     408 1538.94   446.8 1538.74  475.421537.149
   485.7 1536.39   514.8 1530.76   524.5 1529.79   573.1 1529.88   582.8 1530.74
  593.721533.762     612 1540.62   660.4 1555.84   728.1 1576.25   776.4 1589.61
   824.8 1602.18   863.4 1610.76   911.8 1620.45   931.1 1627.34  1018.1 1663.42
#Mann= 10 ,-1 , 0
       0     .12       0    3.73    .016       0   28.39     .12       0
  119.93     .06       0  216.48     .12       0  352.88     .06       0
  475.42     .12       0   524.5    .045       0   573.1     .04       0
  593.72     .12       0
Bank Sta=524.5,573.1
XS Rating Curve= 0 ,0
Exp/Cntr=0.3,0.1

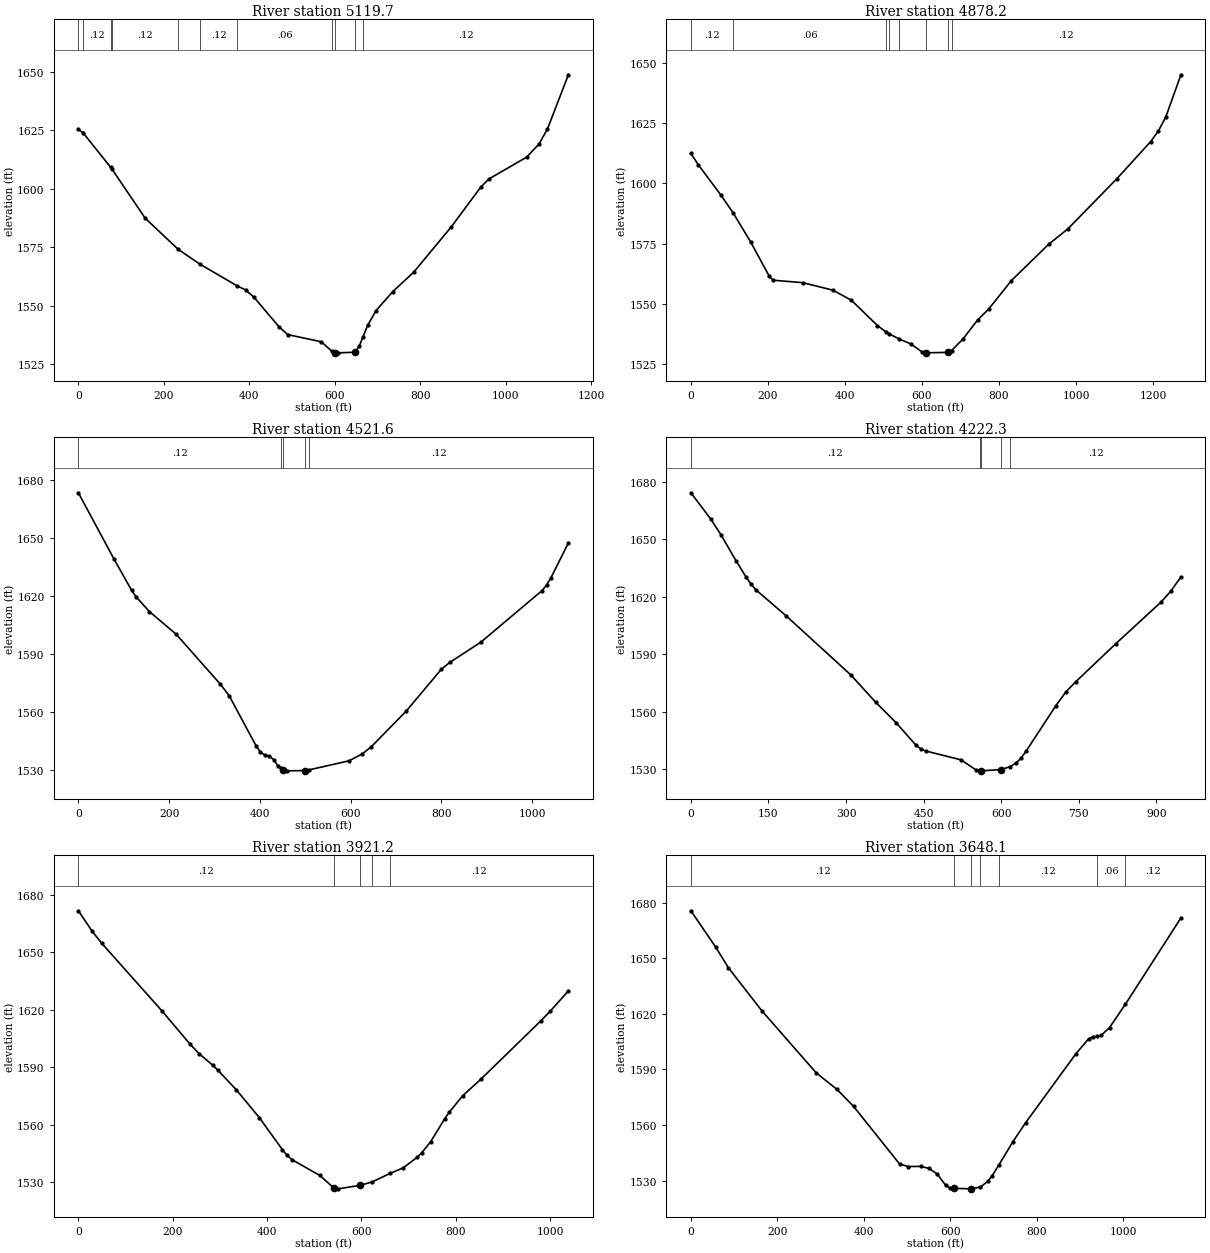
Type RM Length L Ch R = 1 ,5119.7  ,264.1,241.5,218.3
XS GIS Cut Line= 4
     1836545.659      235580.602     1836474.071      235955.347
     1836533.506       236264.63     1836835.589      236597.963
#Sta/Elev= 30
       0 1625.43   10.761624.082   75.361609.279   79.251608.293   156.5  1587.4
  233.671574.099  284.481567.756  371.711558.459   391.4 1556.72     411 1553.58
   470.1  1540.8   489.8 1537.62   568.5 1534.53  593.421530.429  601.161529.878
   607.9 1529.81   647.2 1530.08   657.1 1532.72  665.521536.483   676.8 1541.59
   696.5 1547.92   735.6 1556.02   784.5 1564.34   872.5 1583.76     941 1600.69
   960.5 1604.25  1048.5 1613.56  1077.9 1619.26  1097.4 1625.65  1146.3 1648.84
#Mann= 11 ,-1 , 0
       0    .016       0   10.76     .12       0   75.36     .08       0
   79.25     .12       0  233.67     .06       0  284.48     .12       0
  371.71     .06       0  593.42     .12       0  601.16    .045       0
   647.2     .04       0  665.52     .12       0
Bank Sta=601.16,647.2
XS Rating Curve= 0 ,0
Exp/Cntr=0.3,0.1

Type RM Length L Ch R = 1 ,4878.2  ,394.6,356.6,317.9
XS GIS Cut Line= 4
     1835743.576      235948.658     1836153.298      236124.005
     1836378.992      236347.963     1836814.756      236610.116
#Sta/Elev= 30
       0 1612.43    19.4 1607.68    77.5 1595.26  109.781587.743     155 1575.79
   203.5 1561.53   213.2 1559.89   290.6 1558.86   368.2 1555.77   416.6  1551.6
   484.2 1541.11  507.131538.368  515.431537.581  541.331535.508   570.9 1533.48
   599.8 1530.23   609.5 1529.79   667.3 1529.99  676.611530.708   705.8 1535.41
   744.4  1543.4   773.4 1547.99   832.1 1559.74   929.9 1574.92   978.8 1581.16
  1105.9 1601.94  1193.9 1617.35  1213.5 1621.68    1233 1627.53  1272.2    1645
#Mann= 8 ,-1 , 0
       0     .12       0  109.78     .06       0  507.13     .12       0
  515.43     .06       0  541.33     .12       0   609.5    .045       0
   667.3     .04       0  676.61     .12       0
Bank Sta=609.5,667.3
XS Rating Curve= 0 ,0
Exp/Cntr=0.3,0.1

Type RM Length L Ch R = 1 ,4521.6  ,289.7,299.4,308.8
XS GIS Cut Line= 3
     1835774.826      236672.616      1836406.77      236499.005
     1836811.284      236627.477
#Sta/Elev= 30
       0 1673.33    78.2 1639.23   117.4 1622.92   127.2 1619.55   156.5 1611.95
   215.2 1600.31     313  1574.4   332.6 1568.36   391.3 1542.69     401 1539.37
   410.8  1537.8   420.6 1537.25   430.4 1535.42   440.2 1532.08  446.08 1530.85
     450 1530.03   459.7 1529.64   498.8 1529.78  509.111530.177   596.7 1534.83
     626 1538.45   645.6 1542.11   722.9 1560.63     800 1582.17   819.3 1585.82
   886.9 1596.12  1021.9  1622.8  1031.6  1625.6  1041.2 1629.32  1079.8 1647.39
#Mann= 5 ,-1 , 0
       0     .12       0  446.08     .04       0     450    .045       0
   498.8     .04       0  509.11     .12       0
Bank Sta=450,498.8
XS Rating Curve= 0 ,0
Exp/Cntr=0.3,0.1

Type RM Length L Ch R = 1 ,4222.3  ,287.1,301,315
XS GIS Cut Line= 3
     1835786.978       236742.06     1836217.534       236804.56
     1836729.687      236811.505
#Sta/Elev= 30
       0  1674.2    38.7 1660.38      58 1652.31      87 1638.83   106.4 1630.33
     116 1626.58   125.7 1623.53   183.7 1610.05   309.4 1579.05   357.7 1564.72
   396.4 1554.24   435.1  1542.4   444.7 1540.44   454.4 1539.35     522  1534.8
     551 1529.54  558.04 1529.17   560.7 1529.03   599.4 1529.68  617.251531.236
   628.4 1533.07     638 1535.63   647.7 1539.18   705.7 1563.12     725 1570.26
   744.3 1575.63   821.6 1595.45   908.6 1617.06   927.9 1622.87   947.3 1630.25
#Mann= 5 ,-1 , 0
       0     .12       0  558.04     .04       0   560.7    .045       0
   599.4     .04       0  617.25     .12       0
Bank Sta=560.7,599.4
XS Rating Curve= 0 ,0
Exp/Cntr=0.3,0.1

Type RM Length L Ch R = 1 ,3921.2  ,269.2,273.1,276.9
XS GIS Cut Line= 3
     1835748.784      236874.005     1836405.034       237139.63
     1836733.159       237179.56
#Sta/Elev= 30
       0 1671.77    29.5 1661.02    49.2  1654.9     177 1619.55     236 1602.36
   255.7 1597.21   285.2 1591.08     295 1588.71   334.3 1578.46   383.5 1563.81
   432.6 1547.01   442.5 1544.04   452.3 1541.93   511.3 1533.66   540.8 1527.25
   550.6 1526.62   597.5 1528.46  622.321530.204  661.061534.712   688.3 1537.56
   717.7 1543.03   727.4 1545.35   746.9 1551.31     776 1563.06   785.7 1566.52
   814.9  1575.3   853.8 1584.03   980.2 1614.34   999.6 1619.24  1038.5 1629.93
#Mann= 5 ,-1 , 0
       0     .12       0   540.8    .045       0   597.5     .04       0
  622.32    .016       0  661.06     .12       0
Bank Sta=540.8,597.5
XS Rating Curve= 0 ,0
Exp/Cntr=0.3,0.1

Type RM Length L Ch R = 1 ,3648.1  ,298.4,323.4,348.4
XS GIS Cut Line= 3
     1835694.964      236934.769     1836033.506       237264.63
     1836617.197      237572.991
#Sta/Elev= 30
       0 1675.57    57.9  1655.8    86.8 1644.81     164 1621.65   289.4 1588.23
   337.6 1579.27   376.2 1570.03   482.4 1539.03   501.8 1537.64   530.9 1537.72
   550.3 1536.62   569.8 1533.53   589.2 1527.43   598.9 1526.13   608.6 1525.87
   647.4 1525.61   669.41526.564   686.2 1529.69     696 1532.53  711.731538.401
   744.5 1551.06   773.6 1561.21   890.1 1598.47   919.2 1606.46   928.9 1607.57
  939.671607.847   948.4 1608.39   967.8 1612.57 1004.031625.027  1132.8  1671.7
#Mann= 7 ,-1 , 0
       0     .12       0   608.6    .045       0   647.4     .04       0
   669.4    .016       0  711.73     .12       0  939.67     .06       0
 1004.03     .12       0
Bank Sta=608.6,647.4
XS Rating Curve= 0 ,0
Exp/Cntr=0.3,0.1

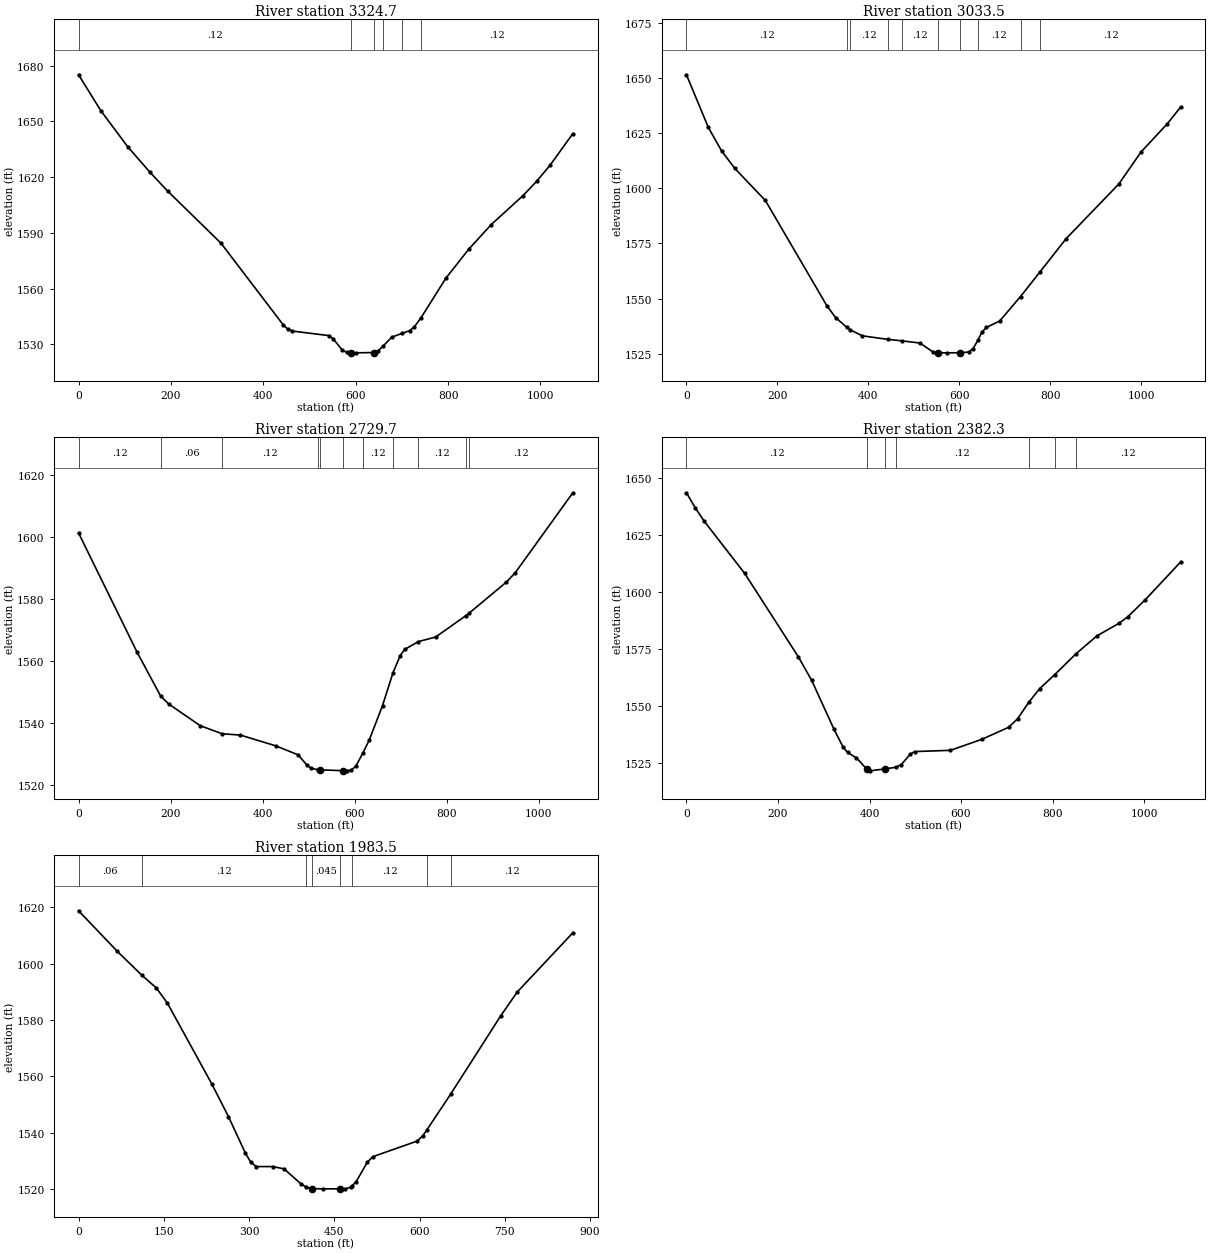
Type RM Length L Ch R = 1 ,3324.7  ,293.2,291.2,289.2
XS GIS Cut Line= 4
     1835630.728      236971.227     1835839.062      237351.435
     1835964.062      237627.477     1836158.506       237898.31
#Sta/Elev= 30
       0 1675.11    48.2 1655.81     106 1636.52   154.2 1622.76   192.7 1612.58
   308.3 1584.51   443.3 1540.49   453.1 1538.24   462.9 1537.21   541.1 1534.81
   550.8 1533.18   570.4 1527.13   580.2 1525.74   589.9 1525.52   599.7 1525.51
   638.8 1525.67   648.6 1526.64  658.661528.965   677.9 1533.93  701.241536.072
     717 1537.49   726.8 1539.47  741.651544.497   795.4 1565.74   844.4 1581.17
   893.5 1594.55   962.1 1610.09   991.5 1617.74    1021 1626.53    1070 1643.44
#Mann= 6 ,-1 , 0
       0     .12       0   589.9    .045       0   638.8     .04       0
  658.66     .12       0  701.24    .016       0  741.65     .12       0
Bank Sta=589.9,638.8
XS Rating Curve= 0 ,0
Exp/Cntr=0.3,0.1

Type RM Length L Ch R = 1 ,3033.5  ,313.3,303.9,294.4
XS GIS Cut Line= 4
     1835521.353      237059.769     1835518.516      237377.986
     1835684.548      237698.658     1835981.423      237978.172
#Sta/Elev= 30
       0 1651.42    48.2 1627.55    77.2 1616.97   106.1 1609.07   173.6 1594.48
   308.6  1546.9     328 1541.45  352.511537.077  359.621535.961   386.6 1533.19
  443.131531.553  473.311530.916   513.4 1529.92   542.7 1525.82   552.5 1525.51
     572 1525.47   601.3 1525.51   620.8 1525.83   630.5  1527.4  640.781531.088
   650.1 1534.94   659.8 1536.99     689 1539.91  734.84 1550.98  778.041562.247
   834.7  1577.1   951.2    1602   999.7  1616.4    1058 1629.32  1087.1 1636.84
#Mann= 10 ,-1 , 0
       0     .12       0  352.51     .08       0  359.62     .12       0
  443.13     .06       0  473.31     .12       0   552.5    .045       0
   601.3     .04       0  640.78     .12       0  734.84    .016       0
  778.04     .12       0
#XS Ineff= 2 , 0
       0     475                       0
Permanent Ineff=
       F       F
Bank Sta=552.5,601.3
XS Rating Curve= 0 ,0
Exp/Cntr=0.3,0.1

Type RM Length L Ch R = 1 ,2729.7  ,389.8,347.4,304.3
XS GIS Cut Line= 4
     1834962.326      237446.922     1835211.631      237583.144
     1835462.326      237863.588     1835856.423      237988.588
#Sta/Elev= 30
       0 1601.24   127.4  1562.7  178.361548.641   195.9 1546.08   264.5 1539.07
  311.86 1536.49   351.6 1536.06   428.8 1532.57     477 1529.68   496.3 1526.34
   505.9  1525.3  520.571524.899   525.2 1524.86   573.4 1524.58   583.1 1524.53
   592.7 1524.81   602.4 1526.04  617.581530.288   631.3  1534.4   660.3 1545.58
  683.151556.191   698.7 1561.71   708.3 1563.67  738.321566.221   775.6 1567.67
  841.351574.566  849.211575.479   929.5 1585.41   948.7 1588.43  1073.7  1614.2
#Mann= 11 ,-1 , 0
       0     .12       0  178.36     .06       0  311.86     .12       0
  520.57     .04       0   525.2    .045       0   573.4     .04       0
  617.58     .12       0  683.15    .016       0  738.32     .12       0
  841.35     .06       0  849.21     .12       0
Bank Sta=525.2,573.4
XS Rating Curve= 0 ,0
Exp/Cntr=0.3,0.1

Type RM Length L Ch R = 1 ,2382.3  ,413.7,398.7,383.7
XS GIS Cut Line= 3
     1834802.169      238176.088     1835513.975      237963.415
     1835848.176      238006.817
#Sta/Elev= 30
       0 1643.47    19.6 1636.73    39.1 1630.92   127.1 1608.19   244.4 1571.61
   273.7 1561.21   322.6 1539.72   342.1 1532.09   351.9 1529.64   371.4  1527.3
  393.961522.354   400.8  1521.6   433.8 1522.44  457.451523.166   469.2 1524.31
   488.8 1528.86   498.5 1530.05   576.7 1530.59   645.2 1535.39   703.8 1540.67
   723.4  1544.4  748.481551.786   771.8 1557.64  804.791563.789  850.911572.869
     897 1580.77   945.1 1586.26   964.4 1589.14  1002.9 1596.68  1079.9 1613.18
#Mann= 7 ,-1 , 0
       0     .12       0  393.96    .045       0   433.8     .04       0
  457.45     .12       0  748.48    .016       0  804.79     .06       0
  850.91     .12       0
Bank Sta=393.96,433.8
XS Rating Curve= 0 ,0
Exp/Cntr=0.3,0.1

Type RM Length L Ch R = 1 ,1983.5  ,350.1,350,349.9
XS GIS Cut Line= 2
     1835171.093      238592.755     1835843.836       238041.54
#Sta/Elev= 30
       0 1618.82    68.4 1604.37  111.561595.895   136.8 1591.44   156.4    1586
   234.5 1557.32   263.8 1545.73   293.2 1532.92   302.9 1529.55   312.7 1528.01
     342    1528   361.6 1527.19   390.9 1521.94   400.91520.669   410.4 1520.16
     430  1520.1   459.3  1520.1   469.1 1520.11   478.8 1520.64  481.571521.222
   488.6  1522.7   508.2  1529.6   517.9 1531.52   596.1 1537.08   605.9    1539
  613.03 1541.08  654.471553.639   742.7 1581.49     772    1590   869.7    1611
#Mann= 8 ,-1 , 0
       0     .06       0  111.56     .12       0   400.9     .04       0
   410.4    .045       0   459.3     .04       0  481.57     .12       0
  613.03    .016       0  654.47     .12       0
Bank Sta=410.4,459.3
XS Rating Curve= 0 ,0
Exp/Cntr=0.3,0.1