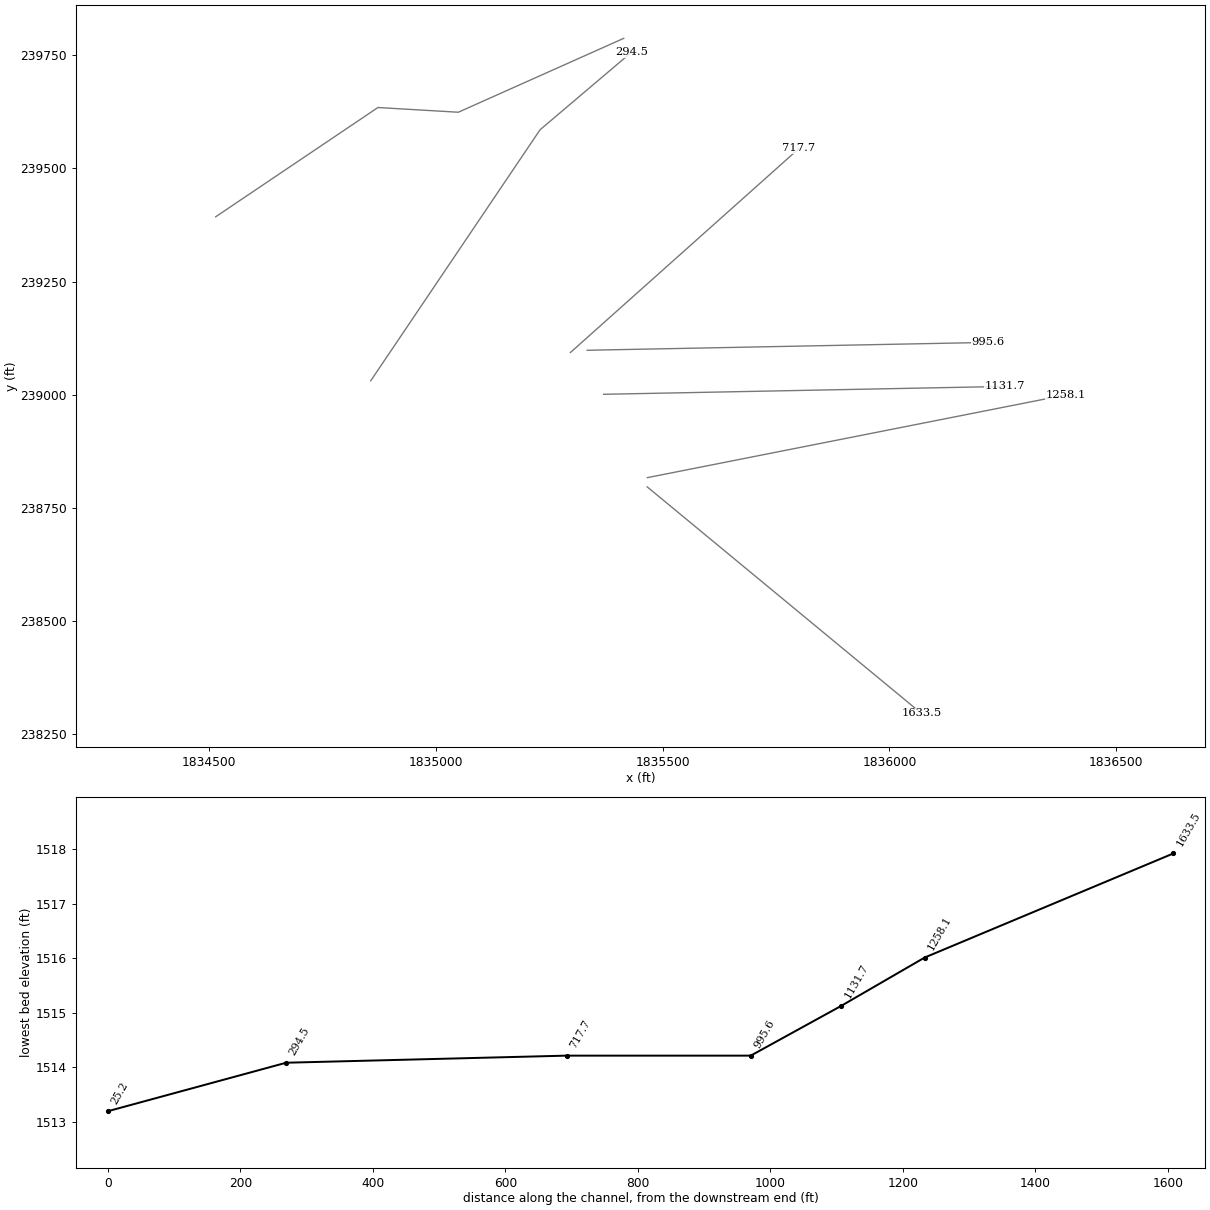
HEC-RAS study SUGARCK.prj: SUGARCK

--- SUGARCK.g01 (geometry) --- (continued)

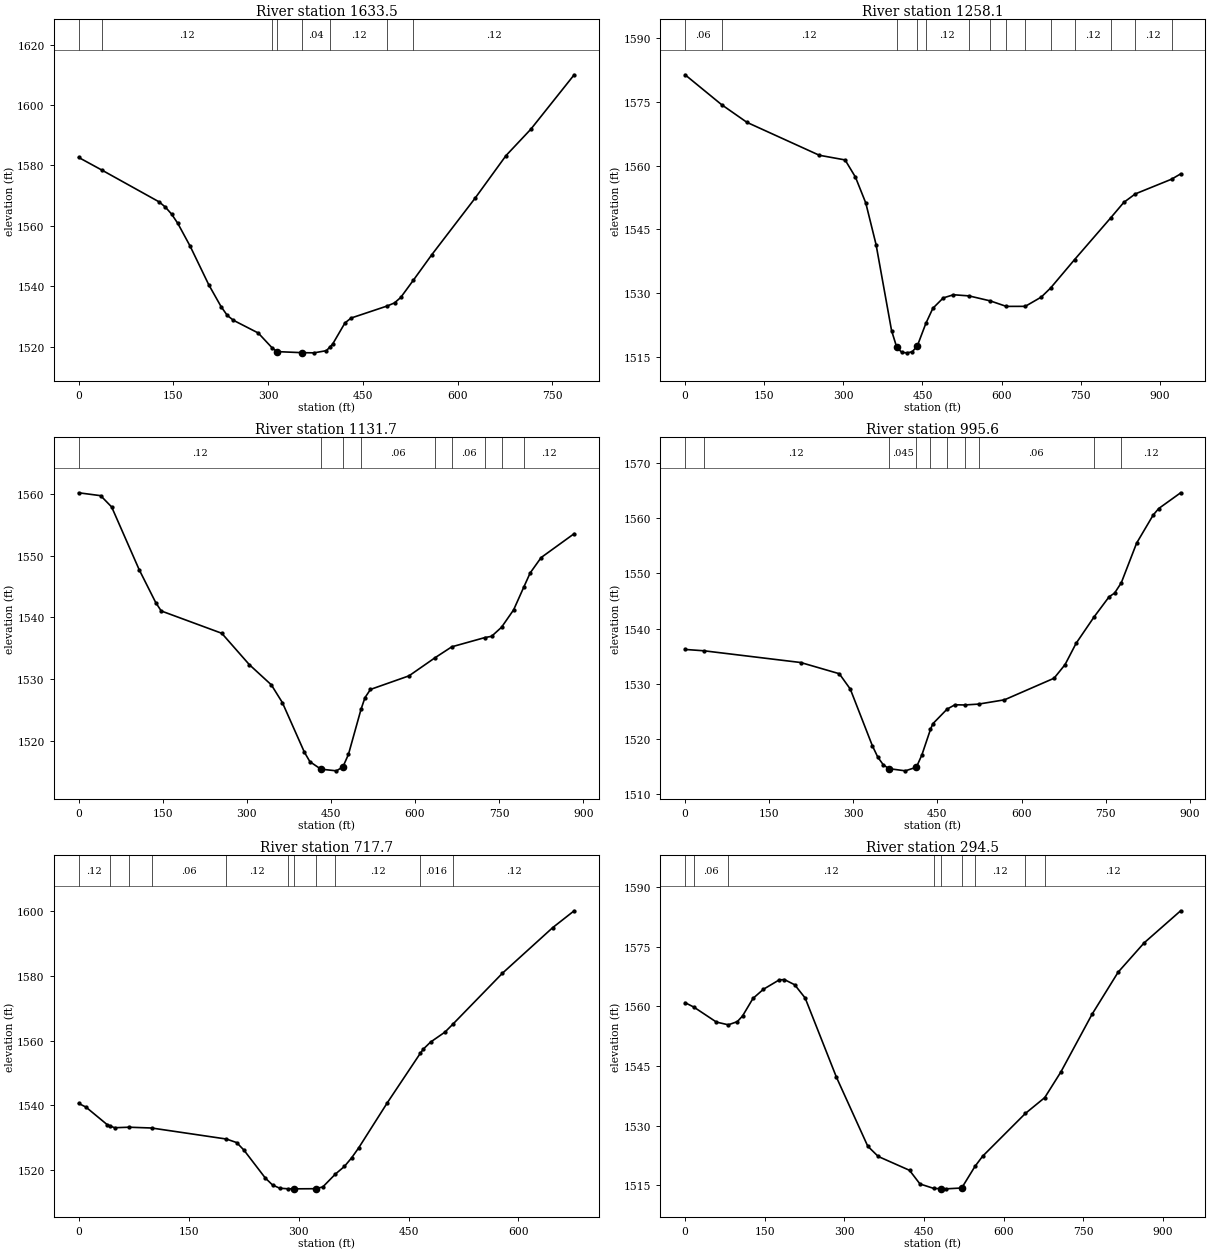
Type RM Length L Ch R = 1 ,1633.5  ,341.6,375.4,409
XS GIS Cut Line= 2
     1835466.232      238796.748     1836070.425      238296.546
#Sta/Elev= 30
       0 1582.63   37.781578.324   127.5  1567.9   137.3 1566.18   147.1 1563.88
   156.9 1560.82   176.5 1553.25   205.9  1540.5   225.5 1533.22   235.3 1530.31
   245.1 1528.69   284.3 1524.49  305.771519.682   313.8 1518.33     353 1517.98
   372.6 1517.92   392.2 1518.64  398.021519.917     402 1520.79   421.6 1527.83
   431.4 1529.45  488.811533.461     500 1534.46   509.8 1536.25  529.821541.964
   558.9 1550.38   627.5 1569.12   676.5 1583.24   715.8 1591.98   784.4    1610
#Mann= 8 ,-1 , 0
       0     .06       0   37.78     .12       0  305.77     .04       0
   313.8    .045       0     353     .04       0  398.02     .12       0
  488.81    .016       0  529.82     .12       0
Bank Sta=313.8,353
XS Rating Curve= 0 ,0
Exp/Cntr=0.3,0.1

Type RM Length L Ch R = 1 ,1258.1  ,137.8,126.4,117.1
XS GIS Cut Line= 2
     1835466.666      238817.147     1836388.134      238999.671
#Sta/Elev= 30
       0 1581.35   69.191574.329   117.4 1570.16   254.4 1562.44   303.3 1561.34
   322.9 1557.31   342.5 1551.23     362 1541.46   391.4 1521.24   401.2 1517.32
     411  1516.1   420.8 1516.01   430.6 1516.26   440.3 1517.66  456.471522.947
   469.7 1526.48   489.3 1528.91   508.8 1529.66  538.151529.391   578.71528.209
  608.911526.925   644.81526.933   675.2 1529.11  692.831531.237  738.371537.927
  806.581547.694   831.7 1551.37  853.451553.359  922.11 1556.81   939.4 1558.06
#Mann= 14 ,-1 , 0
       0     .06       0   69.19     .12       0   401.2    .045       0
   440.3     .04       0  456.47     .12       0  538.15     .08       0
   578.7     .06       0  608.91     .12       0   644.8     .06       0
  692.83    .016       0  738.37     .12       0  806.58     .06       0
  853.45     .12       0  922.11     .06       0
Bank Sta=401.2,440.3
XS Rating Curve= 0 ,0
Exp/Cntr=0.3,0.1

Type RM Length L Ch R = 1 ,1131.7  ,142,136.1,128.5
XS GIS Cut Line= 2
     1835370.312      239001.175     1836253.992      239018.536
#Sta/Elev= 30
       0  1560.2    39.3 1559.73    58.9  1557.9     108 1547.73   137.5  1542.4
   147.3 1541.04   255.3 1537.42   304.4 1532.34   343.7 1529.06   363.4 1526.18
   402.6 1518.15   412.5  1516.6   432.1 1515.39   459.9 1515.12   471.4 1515.78
   481.2 1517.78  503.641525.093   510.7 1526.99   520.5 1528.32   589.2 1530.52
     6361533.477  665.561535.229  724.671536.728   736.5 1536.93  754.221538.396
   775.8 1541.22  794.041544.928   805.3  1547.2   824.9  1549.7   883.8 1553.57
#Mann= 9 ,-1 , 0
       0     .12       0   432.1    .045       0   471.4     .04       0
  503.64     .06       0     636     .08       0  665.56     .06       0
  724.67     .08       0  754.22    .016       0  794.04     .12       0
Bank Sta=432.1,471.4
XS Rating Curve= 0 ,0
Exp/Cntr=0.3,0.1

Type RM Length L Ch R = 1 ,995.6   ,240.4,277.9,315.1
XS GIS Cut Line= 2
     1835333.853      239098.397     1836217.534      239115.758
#Sta/Elev= 30
       0 1536.21   33.511535.967   206.2 1533.84     275 1531.81   294.6 1529.03
   333.9 1518.78   343.7 1516.69   353.5  1515.3   363.4 1514.61   392.8 1514.21
   412.5 1514.87   422.3 1517.09  437.651521.727   441.9 1522.75  467.21 1525.39
   481.2 1526.18   498.61526.147  523.291526.303   569.6 1527.08     658 1530.99
   677.6 1533.45   697.3 1537.31  729.381542.097   756.2 1545.75     766 1546.42
  777.941548.286   805.3 1555.48   834.8 1560.56   844.6 1561.74   883.8  1564.6
#Mann= 10 ,-1 , 0
       0     .06       0   33.51     .12       0   363.4    .045       0
   412.5     .04       0  437.65     .12       0  467.21     .06       0
   498.6     .12       0  523.29     .06       0  729.38    .016       0
  777.94     .12       0
Bank Sta=363.4,412.5
XS Rating Curve= 0 ,0
Exp/Cntr=0.3,0.1

Type RM Length L Ch R = 1 ,717.7   ,414.1,423.2,432.1
XS GIS Cut Line= 2
     1835296.988      239093.421     1835800.867      239544.144
#Sta/Elev= 30
       0 1540.62     9.8 1539.51    39.2 1534.01   42.371533.716      49  1533.1
   68.68 1533.26   99.541533.017  201.691529.602   215.6 1528.51   225.4 1526.21
   254.7 1517.54   264.5 1515.41   274.3  1514.4  285.061514.237   293.9 1514.21
   323.3 1514.25   333.1  1514.8  350.361518.796   362.5 1521.12   372.3 1523.76
   382.1  1526.9   421.3 1540.89  466.031556.088   470.3 1557.43   480.1 1559.58
   499.7 1562.66  510.371565.076   578.1 1580.86   646.7 1594.96     676 1600.17
#Mann= 11 ,-1 , 0
       0     .12       0   42.37     .06       0   68.68     .12       0
   99.54     .06       0  201.69     .12       0  285.06     .04       0
   293.9    .045       0   323.3     .04       0  350.36     .12       0
  466.03    .016       0  510.37     .12       0
Bank Sta=293.9,323.3
XS Rating Curve= 0 ,0
Exp/Cntr=0.3,0.1

Type RM Length L Ch R = 1 ,294.5   ,311.3,269.3,226.6
XS GIS Cut Line= 3
     1834856.884      239030.921     1835230.121      239585.376
     1835431.944      239756.817
#Sta/Elev= 30
       0 1560.88   16.611559.757      59    1556   81.381555.314    98.3 1556.11
   108.1 1557.52   127.8 1561.94   147.4 1564.24   176.9 1566.58   186.8  1566.7
   206.4 1565.38   226.1 1562.05     285 1542.14     344  1524.8   363.7 1522.22
   422.6 1518.74   442.3 1515.31  468.361514.181   481.6 1514.11   491.4 1514.08
   520.9 1514.29  545.861519.715   560.3 1522.28  640.791533.032  677.271537.012
   707.6 1543.45   766.4 1557.97   815.5 1568.55   864.5 1575.92   933.2 1583.98
#Mann= 9 ,-1 , 0
       0    .016       0   16.61     .06       0   81.38     .12       0
  468.36     .04       0   481.6    .045       0   520.9     .04       0
  545.86     .12       0  640.79    .016       0  677.27     .12       0
Bank Sta=481.6,520.9
XS Rating Curve= 0 ,0
Exp/Cntr=0.3,0.1

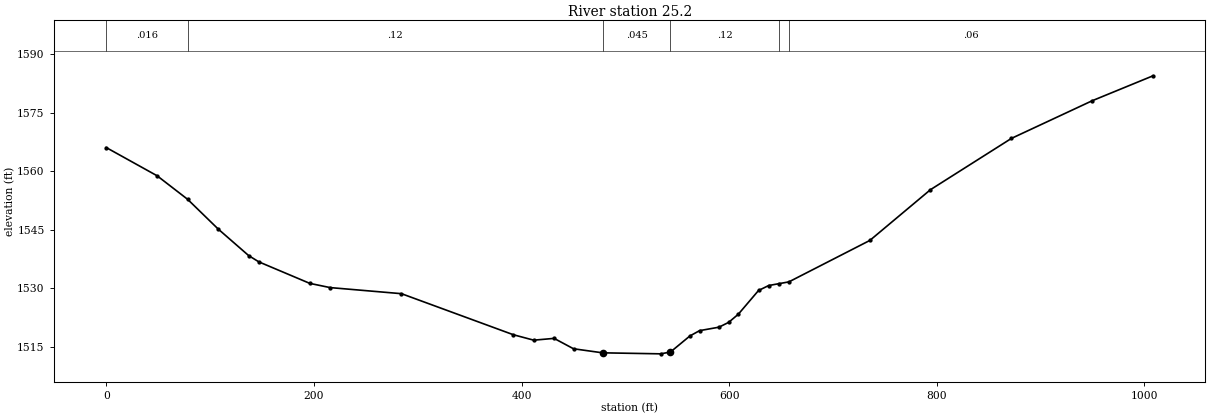
Type RM Length L Ch R = 1 ,25.2    ,0,25.2,52.8
XS GIS Cut Line= 4
     1834515.179      239393.139     1834872.818      239634.458
     1835049.901      239624.041     1835414.485      239787.236
#Sta/Elev= 30
       0 1566.04      49 1558.81    78.4 1552.78   107.9 1545.15   137.3 1538.34
   147.1 1536.74   196.1 1531.24   215.7 1530.16   284.4  1528.6   392.2 1518.08
   411.8 1516.69   431.4 1517.15   450.1 1514.49   478.1 1513.45   534.1 1513.19
   543.5 1513.66   562.2 1517.77   571.5 1519.13   590.2 1520.02   599.5 1521.25
   608.8 1523.33   628.3 1529.42   638.1 1530.69   647.8 1531.16   657.5 1531.62
   735.5 1542.24   793.9 1555.24   871.9 1568.38   949.8 1578.04  1008.3 1584.42
#Mann= 6 ,-1 , 0
       0    .016       0    78.4     .12       0   478.1    .045       0
   543.5     .12       0   647.8    .016       0   657.5     .06       0
Bank Sta=478.1,543.5
XS Rating Curve= 0 ,0
Exp/Cntr=0.3,0.1

Chan Stop Cuts=-1
Use User Specified Reach Order=0
Composite Channel Slope=5